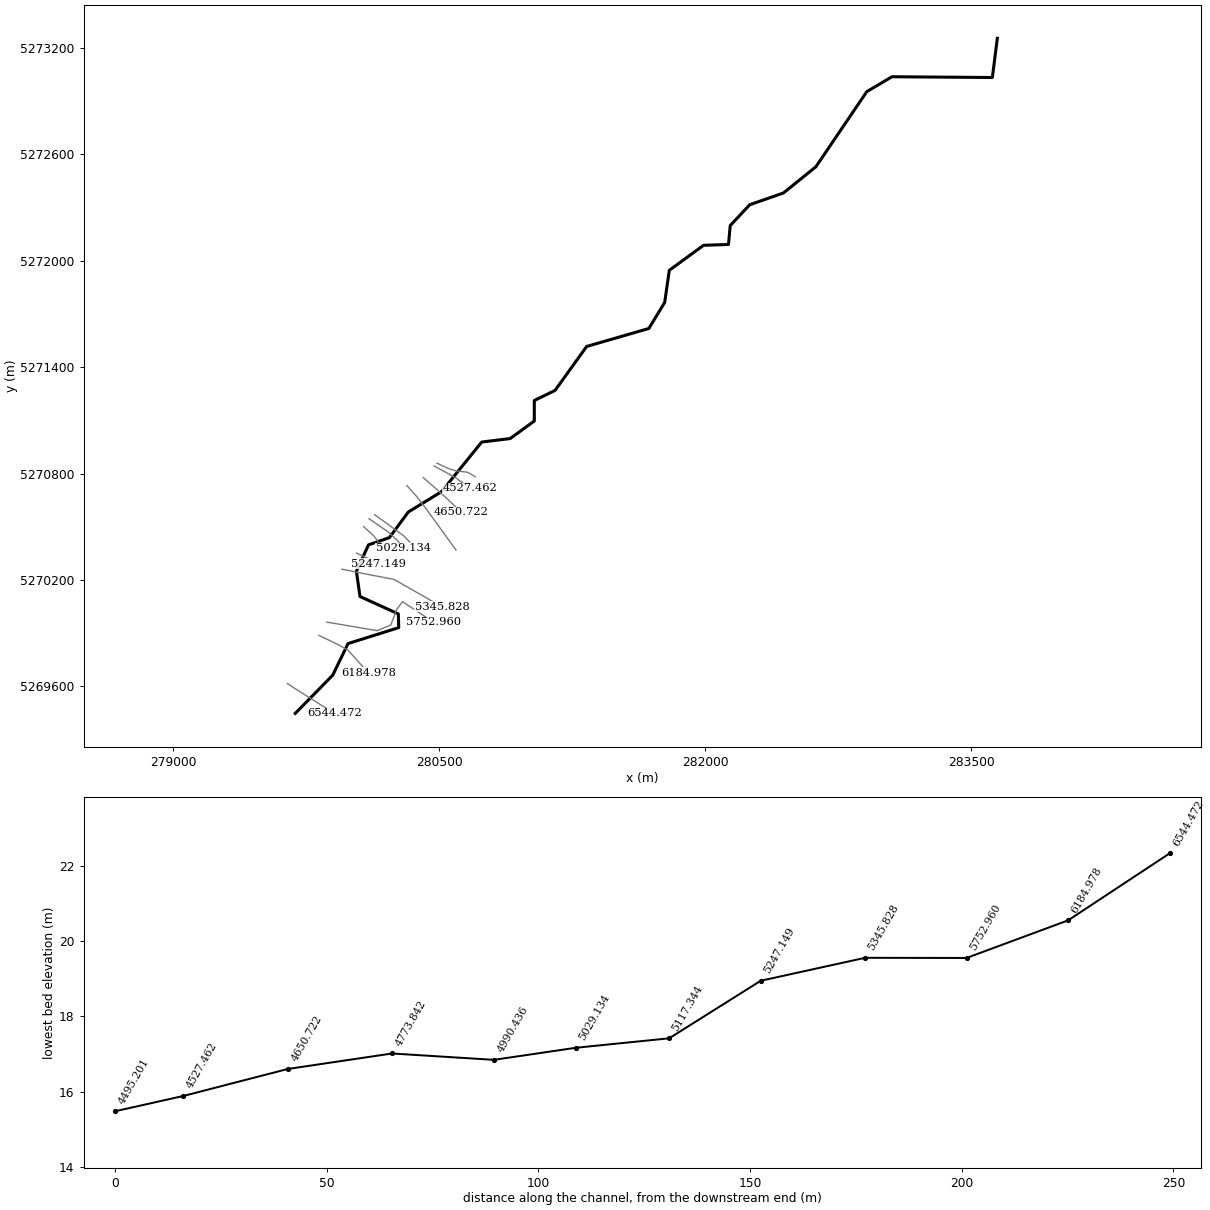
--- ShearstownModel.prj (project) ---

Proj Title=Shearstown Model
Current Plan=p01
Default Exp/Contr=0.3,0.1
SI Units
Geom File=g16
Geom File=g01
Geom File=g02
Geom File=g03
Flow File=f04
Flow File=f05
Flow File=f01
Flow File=f02
Flow File=f03
Flow File=f06
Flow File=f07
Flow File=f08
Plan File=p10
Plan File=p01
Plan File=p02
Plan File=p03
Plan File=p04
Plan File=p05
Plan File=p06
Plan File=p07
Plan File=p08
Y Axis Title=Elevation
X Axis Title(PF)=Main Channel Distance
X Axis Title(XS)=Station
BEGIN DESCRIPTION:
END DESCRIPTION:
DSS File=dss
DSS Export Rating Curves= 0
DSS Export Rating Curve Sorted= 0
DSS Export Volume Flow Curves= 0
DXF OffsetX= 0
DXF OffsetY= 0
DXF ScaleX= 1
DXF ScaleY= 10

--- ShearstownModel.p01 (plan) ---

Plan Title=Flood Flows
Program Version=4.10
Short Identifier=Flood
Geom File=g01
Flow File=f04
Mixed Flow
K Sum by GR= 0
Std Step Tol= 0.003
Critical Tol= 0.003
Num of Std Step Trials= 40
Max Error Tol= 0.1
Flow Tol Ratio= 0.001
Split Flow NTrial= 60
Split Flow Tol= 0.006
Split Flow Ratio= 0.05
Log Output Level= 0
Friction Slope Method= 1
Unsteady Friction Slope Method= 2
Unsteady Bridges Friction Slope Method= 1
Parabolic Critical Depth
Global Vel Dist= 0 , 0 , 0
Global Log Level= 0
CheckData=True
Encroach Param=-1 ,0,0, 0
Optimized Weir=Shearstown_Brook,Main            ,500
Optimized Weir=Shearstown_Brook,Main            ,350
Optimized Weir=Shearstown_Brook,Main            ,200
Computation Interval=1HOUR
Output Interval=1HOUR
Run HTab= 0
Run UNet= 0
Run PostProcess= 0
Run WQNet= 0
UNET Theta= 1
UNET Theta Warmup= 1
UNET ZTol= 0.006
UNET ZSATol= 0.015
UNET MxIter= 20
UNET MaxInSteps= 0
UNET DtIC= 0
UNET DtMin= 0
UNET MaxCRTS= 20
UNET WFStab= 2
UNET SFStab= 1
UNET WFX= 1
UNET SFX= 1
UNET DSS MLevel= 4
UNET DZMax Abort= 30
UNET Convert EG Bridges= 0
UNET Use Existing IB Tables=-1
UNET Froude Reduction=False
UNET Froude Limit= 1
UNET Froude Power= 10
UNET Time Slicing=0,0, 5
UNET Junction Losses=0
Instantaneous Interval=1HOUR
Write IC File= 0
Write IC File at Sim End=0
Echo Input=False
Echo Parameters=False
Echo Output=False
Write Detailed= 0
WQ AD Non Conservative
WQ ULTIMATE=-1
WQ Max Comp Step=1HOUR
WQ Output Interval=15MIN
WQ Output Selected Increments= 0
WQ Output face flow=0
WQ Output face velocity=0
WQ Output face area=0
WQ Output face dispersion=0
WQ Output cell volume=0
WQ Output cell surface area=0
WQ Output cell continuity=0
WQ Output cumulative cell continuity=0
WQ Output face conc=0
WQ Output face dconc_dx=0
WQ Output face courant=0
WQ Output face peclet=0
WQ Output face adv mass=0
WQ Output face disp mass=0
WQ Output cell mass=0
WQ Output cell source sink temp=0
WQ Output cell source sink nsm=0
WQ Output MaxMinRange=-1
WQ Daily Max Min Mean=-1
WQ Daily Range=0
WQ Daily Time=0
WQ Create Restart=0
WQ Fixed Restart=0
WQ System Summary=0
WQ Use Fixed Temperature=0
Sorting and Armoring Iterations= 10
XS Update Threshold= 0.02
Hydraulics Update Threshold= 0.02
Energy Slope Method= 1
Volume Change Method= 0
XS Weighting Method= 0
Number of US Weighted Cross Sections= 1
Number of DS Weighted Cross Sections= 1
Upstream XS Weight=0.25
Main XS Weight=0.5
Downstream XS Weight=0.25
Number of DS XS's Weighted with US Boundary= 1
Upstream Boundary Weight= 1
Weight of XSs Associated with US Boundary= 0
Number of US XS's Weighted with DS Boundary= 1
Downstream Boundary Weight= 0.5
Weight of XSs Associated with DS Boundary= 0.5
Sediment Output Level= 4
Mass or Volume Output= 0
Output Increment Type= 1
Profile and TS Output Increment= 10
XS Output Flag= 0
XS Output Increment= 10
Disregard all LS=0
Disregard all Conn=0
Disregard all Breaches=0
Disregard all Pumps=0

--- ShearstownModel.p02 (plan) ---

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Plan Title=Sensitivity n+20%
Short Identifier=Sens_n+20%
Geom File=g02
Flow File=f01

--- ShearstownModel.p03 (plan) ---

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Plan Title=Sensitivity n-20%
Short Identifier=Sens_n-20%
Geom File=g03
Flow File=f01

--- ShearstownModel.p04 (plan) ---

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Plan Title=Sensitivity Flows
Short Identifier=Sens_Flow
Geom File=g01
Flow File=f02

--- ShearstownModel.p05 (plan) ---

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Plan Title=Sensitivity DS WL (2m surge)
Short Identifier=Sens DS WL
Geom File=g01
Flow File=f03

--- ShearstownModel.p06 (plan) ---

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Plan Title=Bridge Capacities
Short Identifier=Bridge Capacity
Geom File=g01
Flow File=f06
Num of Std Step Trials= 20
Split Flow NTrial= 30
Split Flow Ratio= 0.02

--- ShearstownModel.p07 (plan) ---

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Plan Title=Bridge Capacities2
Short Identifier=Bridge Cap 2
Geom File=g01
Flow File=f07
Num of Std Step Trials= 20
Split Flow NTrial= 30
Split Flow Ratio= 0.02

--- ShearstownModel.p08 (plan) ---

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Plan Title=Mean Annual Flow
Short Identifier=MAF
Geom File=g16
Flow File=f08

--- ShearstownModel.p10 (plan) ---

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Plan Title=Calibration
Short Identifier=Calib
Geom File=g16
Flow File=f05

--- ShearstownModel.f04 (steady flow) ---

Flow Title=Flood Flows 20,100,CC
Program Version=4.10
Number of Profiles= 14
Profile Names=1:20,1:100,1:100 CGCM2 2020s,1:100 CGCM2 2050s,1:100 CGCM2 2080s,1:20 CGCM2 2020s,1:20 CGCM2 2050s,1:20 CGCM2 2080s,1:100 HadCM3 2020s,1:100 HadCM3 2050s,1:100 HadCM3 2080s,1:20 HadCM3 2020s,1:20 HadCM3 2050s,1:20 HadCM3 2080s
River Rch & RM=Shearstown_Brook,Main            ,6544.472
      26      38    65.8    74.3      55      47    51.5    41.3    50.6   105.2
    64.6    38.6    69.3    45.6
River Rch & RM=Shearstown_Brook,Main            ,4527.462
      29      42    69.8      79      58    49.9    54.7    43.8    53.7   111.7
    68.5      41    73.6    48.4
River Rch & RM=Shearstown_Brook,Main            ,4444.284
      34      49    75.9    85.9      63    54.1    59.4    47.6    58.4   121.5
    74.5    44.5      80    52.6
River Rch & RM=Shearstown_Brook,Main            ,2846.736
      37      53    83.8      95    69.5    59.6    65.5    52.4    64.3   134.6
    82.2      49    88.4    57.9
River Rch & RM=Shearstown_Brook,Main            ,1960.358
      39      57    95.3   107.9    79.2      68    74.7    59.9    73.3   152.3
    93.5      56   100.5    66.1
Boundary for River Rch & Prof#=Shearstown_Brook,Main            , 1
Up Type= 3
Up Slope=0.0001
Dn Type= 1
Dn Known WS=1.7
Boundary for River Rch & Prof#=Shearstown_Brook,Main            , 2
Up Type= 3
Up Slope=0.0001
Dn Type= 1
Dn Known WS=1.7
Boundary for River Rch & Prof#=Shearstown_Brook,Main            , 3
Up Type= 3
Up Slope=0.0001
Dn Type= 1
Dn Known WS=1.7
DSS Import GetInterval= 0
DSS Import GetPeak= 0
DSS Import FillOption= 0

--- ShearstownModel.f01 (steady flow) ---

Flow Title=Flood Flows 20,100
Program Version=4.10
Number of Profiles= 2
Profile Names=1:20,1:100
River Rch & RM=Shearstown_Brook,Main            ,6544.472
      26      38
River Rch & RM=Shearstown_Brook,Main            ,4527.462
      29      42
River Rch & RM=Shearstown_Brook,Main            ,4444.284
      34      49
River Rch & RM=Shearstown_Brook,Main            ,2846.736
      37      53
River Rch & RM=Shearstown_Brook,Main            ,1960.358
      39      57
Boundary for River Rch & Prof#=Shearstown_Brook,Main            , 1
Up Type= 3
Up Slope=0.0001
Dn Type= 1
Dn Known WS=1.7
Boundary for River Rch & Prof#=Shearstown_Brook,Main            , 2
Up Type= 3
Up Slope=0.0001
Dn Type= 1
Dn Known WS=1.7
DSS Import GetInterval= 0
DSS Import GetPeak= 0
DSS Import FillOption= 0

--- ShearstownModel.f02 (steady flow) ---

Flow Title=Flood Flows 20,100 sens10%
Program Version=4.10
Number of Profiles= 10
Profile Names=1:20,1:100,1:20 -10%,1:20 +10%,1:100 -10%,1:100 +10%,1:20 -30%,1:20 +30%,1:100 -30%,1:100 +30%
River Rch & RM=Shearstown_Brook,Main            ,6544.472
      26      38      23      29      34      42      18      34      27      49
River Rch & RM=Shearstown_Brook,Main            ,4527.462
      29      42      26      32      38      47      20      38      30      55
River Rch & RM=Shearstown_Brook,Main            ,4444.284
      34      49      30      37      44      54      24      44      34      64
River Rch & RM=Shearstown_Brook,Main            ,2846.736
      37      53      33      40      48      58      26      47      37      69
River Rch & RM=Shearstown_Brook,Main            ,1960.358
      39      57      35      43      51      62      27      51      40      74
Boundary for River Rch & Prof#=Shearstown_Brook,Main            , 1
Up Type= 3
Up Slope=0.0001
Dn Type= 1
Dn Known WS=1.7
Boundary for River Rch & Prof#=Shearstown_Brook,Main            , 2
Up Type= 3
Up Slope=0.0001
Dn Type= 1
Dn Known WS=1.7
Boundary for River Rch & Prof#=Shearstown_Brook,Main            , 3
Up Type= 3
Up Slope=0.0001
Dn Type= 1
Dn Known WS=1.7
DSS Import GetInterval= 0
DSS Import GetPeak= 0
DSS Import FillOption= 0

--- ShearstownModel.f03 (steady flow) ---

Flow Title=Flood Flows 20,100 sens DS WL
Program Version=4.10
Number of Profiles= 2
Profile Names=1:20,1:100
River Rch & RM=Shearstown_Brook,Main            ,6544.472
      26      38
River Rch & RM=Shearstown_Brook,Main            ,4527.462
      29      42
River Rch & RM=Shearstown_Brook,Main            ,4444.284
      34      49
River Rch & RM=Shearstown_Brook,Main            ,2846.736
      37      53
River Rch & RM=Shearstown_Brook,Main            ,1960.358
      39      57
Boundary for River Rch & Prof#=Shearstown_Brook,Main            , 1
Up Type= 3
Up Slope=0.0001
Dn Type= 1
Dn Known WS=2.7
Boundary for River Rch & Prof#=Shearstown_Brook,Main            , 2
Up Type= 3
Up Slope=0.0001
Dn Type= 1
Dn Known WS=2.7
DSS Import GetInterval= 0
DSS Import GetPeak= 0
DSS Import FillOption= 0

--- ShearstownModel.f05 (steady flow) ---

Flow Title=Calibration Flows
Program Version=4.10
Number of Profiles= 5
Profile Names=Aug13/10 LiDAR,Aug30/10 Survey,Aug31/10 Survey,Sep1/10 Survey,Sep21/10 HighWL
River Rch & RM=Shearstown_Brook,Main            ,6544.472
    .473    .102    .075     .06      27
River Rch & RM=Shearstown_Brook,Main            ,4527.462
    .528    .114    .084    .067      30
River Rch & RM=Shearstown_Brook,Main            ,4444.284
    .613    .132    .097    .078      35
River Rch & RM=Shearstown_Brook,Main            ,2846.736
    .643    .138    .102    .082      37
River Rch & RM=Shearstown_Brook,Main            ,1960.358
    .706    .152    .112     .09      40
Boundary for River Rch & Prof#=Shearstown_Brook,Main            , 1
Up Type= 3
Up Slope=0.0001
Dn Type= 1
Dn Known WS=-0.25
Boundary for River Rch & Prof#=Shearstown_Brook,Main            , 2
Up Type= 3
Up Slope=0.0001
Dn Type= 1
Dn Known WS=0.16
Boundary for River Rch & Prof#=Shearstown_Brook,Main            , 3
Up Type= 3
Up Slope=0.0001
Dn Type= 1
Dn Known WS=0.1
Boundary for River Rch & Prof#=Shearstown_Brook,Main            , 4
Up Type= 3
Up Slope=0.0001
Dn Type= 1
Dn Known WS=0
Boundary for River Rch & Prof#=Shearstown_Brook,Main            , 5
Up Type= 3
Up Slope=0.0001
Dn Type= 1
Dn Known WS=1.19
Observed WS=Shearstown_Brook,Main            ,6544.472,,22.44,,,22.64184,
Observed WS=Shearstown_Brook,Main            ,6184.978,,20.67,,,20.95005,
Observed WS=Shearstown_Brook,Main            ,5752.960,,19.87,,,20.16745,21.49
Observed WS=Shearstown_Brook,Main            ,5345.828,,19.47,,,19.88958,
Observed WS=Shearstown_Brook,Main            ,5247.149,,18.89,,,19.191,19.98
Observed WS=Shearstown_Brook,Main            ,5117.344,,17.35,,,17.62281,
Observed WS=Shearstown_Brook,Main            ,5029.134,,16.91,,17.412,,
Observed WS=Shearstown_Brook,Main            ,4990.436,,16.67,,,17.42075,
Observed WS=Shearstown_Brook,Main            ,4773.842,,16.85,,17.25839,,
Observed WS=Shearstown_Brook,Main            ,4650.722,,16.56,,16.79436,,
Observed WS=Shearstown_Brook,Main            ,4527.462,,15.8,,16.056,,
Observed WS=Shearstown_Brook,Main            ,4495.201,,15.51,,15.80389,,
Observed WS=Shearstown_Brook,Main            ,4476.356,,15.53,,15.79571,,
Observed WS=Shearstown_Brook,Main            ,4444.284,,15.64,,15.78496,,
Observed WS=Shearstown_Brook,Main            ,4338.646,,15.15,,15.25665,,
Observed WS=Shearstown_Brook,Main            ,4224.649,,14.55,,14.93124,,
Observed WS=Shearstown_Brook,Main            ,4113.600,,14.03,,14.21454,,
Observed WS=Shearstown_Brook,Main            ,4031.147,,13.36,,13.51369,,
Observed WS=Shearstown_Brook,Main            ,3923.947,,12.95,,13.05725,,
Observed WS=Shearstown_Brook,Main            ,3746.619,,11.64,,11.86337,,
Observed WS=Shearstown_Brook,Main            ,3558.752,,10.39,,10.68238,,
Observed WS=Shearstown_Brook,Main            ,3332.329,,9.2,,9.3757,,
Observed WS=Shearstown_Brook,Main            ,3046.631,,6.91,,7.164453,,
Observed WS=Shearstown_Brook,Main            ,2940.559,,5.54,,5.730798,,
Observed WS=Shearstown_Brook,Main            ,2917.845,,5.42,,5.709237,,
Observed WS=Shearstown_Brook,Main            ,2905.134,,5.48,,5.705289,,
Observed WS=Shearstown_Brook,Main            ,2885.103,,5.44,,,,
Observed WS=Shearstown_Brook,Main            ,2876.564,,5.4,,,,
Observed WS=Shearstown_Brook,Main            ,2846.736,,5.36,,5.740744,,
Observed WS=Shearstown_Brook,Main            ,2697.410,,4.28,,4.51613,,5.32
Observed WS=Shearstown_Brook,Main            ,2581.398,,3.28,,3.487967,,
Observed WS=Shearstown_Brook,Main            ,2472.819,,2.41,,2.629684,,
Observed WS=Shearstown_Brook,Main            ,2341.402,,1.45,,1.742887,,
Observed WS=Shearstown_Brook,Main            ,2240.664,,0.64,,0.9175265,,
Observed WS=Shearstown_Brook,Main            ,2138.891,,0.11,,0.143711,,2.45
Observed WS=Shearstown_Brook,Main            ,2107.745,,0.13,,0.093424,,
Observed WS=Shearstown_Brook,Main            ,2090.583,,0.02,,0.086,,
Observed WS=Shearstown_Brook,Main            ,2065.870,,0.11,,0.0466685,,
Observed WS=Shearstown_Brook,Main            ,1960.358,,-0.04,0.173169,,,
Observed WS=Shearstown_Brook,Main            ,1814.866,,0.04,0.186096,,,
Observed WS=Shearstown_Brook,Main            ,1545.071,,-0.16,0.297354,,,
Observed WS=Shearstown_Brook,Main            ,1156.731,,0.05,0.3445445,,,1.16
Observed WS=Shearstown_Brook,Main            ,735.6188,,-0.02,0.3686195,,,
Observed WS=Shearstown_Brook,Main            ,519.9265,,-0.23,0.3906197,,,
Observed WS=Shearstown_Brook,Main            ,443.9145,,0.01,,0.1758075,,
Observed WS=Shearstown_Brook,Main            ,426.8590,,0.03,,0.1408295,,
Observed WS=Shearstown_Brook,Main            ,377.6255,,-0.24,0.305459,,,1.03
Observed WS=Shearstown_Brook,Main            ,310.9396,,-0.14,,-0.0247275,,
Observed WS=Shearstown_Brook,Main            ,280.4603,,-0.46,,0.019482,,
Observed WS=Shearstown_Brook,Main            ,130.9306,,-0.18,0.16216,,,
Observed WS=Shearstown_Brook,Main            ,95.07389,,-0.25,,0.043064,,
Observed WS=Shearstown_Brook,Main            ,72.16455,,-0.3,,0.104541,,
Observed WS=Shearstown_Brook,Main            ,43.48671,,,,,,
DSS Import GetInterval= 0
DSS Import GetPeak= 0
DSS Import FillOption= 0

--- ShearstownModel.f06 (steady flow) ---

Flow Title=Bridge Capacities
Program Version=4.10
Number of Profiles= 100
Profile Names=PF 1,PF 2,PF 3,PF 4,PF 5,PF 6,PF 7,PF 8,PF 9,PF 10,PF 11,PF 12,PF 13,PF 14,PF 15,PF 16,PF 17,PF 18,PF 19,PF 20,PF 21,PF 22,PF 23,PF 24,PF 25,PF 26,PF 27,PF 28,PF 29,PF 30,PF 31,PF 32,PF 33,PF 34,PF 35,PF 36,PF 37,PF 38,PF 39,PF 40,PF 41,PF 42,PF 43,PF 44,PF 45,PF 46,PF 47,PF 48,PF 49,PF 50,PF 51,PF 52,PF 53,PF 54,PF 55,PF 56,PF 57,PF 58,PF 59,PF 60,PF 61,PF 62,PF 63,PF 64,PF 65,PF 66,PF 67,PF 68,PF 69,PF 70,PF 71,PF 72,PF 73,PF 74,PF 75,PF 76,PF 77,PF 78,PF 79,PF 80,PF 81,PF 82,PF 83,PF 84,PF 85,PF 86,PF 87,PF 88,PF 89,PF 90,PF 91,PF 92,PF 93,PF 94,PF 95,PF 96,PF 97,PF 98,PF 99,PF 100
River Rch & RM=Shearstown_Brook,Main            ,6544.472
      10      20      30      40      50      60      70      80      90     100
     110     120     130     140     150     160     170     180     190     200
     210     220     230     240     250     260     270     280     290     300
     310     320     330     340     350     360     370     380     390     400
     410     420     430     440     450     460     470     480     490     500
     510     520     530     540     550     560     570     580     590     600
     610     620     630     640     650     660     670     680     690     700
     710     720     730     740     750     760     770     780     790     800
     810     820     830     840     850     860     870     880     890     900
     910     920     930     940     950     960     970     980     990    1000
Boundary for River Rch & Prof#=Shearstown_Brook,Main            , 1
Up Type= 3
Up Slope=0.0001
Dn Type= 1
Dn Known WS=0
Boundary for River Rch & Prof#=Shearstown_Brook,Main            , 2
Up Type= 3
Up Slope=0.0001
Dn Type= 1
Dn Known WS=0
Boundary for River Rch & Prof#=Shearstown_Brook,Main            , 3
Up Type= 3
Up Slope=0.0001
Dn Type= 1
Dn Known WS=0
Boundary for River Rch & Prof#=Shearstown_Brook,Main            , 4
Up Type= 3
Up Slope=0.0001
Dn Type= 1
Dn Known WS=0
Boundary for River Rch & Prof#=Shearstown_Brook,Main            , 5
Up Type= 3
Up Slope=0.0001
Dn Type= 1
Dn Known WS=0
Boundary for River Rch & Prof#=Shearstown_Brook,Main            , 6
Up Type= 3
Up Slope=0.0001
Dn Type= 1
Dn Known WS=0
Boundary for River Rch & Prof#=Shearstown_Brook,Main            , 7
Up Type= 3
Up Slope=0.0001
Dn Type= 1
Dn Known WS=0
Boundary for River Rch & Prof#=Shearstown_Brook,Main            , 8
Up Type= 3
Up Slope=0.0001
Dn Type= 1
Dn Known WS=0
Boundary for River Rch & Prof#=Shearstown_Brook,Main            , 9
Up Type= 3
Up Slope=0.0001
Dn Type= 1
Dn Known WS=0
Boundary for River Rch & Prof#=Shearstown_Brook,Main            , 10
Up Type= 3
Up Slope=0.0001
Dn Type= 1
Dn Known WS=0
Boundary for River Rch & Prof#=Shearstown_Brook,Main            , 11
Up Type= 3
Up Slope=0.0001
Dn Type= 1
Dn Known WS=0
Boundary for River Rch & Prof#=Shearstown_Brook,Main            , 12
Up Type= 3
Up Slope=0.0001
Dn Type= 1
Dn Known WS=0
Boundary for River Rch & Prof#=Shearstown_Brook,Main            , 13
Up Type= 3
Up Slope=0.0001
Dn Type= 1
Dn Known WS=0
Boundary for River Rch & Prof#=Shearstown_Brook,Main            , 14
Up Type= 3
Up Slope=0.0001
Dn Type= 1
Dn Known WS=0
Boundary for River Rch & Prof#=Shearstown_Brook,Main            , 15
Up Type= 3
Up Slope=0.0001
Dn Type= 1
Dn Known WS=0
Boundary for River Rch & Prof#=Shearstown_Brook,Main            , 16
Up Type= 3
Up Slope=0.0001
Dn Type= 1
Dn Known WS=0
Boundary for River Rch & Prof#=Shearstown_Brook,Main            , 17
Up Type= 3
Up Slope=0.0001
Dn Type= 1
Dn Known WS=0
Boundary for River Rch & Prof#=Shearstown_Brook,Main            , 18
Up Type= 3
Up Slope=0.0001
Dn Type= 1
Dn Known WS=0
Boundary for River Rch & Prof#=Shearstown_Brook,Main            , 19
Up Type= 3
Up Slope=0.0001
Dn Type= 1
Dn Known WS=0
Boundary for River Rch & Prof#=Shearstown_Brook,Main            , 20
Up Type= 3
Up Slope=0.0001
Dn Type= 1
Dn Known WS=0
Boundary for River Rch & Prof#=Shearstown_Brook,Main            , 21
Up Type= 3
Up Slope=0.0001
Dn Type= 1
Dn Known WS=0
Boundary for River Rch & Prof#=Shearstown_Brook,Main            , 22
Up Type= 3
Up Slope=0.0001
Dn Type= 1
Dn Known WS=0
Boundary for River Rch & Prof#=Shearstown_Brook,Main            , 23
Up Type= 3
Up Slope=0.0001
Dn Type= 1
Dn Known WS=0
Boundary for River Rch & Prof#=Shearstown_Brook,Main            , 24
Up Type= 3
Up Slope=0.0001
Dn Type= 1
Dn Known WS=0
Boundary for River Rch & Prof#=Shearstown_Brook,Main            , 25
Up Type= 3
Up Slope=0.0001
Dn Type= 1
Dn Known WS=0
Boundary for River Rch & Prof#=Shearstown_Brook,Main            , 26
Up Type= 3
Up Slope=0.0001
Dn Type= 1
Dn Known WS=0
Boundary for River Rch & Prof#=Shearstown_Brook,Main            , 27
Up Type= 3
Up Slope=0.0001
Dn Type= 1
Dn Known WS=0
Boundary for River Rch & Prof#=Shearstown_Brook,Main            , 28
Up Type= 3
Up Slope=0.0001
Dn Type= 1
Dn Known WS=0
Boundary for River Rch & Prof#=Shearstown_Brook,Main            , 29
Up Type= 3
Up Slope=0.0001
Dn Type= 1
Dn Known WS=0
Boundary for River Rch & Prof#=Shearstown_Brook,Main            , 30
Up Type= 3
Up Slope=0.0001
Dn Type= 1
Dn Known WS=0
Boundary for River Rch & Prof#=Shearstown_Brook,Main            , 31
Up Type= 3
Up Slope=0.0001
Dn Type= 1
Dn Known WS=0
Boundary for River Rch & Prof#=Shearstown_Brook,Main            , 32
Up Type= 3
Up Slope=0.0001
Dn Type= 1
Dn Known WS=0
Boundary for River Rch & Prof#=Shearstown_Brook,Main            , 33
Up Type= 3
Up Slope=0.0001
Dn Type= 1
Dn Known WS=0
Boundary for River Rch & Prof#=Shearstown_Brook,Main            , 34
Up Type= 3
Up Slope=0.0001
Dn Type= 1
Dn Known WS=0
Boundary for River Rch & Prof#=Shearstown_Brook,Main            , 35
Up Type= 3
Up Slope=0.0001
Dn Type= 1
Dn Known WS=0
Boundary for River Rch & Prof#=Shearstown_Brook,Main            , 36
Up Type= 3
Up Slope=0.0001
Dn Type= 1
Dn Known WS=0
Boundary for River Rch & Prof#=Shearstown_Brook,Main            , 37
Up Type= 3
Up Slope=0.0001
Dn Type= 1
Dn Known WS=0
Boundary for River Rch & Prof#=Shearstown_Brook,Main            , 38
Up Type= 3
Up Slope=0.0001
Dn Type= 1
Dn Known WS=0
Boundary for River Rch & Prof#=Shearstown_Brook,Main            , 39
Up Type= 3
Up Slope=0.0001
Dn Type= 1
Dn Known WS=0
Boundary for River Rch & Prof#=Shearstown_Brook,Main            , 40
Up Type= 3
Up Slope=0.0001
Dn Type= 1
Dn Known WS=0
Boundary for River Rch & Prof#=Shearstown_Brook,Main            , 41
Up Type= 3
Up Slope=0.0001
Dn Type= 1
Dn Known WS=0
Boundary for River Rch & Prof#=Shearstown_Brook,Main            , 42
Up Type= 3
Up Slope=0.0001
Dn Type= 1
Dn Known WS=0
Boundary for River Rch & Prof#=Shearstown_Brook,Main            , 43
Up Type= 3
Up Slope=0.0001
Dn Type= 1
Dn Known WS=0
Boundary for River Rch & Prof#=Shearstown_Brook,Main            , 44
Up Type= 3
Up Slope=0.0001
Dn Type= 1
Dn Known WS=0
Boundary for River Rch & Prof#=Shearstown_Brook,Main            , 45
Up Type= 3
Up Slope=0.0001
Dn Type= 1
Dn Known WS=0
Boundary for River Rch & Prof#=Shearstown_Brook,Main            , 46
Up Type= 3
Up Slope=0.0001
Dn Type= 1
Dn Known WS=0
Boundary for River Rch & Prof#=Shearstown_Brook,Main            , 47
Up Type= 3
Up Slope=0.0001
Dn Type= 1
Dn Known WS=0
Boundary for River Rch & Prof#=Shearstown_Brook,Main            , 48
Up Type= 3
Up Slope=0.0001
Dn Type= 1
Dn Known WS=0
Boundary for River Rch & Prof#=Shearstown_Brook,Main            , 49
Up Type= 3
Up Slope=0.0001
Dn Type= 1
Dn Known WS=0
Boundary for River Rch & Prof#=Shearstown_Brook,Main            , 50
Up Type= 3
Up Slope=0.0001
Dn Type= 1
Dn Known WS=0
Boundary for River Rch & Prof#=Shearstown_Brook,Main            , 51
Up Type= 3
Up Slope=0.0001
Dn Type= 1
Dn Known WS=0
Boundary for River Rch & Prof#=Shearstown_Brook,Main            , 52
Up Type= 3
Up Slope=0.0001
Dn Type= 1
Dn Known WS=0
Boundary for River Rch & Prof#=Shearstown_Brook,Main            , 53
Up Type= 3
Up Slope=0.0001
Dn Type= 1
Dn Known WS=0
Boundary for River Rch & Prof#=Shearstown_Brook,Main            , 54
Up Type= 3
Up Slope=0.0001
Dn Type= 1
Dn Known WS=0
Boundary for River Rch & Prof#=Shearstown_Brook,Main            , 55
Up Type= 3
Up Slope=0.0001
Dn Type= 1
Dn Known WS=0
Boundary for River Rch & Prof#=Shearstown_Brook,Main            , 56
Up Type= 3
Up Slope=0.0001
Dn Type= 1
Dn Known WS=0
Boundary for River Rch & Prof#=Shearstown_Brook,Main            , 57
Up Type= 3
Up Slope=0.0001
Dn Type= 1
Dn Known WS=0
Boundary for River Rch & Prof#=Shearstown_Brook,Main            , 58
Up Type= 3
Up Slope=0.0001
Dn Type= 1
Dn Known WS=0
Boundary for River Rch & Prof#=Shearstown_Brook,Main            , 59
Up Type= 3
Up Slope=0.0001
Dn Type= 1
Dn Known WS=0
Boundary for River Rch & Prof#=Shearstown_Brook,Main            , 60
Up Type= 3
Up Slope=0.0001
Dn Type= 1
Dn Known WS=0
Boundary for River Rch & Prof#=Shearstown_Brook,Main            , 61
Up Type= 3
Up Slope=0.0001
Dn Type= 1
Dn Known WS=0
Boundary for River Rch & Prof#=Shearstown_Brook,Main            , 62
Up Type= 3
Up Slope=0.0001
Dn Type= 1
Dn Known WS=0
Boundary for River Rch & Prof#=Shearstown_Brook,Main            , 63
Up Type= 3
Up Slope=0.0001
Dn Type= 1
Dn Known WS=0
Boundary for River Rch & Prof#=Shearstown_Brook,Main            , 64
Up Type= 3
Up Slope=0.0001
Dn Type= 1
Dn Known WS=0
Boundary for River Rch & Prof#=Shearstown_Brook,Main            , 65
Up Type= 3
Up Slope=0.0001
Dn Type= 1
Dn Known WS=0
Boundary for River Rch & Prof#=Shearstown_Brook,Main            , 66
Up Type= 3
Up Slope=0.0001
Dn Type= 1
Dn Known WS=0
Boundary for River Rch & Prof#=Shearstown_Brook,Main            , 67
Up Type= 3
Up Slope=0.0001
Dn Type= 1
Dn Known WS=0
Boundary for River Rch & Prof#=Shearstown_Brook,Main            , 68
Up Type= 3
Up Slope=0.0001
Dn Type= 1
Dn Known WS=0
Boundary for River Rch & Prof#=Shearstown_Brook,Main            , 69
Up Type= 3
Up Slope=0.0001
Dn Type= 1
Dn Known WS=0
Boundary for River Rch & Prof#=Shearstown_Brook,Main            , 70
Up Type= 3
Up Slope=0.0001
Dn Type= 1
Dn Known WS=0
Boundary for River Rch & Prof#=Shearstown_Brook,Main            , 71
Up Type= 3
Up Slope=0.0001
Dn Type= 1
Dn Known WS=0
Boundary for River Rch & Prof#=Shearstown_Brook,Main            , 72
Up Type= 3
Up Slope=0.0001
Dn Type= 1
Dn Known WS=0
Boundary for River Rch & Prof#=Shearstown_Brook,Main            , 73
Up Type= 3
Up Slope=0.0001
Dn Type= 1
Dn Known WS=0
Boundary for River Rch & Prof#=Shearstown_Brook,Main            , 74
Up Type= 3
Up Slope=0.0001
Dn Type= 1
Dn Known WS=0
Boundary for River Rch & Prof#=Shearstown_Brook,Main            , 75
Up Type= 3
Up Slope=0.0001
Dn Type= 1
Dn Known WS=0
Boundary for River Rch & Prof#=Shearstown_Brook,Main            , 76
Up Type= 3
Up Slope=0.0001
Dn Type= 1
Dn Known WS=0
Boundary for River Rch & Prof#=Shearstown_Brook,Main            , 77
Up Type= 3
Up Slope=0.0001
Dn Type= 1
Dn Known WS=0
Boundary for River Rch & Prof#=Shearstown_Brook,Main            , 78
Up Type= 3
Up Slope=0.0001
Dn Type= 1
Dn Known WS=0
Boundary for River Rch & Prof#=Shearstown_Brook,Main            , 79
Up Type= 3
Up Slope=0.0001
Dn Type= 1
Dn Known WS=0
Boundary for River Rch & Prof#=Shearstown_Brook,Main            , 80
Up Type= 3
Up Slope=0.0001
Dn Type= 1
Dn Known WS=0
Boundary for River Rch & Prof#=Shearstown_Brook,Main            , 81
Up Type= 3
Up Slope=0.0001
Dn Type= 1
Dn Known WS=0
Boundary for River Rch & Prof#=Shearstown_Brook,Main            , 82
Up Type= 3
Up Slope=0.0001
Dn Type= 1
Dn Known WS=0
Boundary for River Rch & Prof#=Shearstown_Brook,Main            , 83
Up Type= 3
Up Slope=0.0001
Dn Type= 1
Dn Known WS=0
Boundary for River Rch & Prof#=Shearstown_Brook,Main            , 84
Up Type= 3
Up Slope=0.0001
Dn Type= 1
Dn Known WS=0
Boundary for River Rch & Prof#=Shearstown_Brook,Main            , 85
Up Type= 3
Up Slope=0.0001
Dn Type= 1
Dn Known WS=0
Boundary for River Rch & Prof#=Shearstown_Brook,Main            , 86
Up Type= 3
Up Slope=0.0001
Dn Type= 1
Dn Known WS=0
Boundary for River Rch & Prof#=Shearstown_Brook,Main            , 87
Up Type= 3
Up Slope=0.0001
Dn Type= 1
Dn Known WS=0
Boundary for River Rch & Prof#=Shearstown_Brook,Main            , 88
Up Type= 3
Up Slope=0.0001
Dn Type= 1
Dn Known WS=0
Boundary for River Rch & Prof#=Shearstown_Brook,Main            , 89
Up Type= 3
Up Slope=0.0001
Dn Type= 1
Dn Known WS=0
Boundary for River Rch & Prof#=Shearstown_Brook,Main            , 90
Up Type= 3
Up Slope=0.0001
Dn Type= 1
Dn Known WS=0
Boundary for River Rch & Prof#=Shearstown_Brook,Main            , 91
Up Type= 3
Up Slope=0.0001
Dn Type= 1
Dn Known WS=0
Boundary for River Rch & Prof#=Shearstown_Brook,Main            , 92
Up Type= 3
Up Slope=0.0001
Dn Type= 1
Dn Known WS=0
Boundary for River Rch & Prof#=Shearstown_Brook,Main            , 93
Up Type= 3
Up Slope=0.0001
Dn Type= 1
Dn Known WS=0
Boundary for River Rch & Prof#=Shearstown_Brook,Main            , 94
Up Type= 3
Up Slope=0.0001
Dn Type= 1
Dn Known WS=0
Boundary for River Rch & Prof#=Shearstown_Brook,Main            , 95
Up Type= 3
Up Slope=0.0001
Dn Type= 1
Dn Known WS=0
Boundary for River Rch & Prof#=Shearstown_Brook,Main            , 96
Up Type= 3
Up Slope=0.0001
Dn Type= 1
Dn Known WS=0
Boundary for River Rch & Prof#=Shearstown_Brook,Main            , 97
Up Type= 3
Up Slope=0.0001
Dn Type= 1
Dn Known WS=0
Boundary for River Rch & Prof#=Shearstown_Brook,Main            , 98
Up Type= 3
Up Slope=0.0001
Dn Type= 1
Dn Known WS=0
Boundary for River Rch & Prof#=Shearstown_Brook,Main            , 99
Up Type= 3
Up Slope=0.0001
Dn Type= 1
Dn Known WS=0
Boundary for River Rch & Prof#=Shearstown_Brook,Main            , 100
Up Type= 3
Up Slope=0.0001
Dn Type= 1
Dn Known WS=0
DSS Import GetInterval= 0
DSS Import GetPeak= 0
DSS Import FillOption= 0

--- ShearstownModel.f07 (steady flow) ---

Flow Title=Bridge Capacities2
Program Version=4.10
Number of Profiles= 4
Profile Names=PF 1,PF 2,PF 3,PF 4
River Rch & RM=Shearstown_Brook,Main            ,6544.472
    1710    1720    1730    1740
Boundary for River Rch & Prof#=Shearstown_Brook,Main            , 1
Up Type= 3
Up Slope=0.0001
Dn Type= 1
Dn Known WS=0
Boundary for River Rch & Prof#=Shearstown_Brook,Main            , 2
Up Type= 3
Up Slope=0.0001
Dn Type= 1
Dn Known WS=0
Boundary for River Rch & Prof#=Shearstown_Brook,Main            , 3
Up Type= 3
Up Slope=0.0001
Dn Type= 1
Dn Known WS=0
Boundary for River Rch & Prof#=Shearstown_Brook,Main            , 4
Up Type= 3
Up Slope=0.0001
Dn Type= 1
Dn Known WS=0
DSS Import GetInterval= 0
DSS Import GetPeak= 0
DSS Import FillOption= 0

--- ShearstownModel.f08 (steady flow) ---

Flow Title=Mean Annual Flow
Program Version=4.10
Number of Profiles= 1
Profile Names=Mean Annual Flow
River Rch & RM=Shearstown_Brook,Main            ,6544.472
    .689
River Rch & RM=Shearstown_Brook,Main            ,4527.462
    .771
River Rch & RM=Shearstown_Brook,Main            ,4444.284
     .85
River Rch & RM=Shearstown_Brook,Main            ,2846.736
    .967
River Rch & RM=Shearstown_Brook,Main            ,1960.358
   1.032
Boundary for River Rch & Prof#=Shearstown_Brook,Main            , 1
Up Type= 3
Up Slope=0.0001
Dn Type= 1
Dn Known WS=0
Observed WS=Shearstown_Brook,Main            ,6544.472,,22.44,,,22.64184,
Observed WS=Shearstown_Brook,Main            ,6184.978,,20.67,,,20.95005,
Observed WS=Shearstown_Brook,Main            ,5752.960,,19.87,,,20.16745,21.49
Observed WS=Shearstown_Brook,Main            ,5345.828,,19.47,,,19.88958,
Observed WS=Shearstown_Brook,Main            ,5247.149,,18.89,,,19.191,19.98
Observed WS=Shearstown_Brook,Main            ,5117.344,,17.35,,,17.62281,
Observed WS=Shearstown_Brook,Main            ,5029.134,,16.91,,17.412,,
Observed WS=Shearstown_Brook,Main            ,4990.436,,16.67,,,17.42075,
Observed WS=Shearstown_Brook,Main            ,4773.842,,16.85,,17.25839,,
Observed WS=Shearstown_Brook,Main            ,4650.722,,16.56,,16.79436,,
Observed WS=Shearstown_Brook,Main            ,4527.462,,15.8,,16.056,,
Observed WS=Shearstown_Brook,Main            ,4495.201,,15.51,,15.80389,,
Observed WS=Shearstown_Brook,Main            ,4476.356,,15.53,,15.79571,,
Observed WS=Shearstown_Brook,Main            ,4444.284,,15.64,,15.78496,,
Observed WS=Shearstown_Brook,Main            ,4338.646,,15.15,,15.25665,,
Observed WS=Shearstown_Brook,Main            ,4224.649,,14.55,,14.93124,,
Observed WS=Shearstown_Brook,Main            ,4113.600,,14.03,,14.21454,,
Observed WS=Shearstown_Brook,Main            ,4031.147,,13.36,,13.51369,,
Observed WS=Shearstown_Brook,Main            ,3923.947,,12.95,,13.05725,,
Observed WS=Shearstown_Brook,Main            ,3746.619,,11.64,,11.86337,,
Observed WS=Shearstown_Brook,Main            ,3558.752,,10.39,,10.68238,,
Observed WS=Shearstown_Brook,Main            ,3332.329,,9.2,,9.3757,,
Observed WS=Shearstown_Brook,Main            ,3046.631,,6.91,,7.164453,,
Observed WS=Shearstown_Brook,Main            ,2940.559,,5.54,,5.730798,,
Observed WS=Shearstown_Brook,Main            ,2917.845,,5.42,,5.709237,,
Observed WS=Shearstown_Brook,Main            ,2905.134,,5.48,,5.705289,,
Observed WS=Shearstown_Brook,Main            ,2885.103,,5.44,,,,
Observed WS=Shearstown_Brook,Main            ,2876.564,,5.4,,,,
Observed WS=Shearstown_Brook,Main            ,2846.736,,5.36,,5.740744,,
Observed WS=Shearstown_Brook,Main            ,2697.410,,4.28,,4.51613,,5.32
Observed WS=Shearstown_Brook,Main            ,2581.398,,3.28,,3.487967,,
Observed WS=Shearstown_Brook,Main            ,2472.819,,2.41,,2.629684,,
Observed WS=Shearstown_Brook,Main            ,2341.402,,1.45,,1.742887,,
Observed WS=Shearstown_Brook,Main            ,2240.664,,0.64,,0.9175265,,
Observed WS=Shearstown_Brook,Main            ,2138.891,,0.11,,0.143711,,2.45
Observed WS=Shearstown_Brook,Main            ,2107.745,,0.13,,0.093424,,
Observed WS=Shearstown_Brook,Main            ,2090.583,,0.02,,0.086,,
Observed WS=Shearstown_Brook,Main            ,2065.870,,0.11,,0.0466685,,
Observed WS=Shearstown_Brook,Main            ,1960.358,,-0.04,0.173169,,,
Observed WS=Shearstown_Brook,Main            ,1814.866,,0.04,0.186096,,,
Observed WS=Shearstown_Brook,Main            ,1545.071,,-0.16,0.297354,,,
Observed WS=Shearstown_Brook,Main            ,1156.731,,0.05,0.3445445,,,1.16
Observed WS=Shearstown_Brook,Main            ,735.6188,,-0.02,0.3686195,,,
Observed WS=Shearstown_Brook,Main            ,519.9265,,-0.23,0.3906197,,,
Observed WS=Shearstown_Brook,Main            ,443.9145,,0.01,,0.1758075,,
Observed WS=Shearstown_Brook,Main            ,426.8590,,0.03,,0.1408295,,
Observed WS=Shearstown_Brook,Main            ,377.6255,,-0.24,0.305459,,,1.03
Observed WS=Shearstown_Brook,Main            ,310.9396,,-0.14,,-0.0247275,,
Observed WS=Shearstown_Brook,Main            ,280.4603,,-0.46,,0.019482,,
Observed WS=Shearstown_Brook,Main            ,130.9306,,-0.18,0.16216,,,
Observed WS=Shearstown_Brook,Main            ,95.07389,,-0.25,,0.043064,,
Observed WS=Shearstown_Brook,Main            ,72.16455,,-0.3,,0.104541,,
Observed WS=Shearstown_Brook,Main            ,43.48671,,,,,,
DSS Import GetInterval= 0
DSS Import GetPeak= 0
DSS Import FillOption= 0

--- ShearstownModel.g01 (geometry) ---

Geom Title=Shearstown_Aug3,11
Program Version=4.10

River Reach=Shearstown_Brook,Main
Reach XY= 30
279687.1378184375269448.11201035279898.4988778835269663.76544955
 279984.536716895269841.61978838280270.4734156715269931.72409242
280268.1191464465270008.98692794280051.9544265575270107.01013755
280031.6934429125270249.80013322280100.1812749535270398.47580194
280217.7520532965270439.28313521 280324.535998095270583.67831443
280512.0214383095270698.39543311280738.316650021 5270978.1967636
280898.9206161615270997.74433233281034.9688408585271096.87333506
281034.849938371 5271212.3395394281152.0402287565271269.41273276
 281330.108592075271517.11039199281680.9184873165271618.51043221
 281770.238034945271765.90195408281796.2063379235271946.72885508
281989.494219469 5272087.6996427282129.8942751575272092.26549817
282139.7869620085272198.80212579282249.7479812335272316.37290413
282439.7523926425272382.55667022282622.837560113   5272530.46784
282909.6409259055272953.90865836283051.8400789665273038.08574686
283617.9309990795273033.83931337283645.8713010965273254.68243257

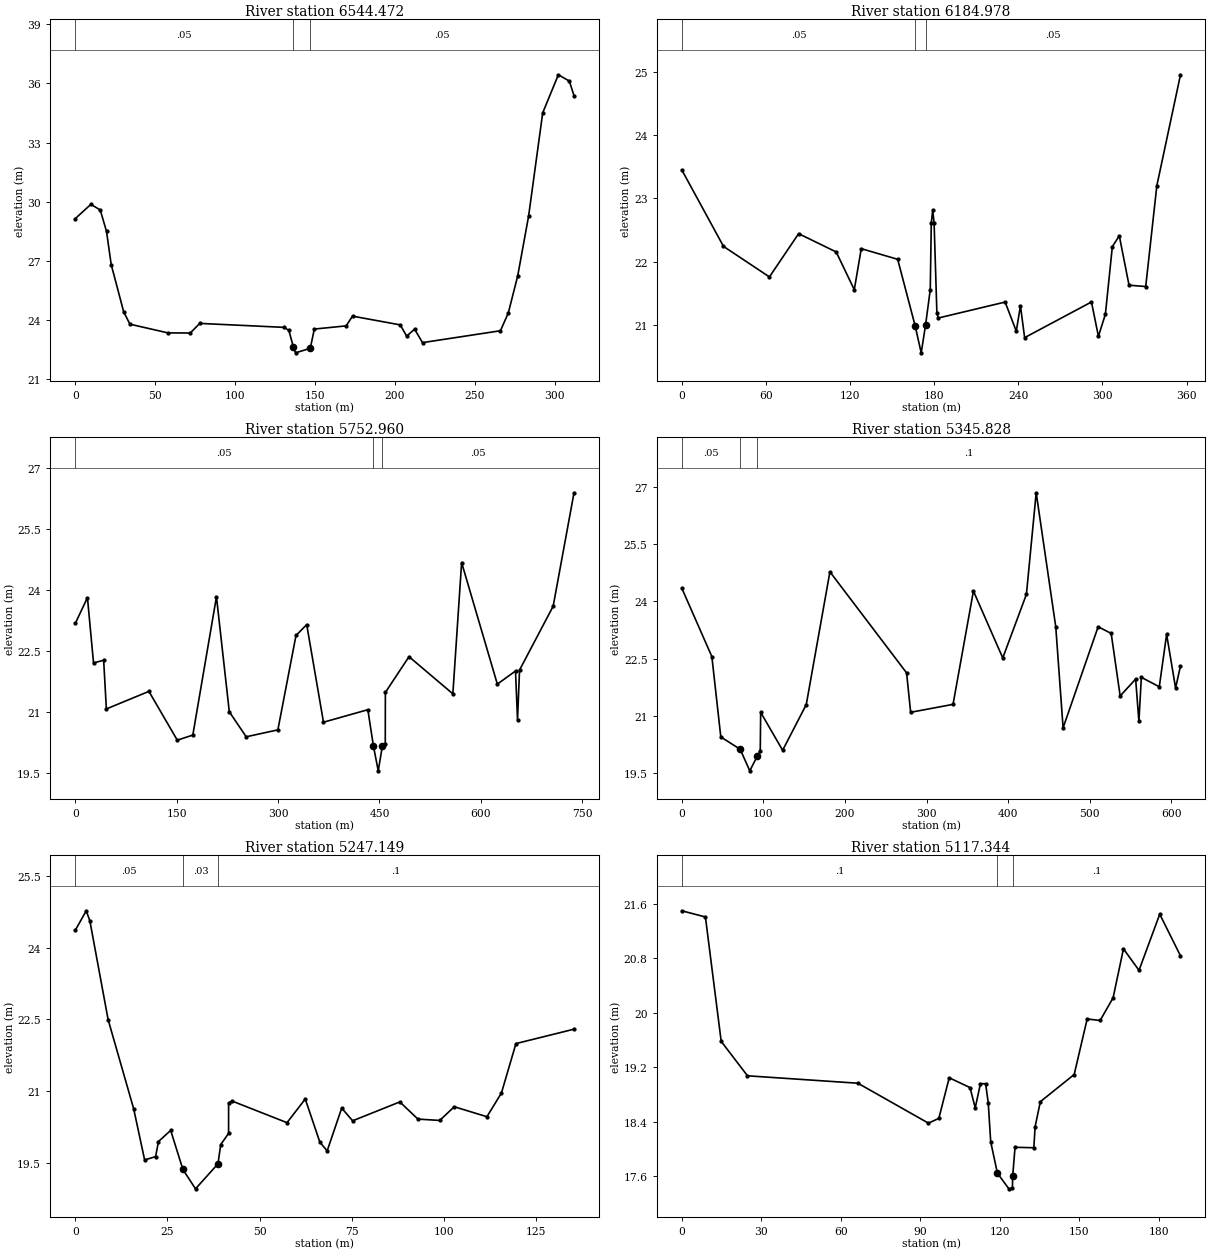
Type RM Length L Ch R = 1 ,6544.472,23.97,23.97,23.97
Node Photo=..\Cross Section Photographs\2.JPG
BEGIN DESCRIPTION:
Section 2
END DESCRIPTION:
Node Name=2
XS GIS Cut Line= 4
279642.8886158175269616.29250684279676.2254208965269594.05736596
279865.5728973935269474.22258917279906.754524344 5269449.5598458
#Sta/Elev= 30
       0  29.145   9.774  29.868  15.638  29.579  19.547  28.491  22.479  26.816
  30.298  24.414  34.208  23.792  57.998  23.351  71.941  23.345  77.917  23.832
   130.7  23.631 133.688  23.474   136.5  22.635  137.91   22.34  147.09  22.572
 149.623  23.545 169.542  23.707 173.525    24.2 203.403  23.757 207.387  23.186
 212.366   23.54 217.346  22.858 266.114   23.46 271.012  24.358  276.89   26.23
 283.747  29.278 292.564  34.506 302.361  36.434 309.218  36.116 312.157  35.377
#Mann= 3 , 0 , 0
       0     .05       0   136.5    .035       0  147.09     .05       0
Bank Sta=136.5,147.09
XS Rating Curve= 0 ,0
Exp/Cntr=0.3,0.1

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
Type RM Length L Ch R = 1 ,6184.978,24,24,24
Node Photo=..\Cross Section Photographs\3.JPG
BEGIN DESCRIPTION:
Section 3
END DESCRIPTION:
Node Name=3
XS GIS Cut Line= 5
 279820.72889364 5269887.8296174279934.1476008725269832.90339471
 279984.689044135269804.58392651280069.3762310125269709.81074358
280098.4158214875269675.93122135
#Sta/Elev= 30
       0  23.448  29.768  22.239  62.513  21.757  83.351   22.44 110.142  22.151
 123.042  21.555 128.016  22.203 153.987  22.035  166.4720.98214 170.769  20.558
  173.8720.99633 177.219  21.555  177.96  22.608 178.959  22.807 179.958  22.614
 181.955  21.184 182.954  21.108 230.622   21.36 238.565    20.9 241.544    21.3
 244.523  20.798 292.185  21.361 297.149  20.819 302.114  21.167 307.079  22.235
 312.042  22.406 318.984  21.626 330.883  21.605 338.816  23.198 355.673  24.949
#Mann= 3 , 0 , 0
       0     .05       0  166.47     .03       0  173.87     .05       0
Bank Sta=166.47,173.87
XS Rating Curve= 0 ,0
Exp/Cntr=0.3,0.1

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
Type RM Length L Ch R = 1 ,5752.960,23.95,23.95,23.95
Node Photo=..\Cross Section Photographs\4.JPG
BEGIN DESCRIPTION:
Section 4
END DESCRIPTION:
Node Name=4
XS GIS Cut Line= 6
279864.7088621385269962.89535559280148.460317394 5269914.7111462
280225.7080181515269946.06912374280258.8978504125270033.83840265
280291.7523945065270077.91709703280468.1728860055269961.66313154
#Sta/Elev= 30
       0  23.177  17.988  23.809  26.983  22.207  41.973  22.272   45.97  21.077
 108.929  21.508 150.902   20.31 173.888  20.435 208.865   23.83 227.853  21.008
 252.837  20.393 299.724  20.563 326.522   22.88 342.402  23.147 367.214  20.751
  432.86  21.058  440.9720.17692 448.221  19.557  454.24  20.157 458.619  20.216
 458.778  21.482 493.732   22.36  558.62  21.448 571.581   24.67 624.423  21.686
 651.306  22.008 654.291  20.805 657.276  22.031 707.025  23.599  737.87  26.384
#Mann= 3 , 0 , 0
       0     .05       0  440.97    .035       0  454.24     .05       0
Bank Sta=440.97,454.24
XS Rating Curve= 0 ,0
Exp/Cntr=0.3,0.1

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
Type RM Length L Ch R = 1 ,5345.828,24.67,24.67,24.67
Node Photo=..\Cross Section Photographs\5.JPG
BEGIN DESCRIPTION:
Section 5
END DESCRIPTION:
Node Name=5
XS GIS Cut Line= 5
279949.9376922285270261.38038633279992.9928032745270252.93819582
280078.9236277615270235.18545406 280243.823128035270203.54021435
 280514.572495045270049.04481284
#Sta/Elev= 30
       0  24.345  36.895  22.551  47.863  20.448   71.5720.12595  83.392  19.561
    92.719.95229  96.207  20.083  96.722  21.092 123.644  20.099 152.609  21.295
 181.593   24.77 275.541  22.126 280.539  21.093 332.499  21.301 357.477  24.267
 393.445  22.516 422.419   24.18 434.409  26.839 458.387  23.333  467.38  20.687
 510.341  23.332 526.328  23.158 537.318  21.521 556.302  21.962 560.299  20.856
 563.296  22.009 585.277  21.761  594.27  23.134  605.26  21.728 611.255  22.307
#Mann= 3 , 0 , 0
       0     .05       0   71.57    .035       0    92.7      .1       0
Bank Sta=71.57,92.7
XS Rating Curve= 0 ,0
Exp/Cntr=0.3,0.1

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
Type RM Length L Ch R = 1 ,5247.149,21.63,21.63,21.63
Node Photo=..\Cross Section Photographs\6.JPG
BEGIN DESCRIPTION:
Section 6
END DESCRIPTION:
Node Name=6
XS GIS Cut Line= 3
280032.4970469815270351.86658041280096.3958268435270322.49029571
280154.3381677475270293.02517464
#Sta/Elev= 30
       0  24.371   2.972  24.779   3.962  24.565   8.915  22.495  15.849  20.626
   18.82  19.555  21.792  19.626  22.573  19.942  25.887  20.175    29.2  19.356
  32.621   18.95   38.7219.47467  39.468  19.879  41.597  20.112  41.602  20.749
  42.593  20.789  57.451  20.337  62.404  20.833  66.366  19.928  68.347  19.745
  72.298  20.643  75.253  20.376  88.056  20.772  92.981  20.412   98.89  20.384
  102.83  20.671 111.694  20.462 115.634  20.958 119.573  21.995 135.332  22.297
#Mann= 3 , 0 , 0
       0     .05       0    29.2     .03       0   38.72      .1       0
Bank Sta=29.2,38.72
XS Rating Curve= 0 ,0
Exp/Cntr=0.3,0.1

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
Type RM Length L Ch R = 1 ,5117.344,22.05,22.05,22.05
Node Photo=..\Cross Section Photographs\7.JPG
BEGIN DESCRIPTION:
Section 7
END DESCRIPTION:
Node Name=7
XS GIS Cut Line= 5
280072.2465517615270501.69594384280128.3868047095270449.91716011
280150.1082838745270423.33692903280165.4760816075270388.23960006
280179.8961941525270351.88511824
#Sta/Elev= 30
       0  21.499   8.927  21.408  14.878  19.582  24.796  19.077  66.454  18.968
  93.046  18.382  96.969  18.452 100.892  19.048 108.738  18.904 110.699  18.606
 112.664  18.961 114.629  18.961 115.612  18.678 116.543  18.107  119.0717.64742
 123.405  17.418 124.732  17.423  124.8217.60086  125.72  18.028 132.809  18.021
 133.295   18.33  135.26  18.697 148.031  19.096 152.925  19.911 157.814  19.889
 162.702  20.221 166.613   20.94  172.48  20.625 180.302  21.449 188.124  20.838
#Mann= 3 , 0 , 0
       0      .1       0  119.07     .03       0  124.82      .1       0
Bank Sta=119.07,124.82
XS Rating Curve= 0 ,0
Exp/Cntr=0.3,0.1

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
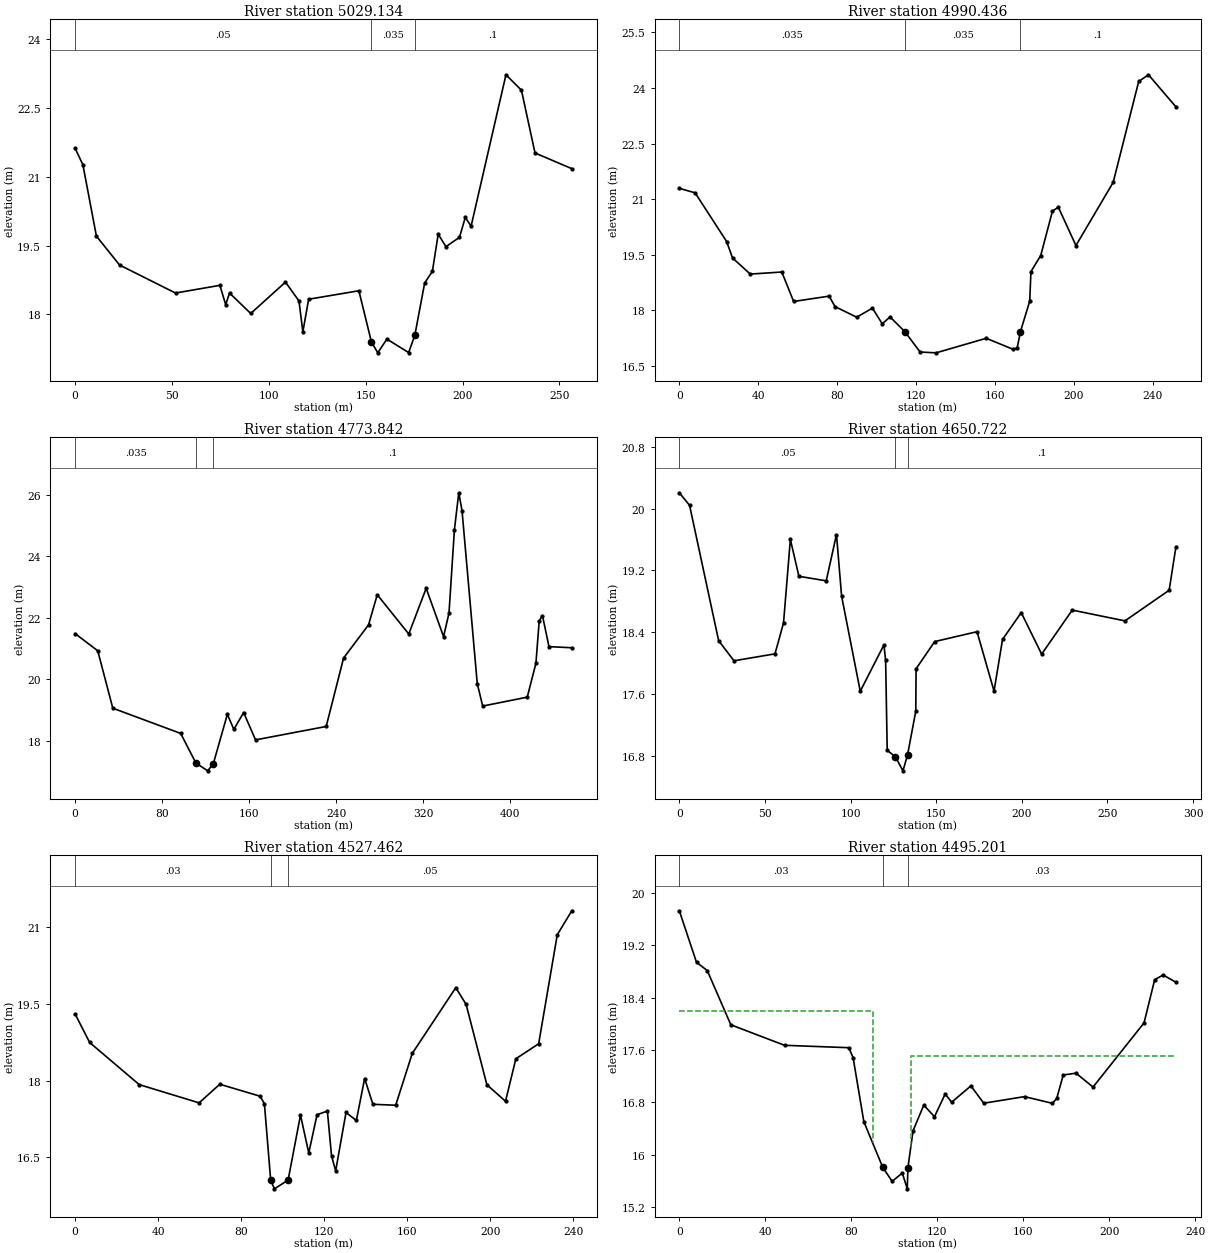
Type RM Length L Ch R = 1 ,5029.134,19.35,19.35,19.35
Node Photo=..\Cross Section Photographs\8.JPG
BEGIN DESCRIPTION:
Section 8
END DESCRIPTION:
Node Name=8
XS GIS Cut Line= 4
280103.1743131415270545.55409078280212.9905607145270469.68944225
280263.4532035485270422.73641931280296.3413668275270379.92087102
#Sta/Elev= 30
       0  21.614   3.984  21.255  10.957  19.705   22.91  19.076  51.795  18.467
  74.705  18.634  77.693  18.214  79.685  18.467  90.642  18.022 108.571  18.705
 115.544  18.294 117.536  17.622 120.524  18.332  146.46  18.516  152.9317.40534
 156.211  17.166 160.931  17.465 172.148  17.172  175.3417.54627 180.424  18.684
  184.42   18.94 187.417  19.746 191.413  19.476 198.406  19.678 201.403  20.112
 204.401  19.921 222.398  23.214 230.396  22.878 237.395  21.513 256.391  21.172
#Mann= 3 , 0 , 0
       0     .05       0  152.93    .035       0  175.34      .1       0
Bank Sta=152.93,175.34
XS Rating Curve= 0 ,0
Exp/Cntr=0.3,0.1

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
Type RM Length L Ch R = 1 ,4990.436,24.07,24.07,24.07
Node Photo=..\Cross Section Photographs\9.JPG
BEGIN DESCRIPTION:
Section 9
END DESCRIPTION:
Node Name=9
XS GIS Cut Line= 4
 280134.58009247  5270568.355547280212.2964044955270512.21838797
280299.5517162145270448.43891012280332.9097400215270414.33816344
#Sta/Elev= 30
       0  21.289   7.989  21.168  23.968  19.852  26.964  19.407  35.952  18.973
   51.93  19.028  57.922  18.233  75.898  18.377  78.894  18.094  89.879  17.808
  97.854  18.053 102.812   17.63 106.778  17.815  114.2217.42065 122.017  16.867
 130.084  16.845 155.522  17.238 169.129  16.941 171.187  16.976  172.8717.42072
 177.561  18.243  178.17   19.04 183.128  19.474 189.078  20.674 192.052   20.78
 200.976  19.744 219.852  21.451 232.772  24.176 237.741  24.357 251.654  23.489
#Mann= 3 , 0 , 0
       0    .035       0  114.22    .035       0  172.87      .1       0
Bank Sta=114.22,172.87
XS Rating Curve= 0 ,0
Exp/Cntr=0.3,0.1

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
Type RM Length L Ch R = 1 ,4773.842,24.62,24.62,24.62
Node Photo=..\Cross Section Photographs\10.JPG
BEGIN DESCRIPTION:
Section 10
END DESCRIPTION:
Node Name=10
XS GIS Cut Line= 4
280316.8324029625270732.46707628280370.6936636935270671.92322421
280426.127656044  5270600.035326 280593.190513925270369.42837701
#Sta/Elev= 30
       0  21.481  20.753  20.923  34.588  19.054  96.996  18.232  110.9717.26892
 121.828  17.014  126.9917.24531 139.891  18.852 145.876  18.365 154.855  18.913
 165.828  18.022 230.764  18.459  246.75  20.686 269.731  21.769 277.725  22.748
 306.701  21.469 322.688  22.958 338.674  21.384  343.67  22.151 348.666  24.871
 352.663  26.068  355.66  25.485 369.649  19.856 374.645  19.123 415.611  19.413
 423.604  20.518 426.602  21.897 429.599  22.069 435.595  21.058 456.577  21.022
#Mann= 3 , 0 , 0
       0    .035       0  110.97    .035       0  126.99      .1       0
Bank Sta=110.97,126.99
XS Rating Curve= 0 ,0
Exp/Cntr=0.3,0.1

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
Type RM Length L Ch R = 1 ,4650.722,24.65,24.65,24.65
Node Photo=..\Cross Section Photographs\11.JPG
BEGIN DESCRIPTION:
Section 11
END DESCRIPTION:
Node Name=11
XS GIS Cut Line= 4
280408.6755851325270777.49636719280481.7863438195270714.11417964
280536.1377770565270665.19788972280623.7836627355270583.03866504
#Sta/Elev= 30
       0  20.205   5.985  20.042  22.943  18.289  31.921  18.028  55.861  18.118
  60.849  18.519  64.839  19.601  69.827  19.123  85.787  19.064  91.772  19.664
  94.765  18.865 105.653  17.633 119.487  18.234 120.475  18.032   121.4  16.867
  126.1916.78418 130.588  16.602  133.2516.80567 138.071  17.375 138.262  17.925
 149.132  18.277 173.854  18.405 183.782  17.635 188.746  18.305 199.667  18.652
 211.581  18.114 229.452  18.685  260.23  18.545 286.044  18.942 290.015  19.506
#Mann= 3 , 0 , 0
       0     .05       0  126.19    .035       0  133.25      .1       0
Bank Sta=126.19,133.25
XS Rating Curve= 0 ,0
Exp/Cntr=0.3,0.1

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
Type RM Length L Ch R = 1 ,4527.462,16.13,16.13,16.13
Node Photo=..\Cross Section Photographs\12.JPG
BEGIN DESCRIPTION:
Section 12
END DESCRIPTION:
Node Name=12
XS GIS Cut Line= 4
280469.4936318965270843.45930345280521.2268582815270815.69005693
280595.2157189425270774.37960973280672.1732427935270717.26256459
#Sta/Elev= 30
       0  19.299   6.966  18.744   30.85  17.921  59.712  17.564  69.681  17.928
  89.036  17.695  91.167   17.55    94.2 16.0559  95.987  15.884   102.6  16.055
 108.562  17.326  112.55  16.584 116.538  17.333 121.522  17.403 123.516  16.531
  125.51  16.234 130.495  17.376  135.48   17.22 139.467   18.04 143.455  17.536
 154.437  17.518 162.423  18.531 183.387  19.815 188.379  19.487 198.362  17.919
 207.347  17.595 212.338  18.426  223.32  18.719 232.304  20.851 239.293  21.318
#Mann= 3 , 0 , 0
       0     .03       0    94.2     .03       0   102.6     .05       0
Bank Sta=94.2,102.6
XS Rating Curve= 0 ,0
Exp/Cntr=0.3,0.1

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
Type RM Length L Ch R = 1 ,4495.201,18.84,18.84,18.84
Node Photo=..\Cross Section Photographs\13.JPG
BEGIN DESCRIPTION:
Section 13
END DESCRIPTION:
Node Name=13
XS GIS Cut Line= 6
280485.8752244425270858.99914381280549.1776164115270829.36424114
 280591.957136425270816.00868368280628.5758623975270811.57395387
280658.3066750095270807.68587123 280701.222311025270783.11379422
#Sta/Elev= 30
       0  19.725   7.988  18.938  12.981  18.812  23.964  17.983  48.927   17.67
  78.859  17.633  80.851   17.48   85.83  16.504   94.6615.80346  98.996  15.592
 103.731  15.718 106.042  15.477  106.3515.80235 108.736  16.365 113.716  16.756
 118.699  16.579 123.684  16.926 126.675    16.8 135.647   17.05 141.629  16.785
 160.593  16.886 173.586  16.783 175.585  16.859 178.584  17.216 184.549  17.244
 192.462  17.032 216.199  18.013 221.144  18.673   225.1  18.744 231.034  18.633
#Mann= 3 , 0 , 0
       0     .03       0   94.66     .03       0  106.35     .03       0
#XS Ineff= 2 , 0
       0    89.9    18.2   107.7       0    17.5
Permanent Ineff=
       F       F
Bank Sta=94.66,106.35
XS Rating Curve= 0 ,0
Exp/Cntr=0.5,0.3