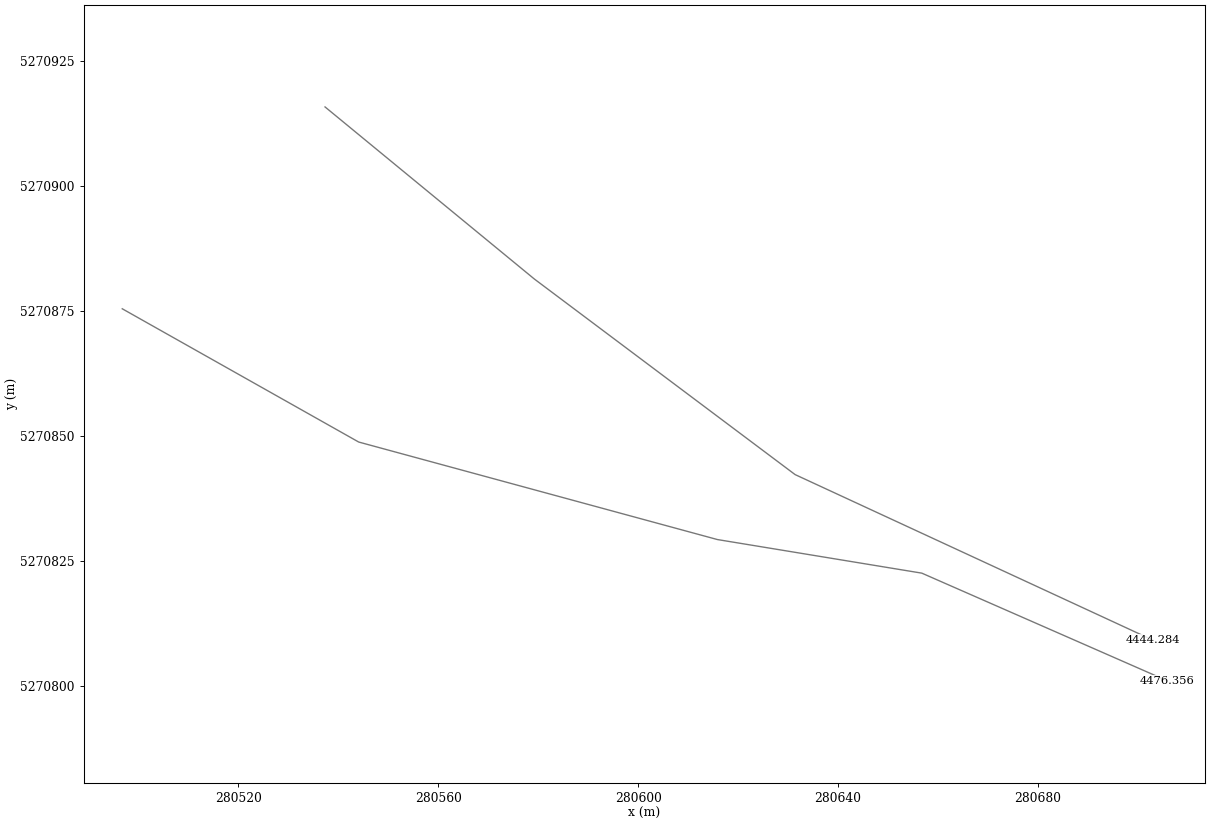
HEC-RAS study ShearstownModel.prj: Shearstown Model

--- ShearstownModel.g01 (geometry) --- (continued)

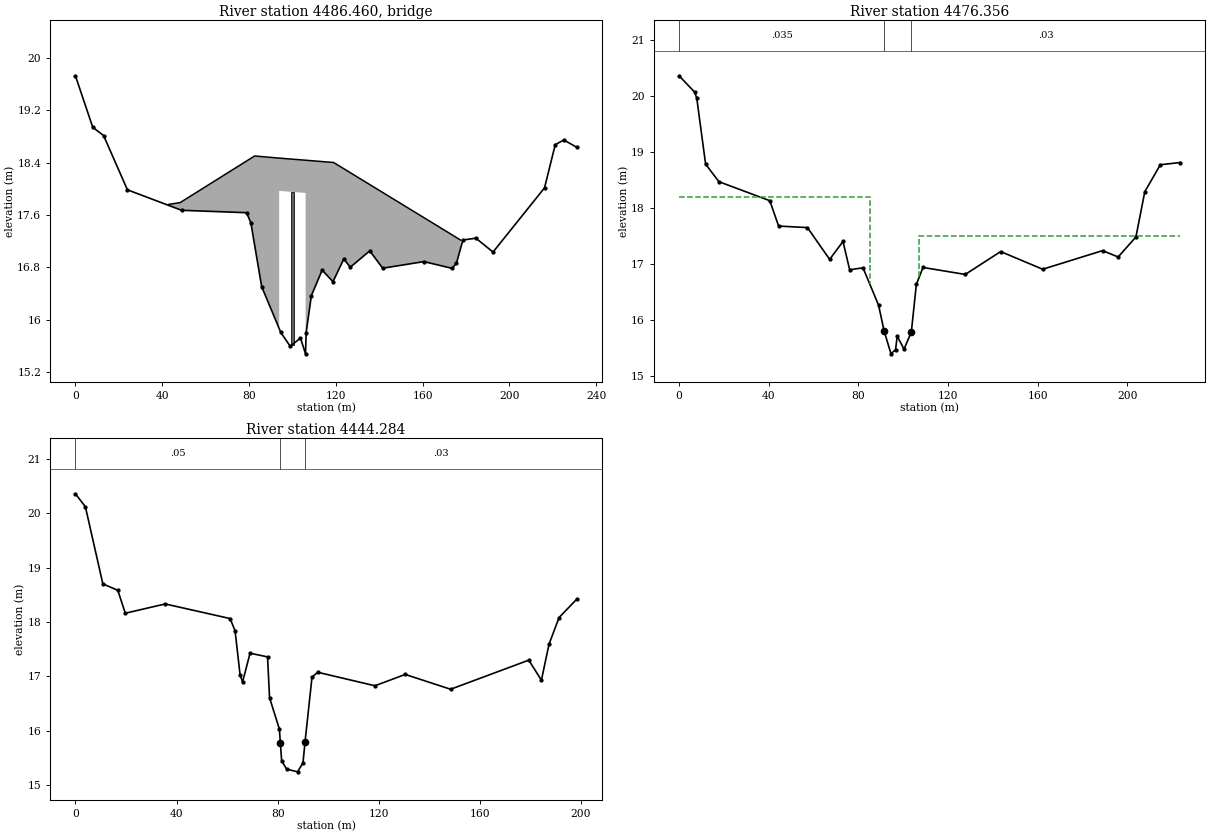
Type RM Length L Ch R = 3 ,4486.460,,,
BEGIN DESCRIPTION:
Butlerville Bridge
END DESCRIPTION:
Node Name=Bridge13,14
Bridge Culvert--1,0,-1,-1, 0
Deck Dist Width WeirC Skew NumUp NumDn MinLoCord MaxHiCord MaxSubmerge Is_Ogee
4.55,9.8,1.4,0, 9, 10, , , 0.98, 0, 0,0,,
   42.94  48.229    82.6    93.9    93.9   106.1   106.1     119 177.539
   17.76  17.787    18.5  18.467  18.467  18.435  18.435    18.4  17.215
      15      15      15      15  17.967  17.935      15      15      15
  43.249  53.183    79.5    91.4    91.4   103.6   103.6     114 161.797 187.225
  17.793  17.794    18.5  18.466  18.466   18.43   18.43    18.4  17.168  17.179
      15      15      15      15  17.966  17.937      15      15      15      15
Pier Skew, UpSta & Num, DnSta & Num=  ,100, 2 ,97.5, 2 , 0 , 0 , 0 ,,
     1.2     1.2
      15    18.1
     1.2     1.2
      15    18.1
BR Coef=-1 , 0 , 0 ,, 0 ,,,0.8,0,,0,
WSPro=,,,, 1 ,,,, 0 ,,,, 0 ,,,,-1 ,-1 ,-1 , 0 , 0 , 0 , 0 , 0
BC Design=,, 0 ,, 0 ,,,,,,
BC Use User HTab Curves=0
BC User HTab FreeFlow(D)= 0

Type RM Length L Ch R = 1 ,4476.356,16.03,16.03,16.03
Node Photo=..\Cross Section Photographs\14.JPG
BEGIN DESCRIPTION:
Section 14
END DESCRIPTION:
Node Name=14
XS GIS Cut Line= 5
280496.7358473435270875.45409125280544.0596244165270848.78068963
280615.8615535035270829.26105511280656.7762570795270822.53750416
280705.820898775 5270801.0266964
#Sta/Elev= 30
       0  20.369   6.914  20.079   7.902   19.97  11.852  18.789  17.779  18.475
  40.495  18.135  44.446  17.681  57.299  17.654  67.221  17.085  73.173  17.406
  76.149  16.899  82.102  16.935  89.047  16.267   91.5415.80334   94.59  15.396
  96.654  15.471  97.364  15.713  100.41  15.479  103.6815.78834 105.913  16.637
 108.889  16.941 127.739  16.816 143.539  17.225 162.297  16.909 189.038  17.242
  195.98  17.128 203.914  17.486 207.881  18.296 214.823  18.778 223.749  18.818
#Mann= 3 , 0 , 0
       0    .035       0   91.54     .03       0  103.68     .03       0
#XS Ineff= 2 , 0
       0    85.1    18.2   107.2       0    17.5
Permanent Ineff=
       F       F
Bank Sta=91.54,103.68
XS Rating Curve= 0 ,0
Exp/Cntr=0.5,0.3

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
Type RM Length L Ch R = 1 ,4444.284,21.13,21.13,21.13
Node Photo=..\Cross Section Photographs\15.JPG
BEGIN DESCRIPTION:
Section 15
END DESCRIPTION:
Node Name=15
XS GIS Cut Line= 4
280537.3243790355270915.85512201280579.2393628745270881.39637454
280631.4159781775270842.26391306280702.9575987895270809.16151552
#Sta/Elev= 30
       0   20.36   3.946  20.121  10.852  18.701  16.772  18.582  19.731   18.16
  35.516  18.331  61.178  18.062  63.155  17.838  65.131  17.028  66.119  16.893
  69.084  17.424  76.001  17.356  76.806  16.602  80.673  16.028   81.0815.76939
   81.58  15.444  83.523   15.29  87.885  15.239  90.019  15.404   90.8515.79611
  93.588  16.981  95.823  17.073 118.493  16.824 130.458  17.033 148.419   16.76
 179.352  17.296 184.341  16.926 187.334  17.586 191.326  18.081  198.31  18.418
#Mann= 3 , 0 , 0
       0     .05       0   81.08     .03       0   90.85     .03       0
Bank Sta=81.08,90.85
XS Rating Curve= 0 ,0
Exp/Cntr=0.3,0.1