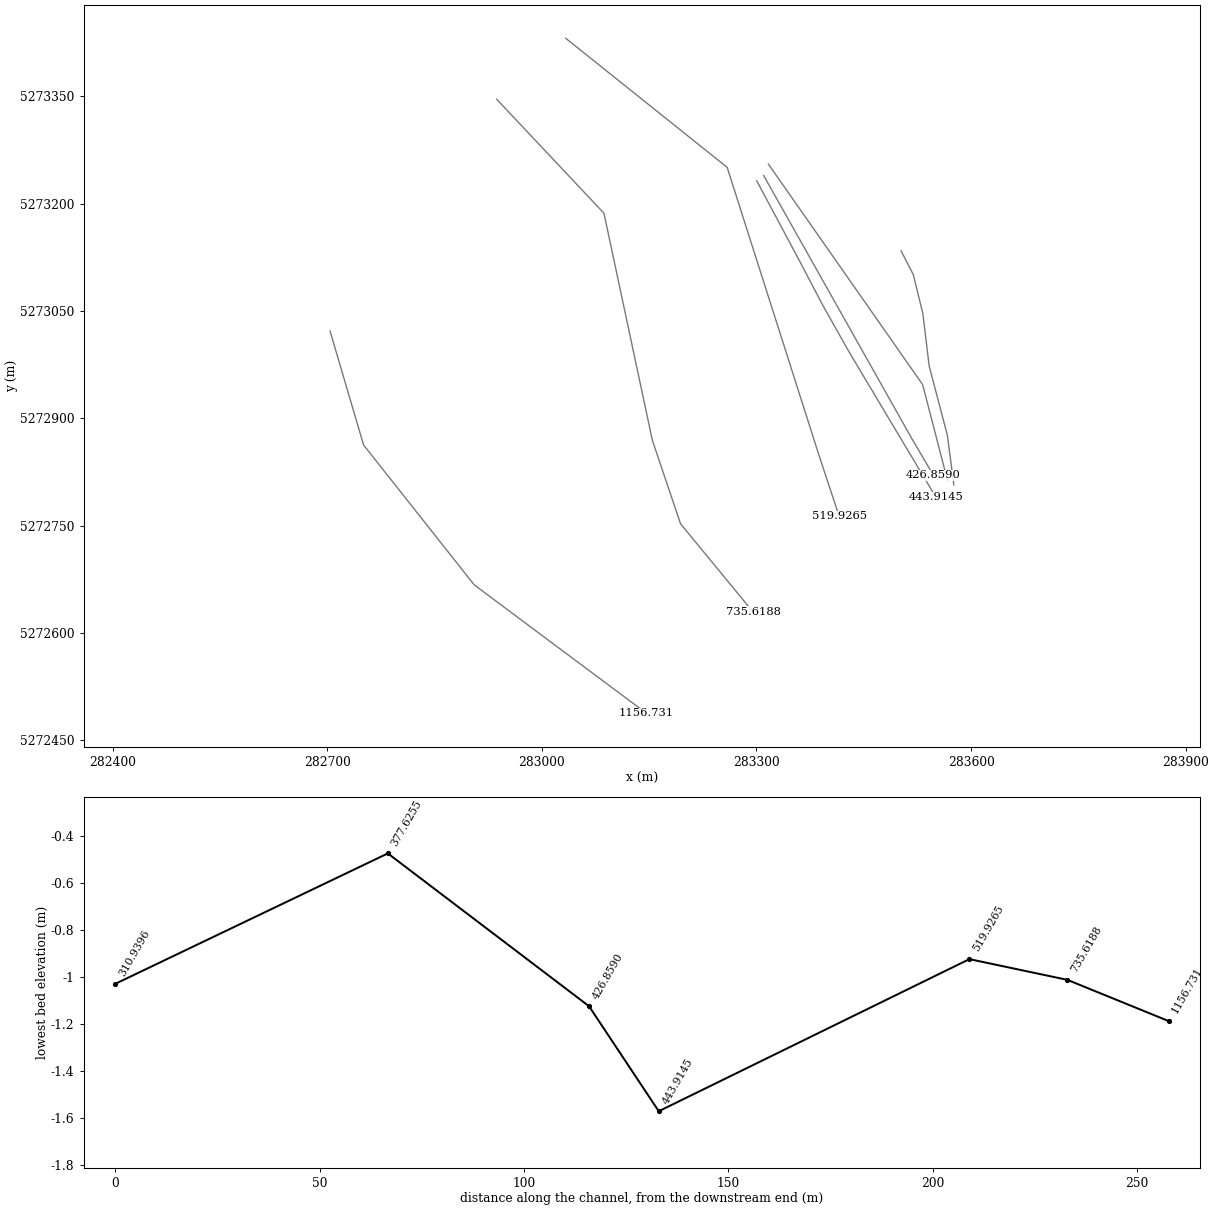
HEC-RAS study ShearstownModel.prj: Shearstown Model

--- ShearstownModel.g01 (geometry) --- (continued)

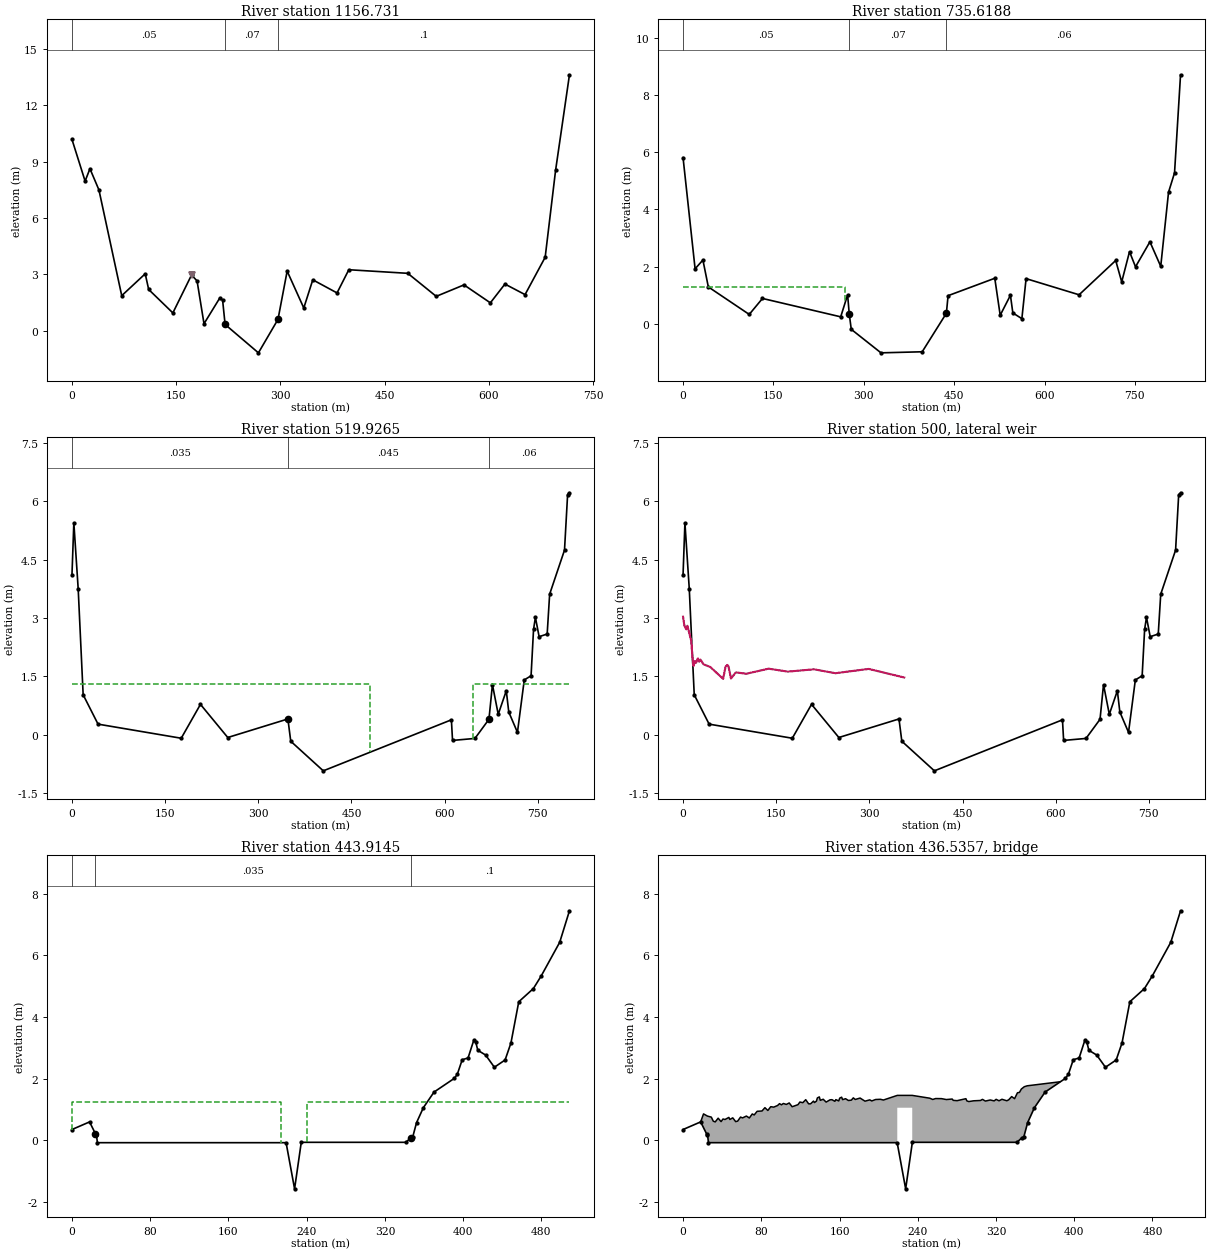
Type RM Length L Ch R = 1 ,1156.731,24.77,24.77,24.77
Node Photo=..\Cross Section Photographs\43.JPG
BEGIN DESCRIPTION:
Section 43
END DESCRIPTION:
Node Name=43
XS GIS Cut Line= 4
282704.0342084265273021.90289057 282750.881721345272862.62134666
282905.4855401995272667.13056745283146.3838473515272487.49095268
#Sta/Elev= 30
       0  10.177  18.889   7.957  25.849   8.618  38.773    7.49  71.581   1.857
 105.383   3.022 110.354   2.186  145.15    .938  172.01   2.957 179.985   2.644
 189.955    .362 212.297   1.711  216.69   1.629  220.32    .323 268.251  -1.188
  296.41.5946554 309.589   3.165 333.515   1.201 346.476   2.701 381.369   2.003
 398.317   3.238 483.153   3.047 524.086    1.82  564.02   2.431 601.957   1.475
 622.922   2.475 651.875   1.913 680.827   3.903 695.802    8.53 715.769  13.621
#Mann= 3 , 0 , 0
       0     .05       0  220.32     .07       0  296.41      .1       0
Levee=-1,172.01,2.96,0,,,,
Bank Sta=220.32,296.41
XS Rating Curve= 0 ,0
Exp/Cntr=0.3,0.1

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
Type RM Length L Ch R = 1 ,735.6188,23.97,23.97,23.97
Node Photo=..\Cross Section Photographs\44.JPG
BEGIN DESCRIPTION:
Section 44
END DESCRIPTION:
Node Name=44
XS GIS Cut Line= 5
282936.9332726415273345.81997989283086.8453139775273186.53843598
283154.5526840875272868.97747977283193.8805513565272752.50690277
283295.1372609955272629.32863744
#Sta/Elev= 30
       0   5.805  19.976   1.923   32.96   2.229  41.949    1.29 109.866    .329
 131.839    .887 261.693    .245 273.157   1.015  275.82.3542499  279.23   -.192
  328.57  -1.013 396.976   -.976  437.12.3708771 439.923    .984 517.459   1.592
  526.45      .3 543.435    .999 547.433    .381 562.424    .181  569.42   1.579
 657.372   1.015 718.189   2.213 728.155   1.465 741.111   2.521 751.077   1.992
 774.995   2.866 792.933   2.009 805.889   4.598 815.854   5.275  825.82   8.701
#Mann= 3 , 0 , 0
       0     .05       0  275.82     .07       0  437.12     .06       0
#XS Ineff= 2 , 0
       0   268.8     1.3     772       0     1.3
Permanent Ineff=
       F       F
Bank Sta=275.82,437.12
XS Rating Curve= 0 ,0
Exp/Cntr=0.3,0.1

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
Type RM Length L Ch R = 1 ,519.9265,76.01,76.01,76.01
Node Photo=..\Cross Section Photographs\45.JPG
BEGIN DESCRIPTION:
Section 45
END DESCRIPTION:
Node Name=45
XS GIS Cut Line= 4
283033.4976219335273430.97415832283259.0553987255273250.64086736
283387.411682446   5272848.20008283415.5835134895272763.01970187
#Sta/Elev= 30
       0   4.115   2.998   5.444   9.993    3.75  17.987   1.028  41.969    .274
 175.868   -.088 206.845    .782 250.812   -.069  347.62.4073217 352.211   -.165
 404.603   -.925 610.825    .385 612.676   -.144  648.72   -.093  671.29.3980832
 676.912   1.288 686.233    .527 699.214   1.131 703.209    .585 717.179    .063
 728.145   1.409  739.11   1.516 743.098   2.707 746.089   3.016  752.07    2.52
 765.029   2.588 769.017   3.611 792.942   4.743 797.927   6.167 800.917   6.215
#Mann= 3 , 0 , 0
       0    .035       0  347.62    .045       0  671.29     .06       0
#XS Ineff= 2 , 0
       0     479     1.3   645.8       0     1.3
Permanent Ineff=
       F       F
Bank Sta=347.62,671.29
XS Rating Curve= 0 ,0
Exp/Cntr=0.3,0.1

Type RM Length L Ch R = 6 ,500     ,,,
BEGIN DESCRIPTION:
Barrier Beach
END DESCRIPTION:
Lateral Weir Pos= 0
Lateral Weir End=Shearstown_Brook,Main            ,43.48671,
Lateral Weir Distance=100
Lateral Weir TW Multiple XS=0
Lateral Weir WD=20
Lateral Weir Coef=1.1
Lateral Weir WSCriteria=-1
Lateral Weir Flap Gates= 0
Lateral Weir Hagers EQN= 0 ,,,,,
Lateral Weir SS=0.05,0.05,
Lateral Weir Type= 0
Lateral Weir Connection Pos and Dist= 1 ,
Lateral Weir SE= 27
       0   3.032   1.997   2.815   4.992   2.708   6.988     2.8  12.978   2.425
  15.973   1.839  16.972   1.767  18.968   1.893  20.965   1.849   23.96   1.965
  25.957   1.877  27.953   1.931  32.945   1.811  43.927    1.74  64.512   1.437
  68.353   1.747  71.234   1.794  73.182   1.755   77.13   1.448  85.027   1.603
 101.809   1.568 137.731   1.698  168.73   1.623 210.718   1.682 245.349   1.582
 298.769   1.692     356   1.472
Lateral Weir HW RS User Defined=-1
Lateral Weir HW RS Station=519.9265,-100
Lateral Weir HW RS Station=443.9145,356
Lateral Weir TW RS Station=43.48671,0
Lateral Weir TW RS Station=0       ,0
LW Div RC= 0 ,False,

Type RM Length L Ch R = 1 ,443.9145,17.06,17.06,17.06
Node Photo=..\Cross Section Photographs\46.JPG
BEGIN DESCRIPTION:
Section 46
END DESCRIPTION:
Node Name=46
XS GIS Cut Line= 6
283300.3700358045273231.86327597283361.1229911965273118.16049707
283393.0786741575273057.22175282 283428.564345355272994.23933117
283490.0604561625272891.12651697283550.9992004125272789.31422475
#Sta/Elev= 30
       0    .353  17.988      .6  23.984    .216  24.984    .191  25.983   -.074
 218.957   -.074 227.634  -1.571 234.472   -.062 341.456   -.062 346.417    .083
 348.402    .105 352.371    .577 359.316   1.061 370.231   1.568 391.072   2.014
 394.063   2.147 399.049   2.617 405.031   2.674 411.014   3.262 413.008   3.176
 415.002   2.923 422.979   2.769 431.953   2.373 442.921   2.609 448.904   3.161
 456.881   4.497 471.837   4.925 479.814   5.333 498.759   6.426  508.73   7.448
#Mann= 3 , 0 , 0
       0    .035       0  23.984    .035       0 346.417      .1       0
#XS Ineff= 2 , 0
       0   213.3    1.26   240.1       0    1.26
Permanent Ineff=
       F       F
Bank Sta=23.984,346.417
XS Rating Curve= 0 ,0
Exp/Cntr=0.5,0.3

Type RM Length L Ch R = 3 ,436.5357,,,
BEGIN DESCRIPTION:
Railway Bridge
END DESCRIPTION:
Node Name=RailBridge
Bridge Culvert--1,0,-1,-1, 0
Deck Dist Width WeirC Skew NumUp NumDn MinLoCord MaxHiCord MaxSubmerge Is_Ogee
6.1,5,1.4,0, 102, 102, , , 0.98, 0, 2,2,,
   17.99  20.932  24.918  28.904  30.897   32.89  35.879  38.868  40.861  42.854
   46.84  47.836  50.826  53.815  55.808  58.797   60.79  64.776  67.765  70.754
  72.747  75.737  80.719  83.708  86.698  89.687  92.676  96.648  98.633 100.619
 102.605 105.583 108.562 111.541 117.498 119.483 122.462 125.441 128.419 130.405
 133.383 134.376 136.362 137.355 139.341 140.333 143.312 146.291 150.262 152.248
 155.226 156.219 159.198 160.191 162.176 163.169 166.148 169.126 172.105 174.091
 176.076 181.041 186.005 190.969 192.955 196.926 201.891 204.869  219.06  219.06
  234.36  234.36 252.324 255.315 258.307 264.289 269.274 275.257 276.254 280.242
 289.216 290.213 292.207 297.192 304.172 306.166 309.157 314.142 318.131 320.125
 323.116 326.107 331.068 333.052 336.028 339.004  341.98 343.964 345.948 348.924
   351.9  385.11
      .6     .86    .789    .755    .624      .6    .721     .61    .695    .678
    .746    .679    .732    .609    .626    .757     .73     .79    .727    .858
    .826    .944    .954   1.062    .971   1.094   1.079   1.132   1.192   1.155
   1.198   1.167   1.215   1.092   1.159   1.245   1.224   1.321   1.186   1.187
   1.275   1.229   1.273   1.379   1.411     1.3   1.335   1.243   1.316   1.321
   1.269   1.322   1.281   1.371   1.402   1.322   1.353   1.294   1.306    1.38
   1.328   1.374   1.273   1.315    1.28   1.327   1.333    1.31    1.46    1.46
    1.46    1.46   1.369   1.328   1.358   1.355   1.325   1.342   1.299   1.289
   1.353   1.282    1.26   1.285   1.295   1.332   1.276   1.311   1.282   1.332
   1.285   1.334   1.286   1.318   1.422   1.354   1.546   1.556   1.666   1.741
   1.771     1.9
      -2      -2      -2      -2      -2      -2      -2      -2      -2      -2
      -2      -2      -2      -2      -2      -2      -2      -2      -2      -2
      -2      -2      -2      -2      -2      -2      -2      -2      -2      -2
      -2      -2      -2      -2      -2      -2      -2      -2      -2      -2
      -2      -2      -2      -2      -2      -2      -2      -2      -2      -2
      -2      -2      -2      -2      -2      -2      -2      -2      -2      -2
      -2      -2      -2      -2      -2      -2      -2      -2      -2    1.06
    1.06      -2      -2      -2      -2      -2      -2      -2      -2      -2
      -2      -2      -2      -2      -2      -2      -2      -2      -2      -2
      -2      -2      -2      -2      -2      -2      -2      -2      -2      -2
      -2      -2
       5   6.993   8.986  12.972  15.961   18.95  21.939  24.929  27.918  31.904
  33.897   35.89  38.879  41.868  43.861  45.854   49.84  50.836  53.826  56.815
  58.808  61.797   63.79  67.776  70.765  73.754  75.747  78.737  83.719  86.708
  89.698  92.687  95.676  99.648 101.633 103.619 105.605 108.583 111.562 114.541
 120.498 122.483 125.462 128.441 131.419 133.405 136.383 137.376 139.362 140.355
 142.341 143.333 146.312 149.291 153.262 158.226 159.219 162.198 163.191 165.176
 166.169 169.148 172.126 175.105 177.091 179.076 184.041 189.005 193.969 195.955
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BR Coef=-1 , 0 , 0 ,, 0 ,,,0.8,-1,,0,
WSPro=,,,, 1 ,,,, 0 ,,,, 0 ,,,,-1 ,-1 ,-1 , 0 , 0 , 0 , 0 , 0
BC Design=,, 0 ,, 0 ,,,,,,
BC Use User HTab Curves=0
BC User HTab FreeFlow(D)= 0

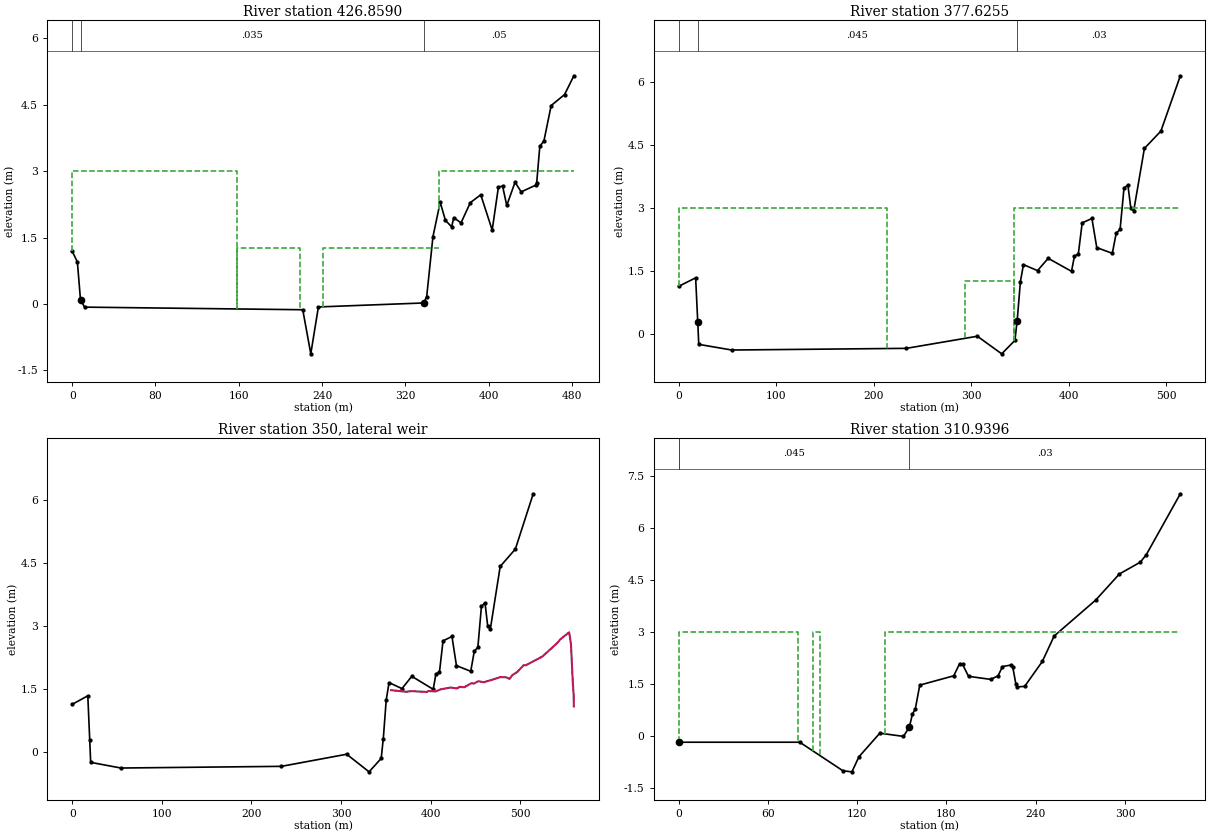
Type RM Length L Ch R = 1 ,426.8590,49.23,49.23,49.23
Node Photo=..\Cross Section Photographs\47.JPG
BEGIN DESCRIPTION:
Section 47
END DESCRIPTION:
Node Name=47
XS GIS Cut Line= 3
283310.0310562335273239.29483015283516.831999219 5272872.0801609
283547.5180335385272819.96757368
#Sta/Elev= 30
       0   1.193   4.993     .95   7.989    .088  11.984    -.07  221.49   -.129
 229.201  -1.125 236.502   -.066 337.553    .024 340.549    .167 346.542    1.52
 353.532   2.299 358.526   1.889 364.518   1.744 366.515   1.951 373.506   1.833
 382.494   2.291 392.481   2.467 403.467    1.67 409.459   2.645 413.454   2.662
 417.448   2.226 425.409    2.75 431.357   2.533 445.237   2.684 446.229   2.743
 449.203   3.562 453.169   3.684 460.109   4.483 472.997   4.731  481.92   5.155
#Mann= 3 , 0 , 0
       0    .035       0   7.989    .035       0 337.553     .05       0
#XS Ineff= 4 ,-1
       0   158.2       3   158.2   218.5    1.26   240.6   352.2    1.26
   352.2     500       3
Permanent Ineff=
       F       F       F       F
Bank Sta=7.989,337.553
XS Rating Curve= 0 ,0
Exp/Cntr=0.5,0.3

Type RM Length L Ch R = 1 ,377.6255,66.69,66.69,66.69
Node Photo=..\Cross Section Photographs\48.JPG
BEGIN DESCRIPTION:
Section 48
END DESCRIPTION:
Node Name=48
XS GIS Cut Line= 3
283316.6865485525273255.19152789283532.2738355985272947.01733186
283567.0444739495272812.91860813
#Sta/Elev= 30
       0   1.134  17.429   1.337  19.561    .293  20.634    -.25  54.431   -.385
 233.617   -.345 306.411   -.056  331.39   -.476 344.924   -.156 347.286    .318
 350.561   1.245 353.709   1.652 368.118   1.509 379.089   1.802 403.008   1.492
 405.998   1.856 409.985   1.906 413.971   2.648 423.938   2.752 428.921   2.057
 444.867   1.922 448.854   2.401  452.84   2.493 456.827   3.473 460.813   3.553
 463.803   3.007 466.793   2.934 477.756   4.423 494.699   4.837 514.632   6.156
#Mann= 3 , 0 , 0
       0     .03       0  19.561    .045       0 347.286     .03       0
#XS Ineff= 3 ,-1
       0     214       3     294   344.2    1.26   344.2     515       3
Permanent Ineff=
       F       F       F
Bank Sta=19.561,347.286
XS Rating Curve= 0 ,0
Exp/Cntr=0.3,0.1

Type RM Length L Ch R = 6 ,350     ,,,
BEGIN DESCRIPTION:
Barrier Beach
END DESCRIPTION:
Lateral Weir Pos= 0
Lateral Weir End=Shearstown_Brook,Main            ,43.48671,
Lateral Weir Distance=0
Lateral Weir TW Multiple XS=0
Lateral Weir WD=20
Lateral Weir Coef=1.1
Lateral Weir WSCriteria=-1
Lateral Weir Flap Gates= 0
Lateral Weir Hagers EQN= 0 ,,,,,
Lateral Weir SS=0.05,0.05,
Lateral Weir Type= 0
Lateral Weir Connection Pos and Dist= 1 ,
Lateral Weir SE= 30
     356   1.472 372.867   1.434 378.834   1.449 395.738   1.429 397.727   1.451
 405.682   1.441 411.648   1.494 422.587   1.535 429.547   1.512 432.531   1.552
 437.502   1.541 445.458   1.637 448.441   1.629 453.413   1.686 459.379    1.66
 478.272   1.784 484.238    1.78 488.211    1.74 491.192    1.83 497.153   1.911
 504.107   2.072 506.094   2.063  524.97   2.276 541.859   2.605 544.839   2.686
 554.774   2.851 556.761   2.569 558.747   1.681 559.741   1.357     560   1.083
Lateral Weir HW RS User Defined=-1
Lateral Weir HW RS Station=377.6255,356
Lateral Weir HW RS Station=310.9396,560
Lateral Weir TW RS Station=43.48671,356
Lateral Weir TW RS Station=0       ,0
LW Div RC= 0 ,False,

Type RM Length L Ch R = 1 ,310.9396,30.48,30.48,30.48
Node Photo=..\Cross Section Photographs\49.JPG
BEGIN DESCRIPTION:
Section 49
END DESCRIPTION:
Node Name=49
XS GIS Cut Line= 6
283502.2181972345273133.89678214283519.2490634915273100.62504274
283532.5992213525273046.17045146283541.3822199455272973.09590316
283566.8528555155272876.13751009283575.852241862  5272806.801189
#Sta/Elev= 30
       0   -.176  81.403   -.176  110.44      -1 116.476   -1.03 121.153   -.597
 135.218    .085 151.131   -.008  155.11    .266 157.099    .629 159.088    .789
 162.072   1.471 184.911   1.739 188.881   2.092 190.866   2.066 194.836   1.724
 209.725   1.636 214.687   1.737 217.665   2.006  223.62   2.052 224.613   1.985
 226.598   1.517  227.59   1.421 232.553   1.433 244.464   2.154 252.404   2.887
 280.278   3.921 296.259   4.676 310.243   5.014 314.238   5.224 337.211   6.988
#Mann= 3 , 0 , 0
       0     .03       0       0    .045       0  155.11     .03       0
#XS Ineff= 3 ,-1
       0      80       3      90      95       3   138.9     350       3
Permanent Ineff=
       F       F       F
Bank Sta=0,155.11
XS Rating Curve= 0 ,0
Exp/Cntr=0.5,0.3