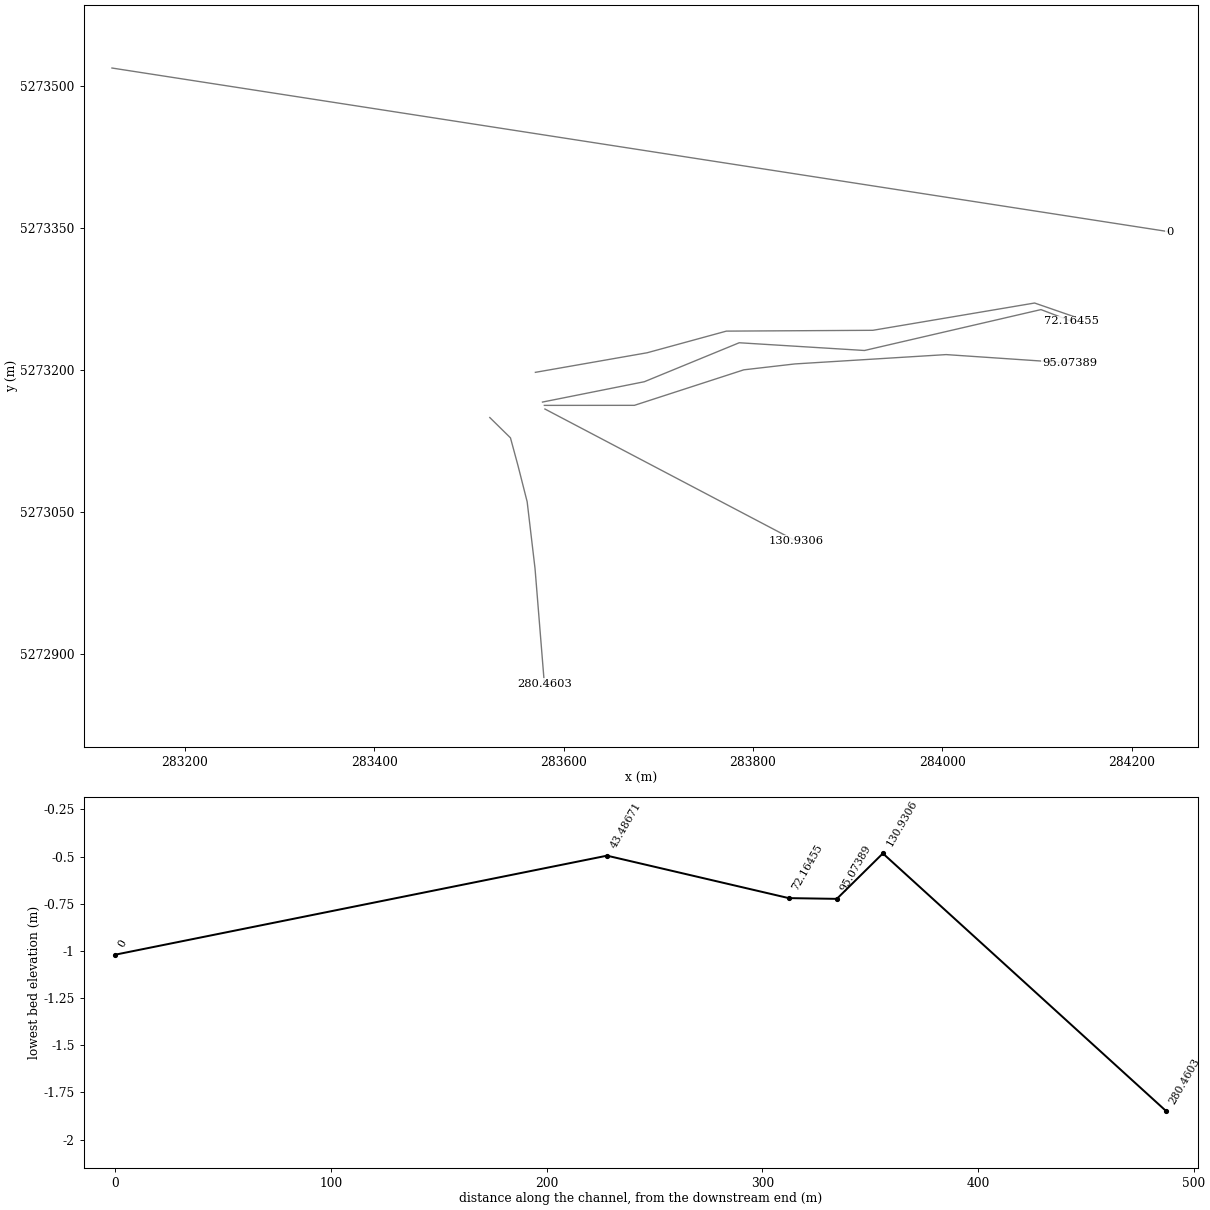
HEC-RAS study ShearstownModel.prj: Shearstown Model

--- ShearstownModel.g01 (geometry) --- (continued)

Type RM Length L Ch R = 4 ,292.3195,,,
BEGIN DESCRIPTION:
Conception Bay Highway Bridge
END DESCRIPTION:
Node Name=HWY70Bridge
Bridge Culvert--1,0,-1,-1, 0
Deck Dist Width WeirC Skew NumUp NumDn MinLoCord MaxHiCord MaxSubmerge Is_Ogee
10.45,9.6,1.4,0, 266, 271, , , 0.98, 0, 2,2,,
     -10  -9.029  -8.058  -7.087  -6.116  -5.145  -4.174  -3.204  -2.233  -1.262
   -.291     .68   1.651   2.629   3.608   4.586   5.564   6.543   7.521     8.5
   9.478  10.456  11.435  12.413  13.391   14.37  15.348  16.326  17.305  18.283
  19.261   20.24  21.218  22.196  23.175  24.153  25.131   26.11  27.088  28.066
  29.045  30.023  31.002   31.98  32.958  33.936  34.914  35.892   36.87  37.848
  38.826  39.804  40.782  41.759  42.737  43.715  44.693  45.671  46.649  47.627
  48.605  49.583  50.561  51.539  52.517  53.495  54.473  55.451  56.429  57.407
  58.385  59.363  60.341  61.319  62.297  63.275  64.253   65.23  66.208  67.186
  68.164  69.142  70.109  71.076  72.042  73.009  73.976  74.942  75.909  76.876
  77.843  78.809  79.776  80.743  81.709  82.676  83.643    96.4     108     108
     123     123   131.1 145.879  146.87 147.862 148.853 149.845 150.837 151.828
  152.82 153.812 154.803 155.795 156.787 157.778  158.77 159.762 160.753 161.745
 162.737 163.728  164.72 165.712 166.703 167.695 168.687 169.678  170.67 171.662
 172.653 173.645 174.636 175.628  176.62 177.611 178.603 179.595 180.593 181.591
 182.589 183.587 184.585 185.583 186.582  187.58 188.578 189.576 190.574 191.572
  192.57 193.568 194.567 195.565 196.563 197.561 198.559 199.557 200.555 201.553
 202.552  203.55 204.548 205.546 206.544 207.542  208.54 209.538 210.537 211.535
 212.533 213.531 214.529 215.527 216.525 217.523 218.522  219.52 220.518 221.516
 222.514 223.512 224.487 225.462 226.436 227.411 228.386 229.361 230.336  231.31
 232.285  233.26 234.235 235.209 236.184 237.159 238.134 239.109 240.083 241.058
 242.033 243.008 243.982 244.957 245.932 246.907 247.882 248.856 249.847 250.837
 251.827 252.817 253.807 254.797 255.787 256.777 257.767 258.758 259.748 260.738
 261.728 262.718 263.708 264.698 265.688 266.678 267.669 268.659 269.649 270.639
 271.629 272.619 273.609 274.607 275.605 276.602   277.6 278.598 279.595 280.593
 281.591 282.588 283.586 284.584 285.581 286.579 287.577 288.574 289.572  290.57
 291.567 292.565 293.563 294.561 295.558 296.556 297.554 298.551 299.549 300.547
 301.544 302.542  303.54 304.537 305.535 306.533
   2.961   2.984       3    3.01   3.018   3.032   3.037   3.051   3.064    3.08
   3.104   3.117   3.137   3.141   3.147   3.151   3.173   3.187   3.202   3.207
   3.216   3.225   3.241    3.25   3.267   3.284   3.301   3.312   3.327   3.342
   3.352   3.359   3.376     3.4   3.422   3.444   3.453    3.47   3.483   3.506
   3.519   3.543   3.542   3.555    3.56   3.574   3.589   3.599   3.619   3.629
   3.632   3.634   3.637   3.647   3.652   3.656   3.658    3.66   3.671   3.672
   3.672   3.686   3.697   3.701   3.706   3.708   3.699   3.699   3.714   3.712
   3.709   3.717   3.713   3.711   3.711   3.718   3.706   3.704   3.696   3.691
   3.704   3.701   3.698     3.7   3.692   3.685    3.69   3.693   3.689   3.685
   3.678   3.669   3.657   3.646    3.64   3.638   3.629    3.62     4.2     4.2
    3.92    3.92    3.03    2.45   2.429   2.385    2.35   2.329     2.3    2.27
   2.249   2.249   2.241   2.227   2.218   2.205     2.2   2.187   2.179   2.164
   2.149    2.15   2.158   2.158   2.147   2.135   2.128   2.126   2.121   2.112
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                                                                      -1    3.71
    3.43      -1
       0       7   7.971   8.942   9.913  10.884  11.855  12.826  13.796  14.767
  15.738  16.709   17.68  18.651  19.629  20.608  21.586  22.564  23.543  24.521
    25.5  26.478  27.456  28.435  29.413  30.391   31.37  32.348  33.326  34.305
  35.283  36.261   37.24  38.218  39.196  40.175  41.153  42.131   43.11  44.088
  45.066  46.045  47.023  48.002   48.98  49.958  50.936  51.914  52.892   53.87
  54.848  55.826  56.804  57.782  58.759  59.737  60.715  61.693  62.671  63.649
  64.627  65.605  66.583  67.561  68.539  69.517  70.495  71.473  72.451  73.429
  74.407  75.385  76.363  77.341  78.319  79.297  80.275  81.253   82.23  83.208
  84.186  85.164  86.142  87.109  88.076  89.042  90.009  90.976  91.942   125.2
   125.2   140.2   140.2 148.027 149.016 150.006 150.996 151.985 152.975 153.964
 154.954 155.943 156.933 157.922 158.912 159.904 160.895 161.887 162.879  163.87
 164.862 165.853 166.845 167.837 168.828  169.82 170.812 171.803 172.795 173.787
 174.778  175.77 176.762 177.753 178.745 179.737 180.728  181.72 182.712 183.703
 184.695 185.687 186.678  187.67 188.662 189.653 190.645 191.636 192.628  193.62
 194.611 195.603 196.595 197.593 198.591 199.589 200.587 201.585 202.583 203.582
  204.58 205.578 206.576 207.574 208.572  209.57 210.568 211.567 212.565 213.563
 214.561 215.559 216.557 217.555 218.553 219.552  220.55 221.548 222.546 223.544
 224.542  225.54 226.538 227.537 228.535 229.533 230.531 231.529 232.527 233.525
 234.523 235.522  236.52 237.518 238.516 239.514 240.512 241.487 242.462 243.436
 244.411 245.386 246.361 247.336  248.31 249.285  250.26 251.235 252.209 253.184
 254.159 255.134 256.109 257.083 258.058 259.033 260.008 260.982 261.957 262.932
 263.907 264.882 265.856 266.847 267.837 268.827 269.817 270.807 271.797 272.787
 273.777 274.767 275.758 276.748 277.738 278.728 279.718 280.708 281.698 282.688
 283.678 284.669 285.659 286.649 287.639 288.629 289.619 290.609 291.607 292.605
 293.602   294.6 295.598 296.595 297.593 298.591 299.588 300.586 301.584 302.581
 303.579 304.577 305.574 306.572  307.57 308.567 309.565 310.563 311.561 312.558
 313.556 314.554 315.551 316.549 317.547 318.544 319.542  320.54 321.537 322.535
 323.533
     2.9   2.961   2.984       3    3.01   3.018   3.032   3.037   3.051   3.064
    3.08   3.104   3.117   3.137   3.141   3.147   3.151   3.173   3.187   3.202
   3.207   3.216   3.225   3.241    3.25   3.267   3.284   3.301   3.312   3.327
   3.342   3.352   3.359   3.376     3.4   3.422   3.444   3.453    3.47   3.483
   3.506   3.519   3.543   3.542   3.555    3.56   3.574   3.589   3.599   3.619
   3.629   3.632   3.634   3.637   3.647   3.652   3.656   3.658    3.66   3.671
   3.672   3.672   3.686   3.697   3.701   3.706   3.708   3.699   3.699   3.714
   3.712   3.709   3.717   3.713   3.711   3.711   3.718   3.706   3.704   3.696
   3.691   3.704   3.701   3.698     3.7   3.692   3.685    3.69   3.693     4.2
     4.2    3.92    3.92   2.678   2.661   2.635   2.613   2.592   2.575   2.559
   2.538   2.512    2.49   2.477   2.461    2.45   2.448   2.449    2.45   2.429
   2.385    2.35   2.329     2.3    2.27   2.249   2.249   2.241   2.227   2.218
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                                                                              -1
    3.71    3.43      -1
BR Coef=-1 , 0 , 0 ,, 0 ,,,0.8,0,,0,
WSPro=,,,, 1 ,,,, 0 ,,,, 0 ,,,,-1 ,-1 ,-1 , 0 , 0 , 0 , 0 , 0
Culvert=1,2.4,,24,0.024,0.9,1,2,3,-0.03,82.9,-0.31,98.85,Culvert #1  , 0 ,3
Culvert Bottom n=0.024
Culvert=1,2.4,,24,0.024,0.9,1,2,3,-0.47,86.4,-0.6,102.85,Culvert #2  , 0 ,3
Culvert Bottom n=0.024
BC Mult= 2 ,0,100,0,115
BC Mult= 3 ,90,350,105,300
BC Design=,, 0 ,, 0 ,,,,,,
BC Use User HTab Curves=0
BC User HTab FreeFlow(D)= 0

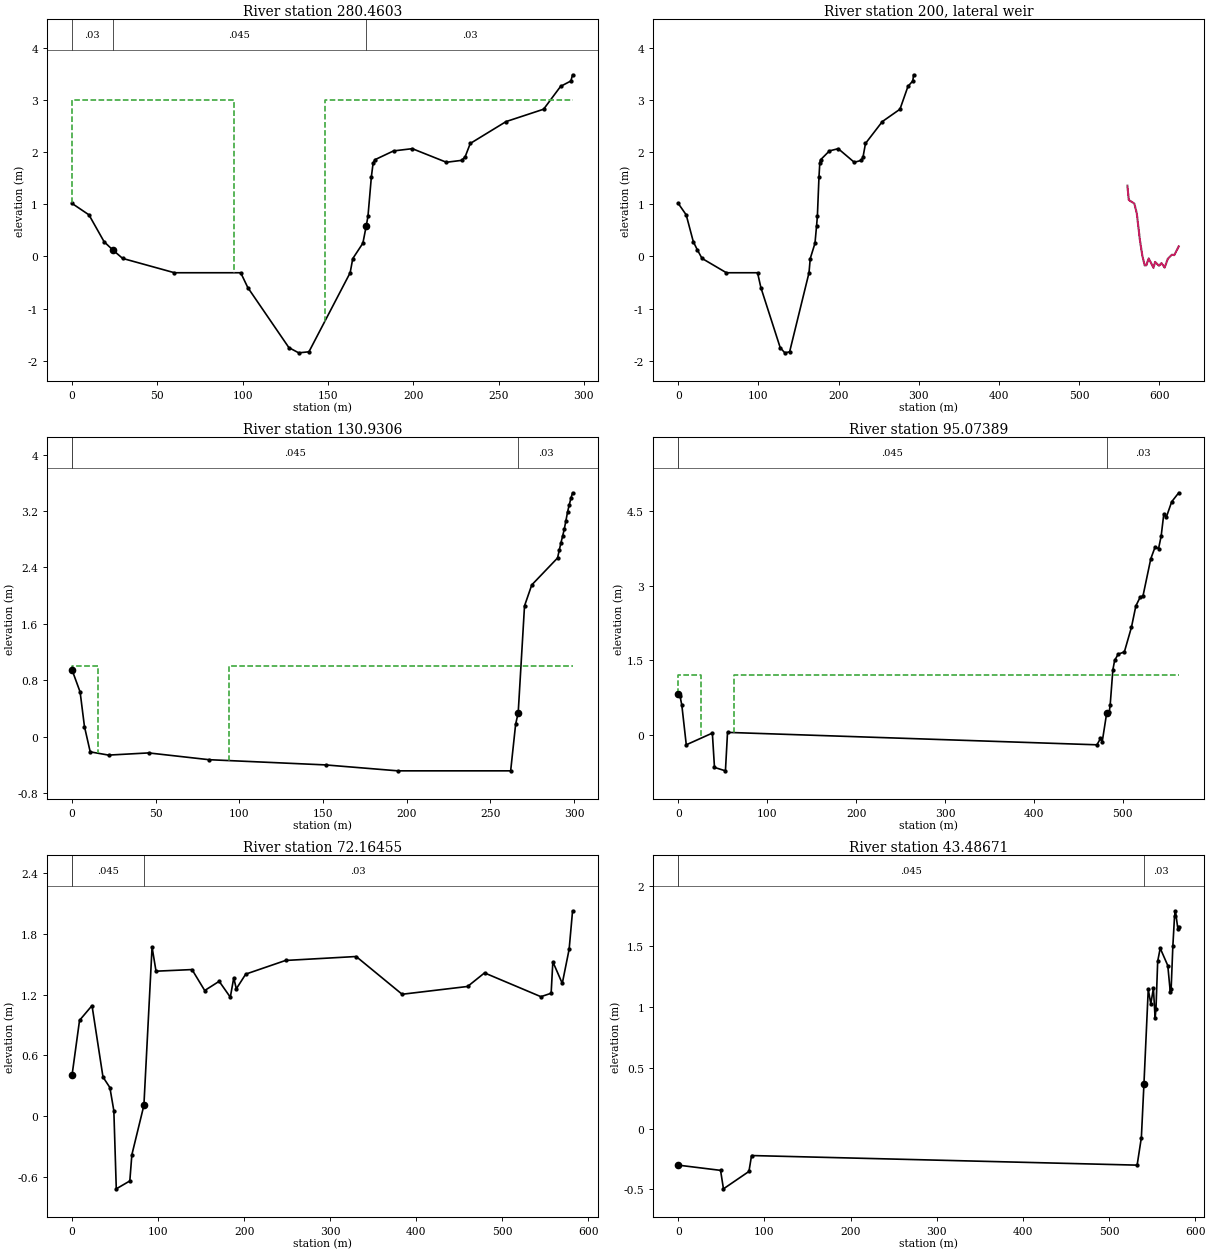
Type RM Length L Ch R = 1 ,280.4603,172.11,131.4,203.46
Node Photo=..\Cross Section Photographs\50.JPG
BEGIN DESCRIPTION:
Section 50
END DESCRIPTION:
Node Name=50
XS GIS Cut Line= 6
 283522.062444495273149.85000052283543.8822346655273128.40303837
283551.8497124315273098.99925137283561.5245068615273060.86917921
283569.839135387 5272990.3105804283579.6760938115272868.75387987
#Sta/Elev= 30
       0   1.016   9.869    .798  18.752    .282  23.687    .129  29.608   -.038
      60   -.313  98.846   -.313     103   -.598 127.084   -1.75 132.828   -1.85
 138.837   -1.83     163   -.313 164.537   -.041 170.458    .254 172.444    .588
 173.444    .771 175.443    1.53 176.443   1.788 177.442   1.855 188.438   2.025
 199.434   2.068 219.426   1.807 228.423   1.844 230.422   1.913 233.421   2.168
 254.413   2.588 276.405   2.825 286.401   3.264 292.399   3.367 293.399   3.486
#Mann= 3 , 0 , 0
       0     .03       0  23.687    .045       0 172.444     .03       0
#XS Ineff= 2 , 0
       0      95       3     148       0       3
Permanent Ineff=
       F       F
Bank Sta=23.687,172.444
XS Rating Curve= 0 ,0
Exp/Cntr=0.5,0.3

Type RM Length L Ch R = 6 ,200     ,,,
BEGIN DESCRIPTION:
Barrier Beach
END DESCRIPTION:
Lateral Weir Pos= 0
Lateral Weir End=Shearstown_Brook,Main            ,43.48671,
Lateral Weir Distance=0
Lateral Weir TW Multiple XS=0
Lateral Weir WD=20
Lateral Weir Coef=1.1
Lateral Weir WSCriteria=-1
Lateral Weir Flap Gates= 0
Lateral Weir Hagers EQN= 0 ,,,,,
Lateral Weir SS=0.05,0.05,
Lateral Weir Type= 0
Lateral Weir Connection Pos and Dist= 1 ,
Lateral Weir SE= 18
     560   1.357 561.727   1.083 568.681   1.014 571.661     .83 575.634     .31
 578.614    .017 581.594   -.174 583.581    -.17 586.561   -.037 592.521   -.218
 594.508   -.106 599.475    -.18 602.455   -.127 606.428   -.214 610.401   -.044
 615.368    .032 618.348    .025     624    .192
Lateral Weir HW RS User Defined=-1
Lateral Weir HW RS Station=280.4603,560
Lateral Weir HW RS Station=130.9306,624
Lateral Weir TW RS Station=43.48671,560
Lateral Weir TW RS Station=0       ,0
LW Div RC= 0 ,False,

Type RM Length L Ch R = 1 ,130.9306,169.92,21.35,20
Node Photo=..\Cross Section Photographs\51.JPG
BEGIN DESCRIPTION:
Section 51
END DESCRIPTION:
Node Name=51
XS GIS Cut Line= 2
283580.291020371 5273158.8379694 283844.99891245 5273019.6966415
#Sta/Elev= 24
       0    .944   4.781    .634   7.363    .145  10.808   -.214  21.776    -.26
  45.704   -.229  81.778   -.325  151.43   -.399 194.655   -.483 262.048   -.483
 265.031    .179 266.551    .338 270.335   1.855 274.659   2.152 290.077   2.534
 291.074   2.643 292.071   2.746 293.068    2.84 294.065    2.94 295.061   3.061
 296.058   3.186 297.055   3.287 298.052   3.379 299.049   3.458
#Mann= 3 , 0 , 0
       0     .03       0       0    .045       0 266.551     .03       0
#XS Ineff= 2 , 0
       0    15.7       1    93.8       0       1
Permanent Ineff=
       F       F
Bank Sta=0,266.551
XS Rating Curve= 0 ,0
Exp/Cntr=0.3,0.1

Type RM Length L Ch R = 1 ,95.07389,20.65,22.28,17.68
Node Photo=..\Cross Section Photographs\52.JPG
BEGIN DESCRIPTION:
Section 52
END DESCRIPTION:
Node Name=52
XS GIS Cut Line= 6
283579.6496718225273162.69039581 283674.780875735273162.73952167
283790.3245664085273200.24693075 283844.280166795273206.47257695
284004.071752543 5273216.3298501284134.2915188525273207.51018465
#Sta/Elev= 30
       0    .813   1.997    .777   3.993    .597   8.985     -.2  38.316    .036
  40.702   -.655   53.03   -.724  55.376     .05 470.775     -.2 474.754   -.073
 476.743   -.136 481.716    .436   484.7     .47 485.694    .609 488.678   1.308
 490.667   1.498 494.646   1.625 501.608   1.669 509.566   2.165  514.54   2.595
 519.514   2.777 522.499   2.791 531.335   3.545 536.192   3.782 540.077   3.749
 542.991   4.001 545.905   4.438 548.861   4.385 554.813   4.692 562.749   4.873
#Mann= 3 , 0 , 0
       0     .03       0       0    .045       0 481.716     .03       0
#XS Ineff= 2 , 0
       0    25.8     1.2   63.18       0     1.2
Permanent Ineff=
       F       F
Bank Sta=0,481.716
XS Rating Curve= 0 ,0
Exp/Cntr=0.5,0.3

Type RM Length L Ch R = 1 ,72.16455,43.33,84.24,26.07
Node Photo=..\Cross Section Photographs\53.JPG
BEGIN DESCRIPTION:
Section 53
END DESCRIPTION:
Node Name=53
XS GIS Cut Line= 6
283577.704157385 5273166.1923218283685.2826575295273187.68436555
283785.4850992485273228.83788666283917.7800809575273220.66672603
284104.1603640125273263.85714652284136.8450065535273251.40585413
#Sta/Elev= 30
       0    .409   8.609    .945  23.119   1.091  35.872    .385  43.885    .281
  48.489    .052  51.335    -.72  67.063   -.642  69.443   -.383  83.424    .105
  92.922   1.669  97.526   1.431 139.356   1.447 154.117    1.24 170.926   1.331
 183.883   1.174  187.87   1.365  190.86   1.257 201.791   1.402 248.094   1.537
 330.178   1.576 383.581   1.203 459.717    1.28 479.383   1.414 544.924   1.179
 556.814   1.213 558.796   1.524 569.759    1.31 577.741   1.648 581.732   2.028
#Mann= 3 , 0 , 0
       0     .03       0       0    .045       0  83.424     .03       0
Bank Sta=0,83.424
XS Rating Curve= 0 ,0
Exp/Cntr=0.5,0.3

Type RM Length L Ch R = 1 ,43.48671,228,228,228
Node Photo=..\Cross Section Photographs\54.JPG
BEGIN DESCRIPTION:
Section 54
END DESCRIPTION:
Node Name=54
XS GIS Cut Line= 6
283570.219214844 5273197.5961977283688.2993020925273218.28176043
 283771.903451465273241.12206928283926.6142227135273241.98396772
284097.4564455145273270.80425433 284140.928278475273255.77052092
#Sta/Elev= 23
       0     -.3   49.09   -.343  52.453   -.495  82.026   -.352  85.079   -.221
 532.729     -.3 537.649   -.073 540.644    .369 545.635   1.147 548.629   1.027
 551.624   1.155  553.62    .909 554.618    .988 556.594   1.377 559.525   1.485
 568.321   1.342 571.253   1.123  572.23   1.152 574.185     1.5 576.139   1.746
 577.117   1.793 580.049   1.644 581.026   1.663
#Mann= 3 , 0 , 0
       0     .03       0       0    .045       0 540.644     .03       0
Bank Sta=0,540.644
XS Rating Curve= 0 ,0
Exp/Cntr=0.5,0.3

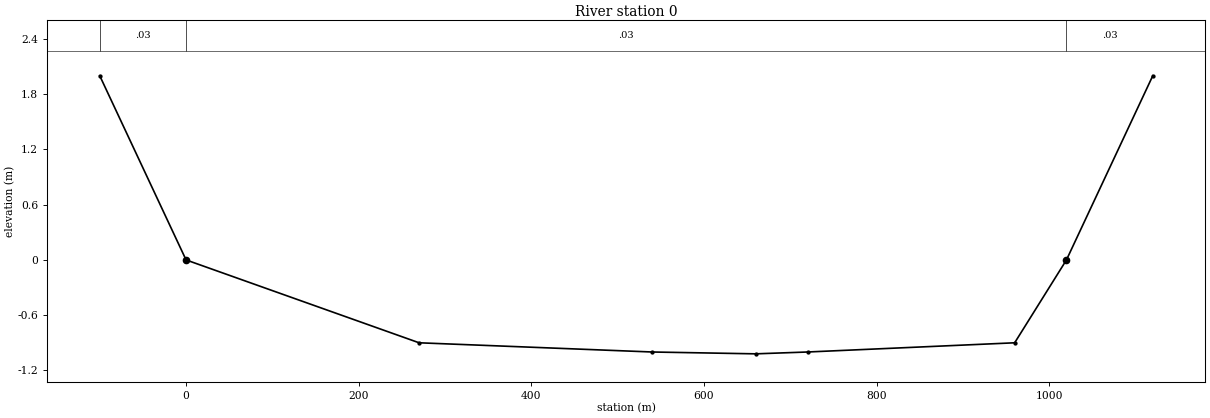
Type RM Length L Ch R = 1 ,0       ,,,
BEGIN DESCRIPTION:
Downstream BC
END DESCRIPTION:
XS GIS Cut Line= 2
         283123.        5273519.         284240.        5273346.
#Sta/Elev= 9
    -100       2       0       0     270     -.9     540      -1     660   -1.02
     720      -1     960     -.9    1020       0    1120       2
#Mann= 3 , 0 , 0
    -100     .03       0       0     .03       0    1020     .03       0
Bank Sta=0,1020
XS Rating Curve= 0 ,0
Exp/Cntr=0.3,0.1
Stream Node=Shearstown_Brook,Main            , 0 , 0 ,Upstream end
Stream Node=Shearstown_Brook,Main            , 0 , 1 ,Downstream end

Chan Stop Cuts=-1
Use User Specified Reach Order=0
Composite Channel Slope=5

--- ShearstownModel.g02 (geometry) ---

Geom Title=Shearstown Sens n+20%
Program Version=4.10

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
River Reach=Shearstown_Brook,Main

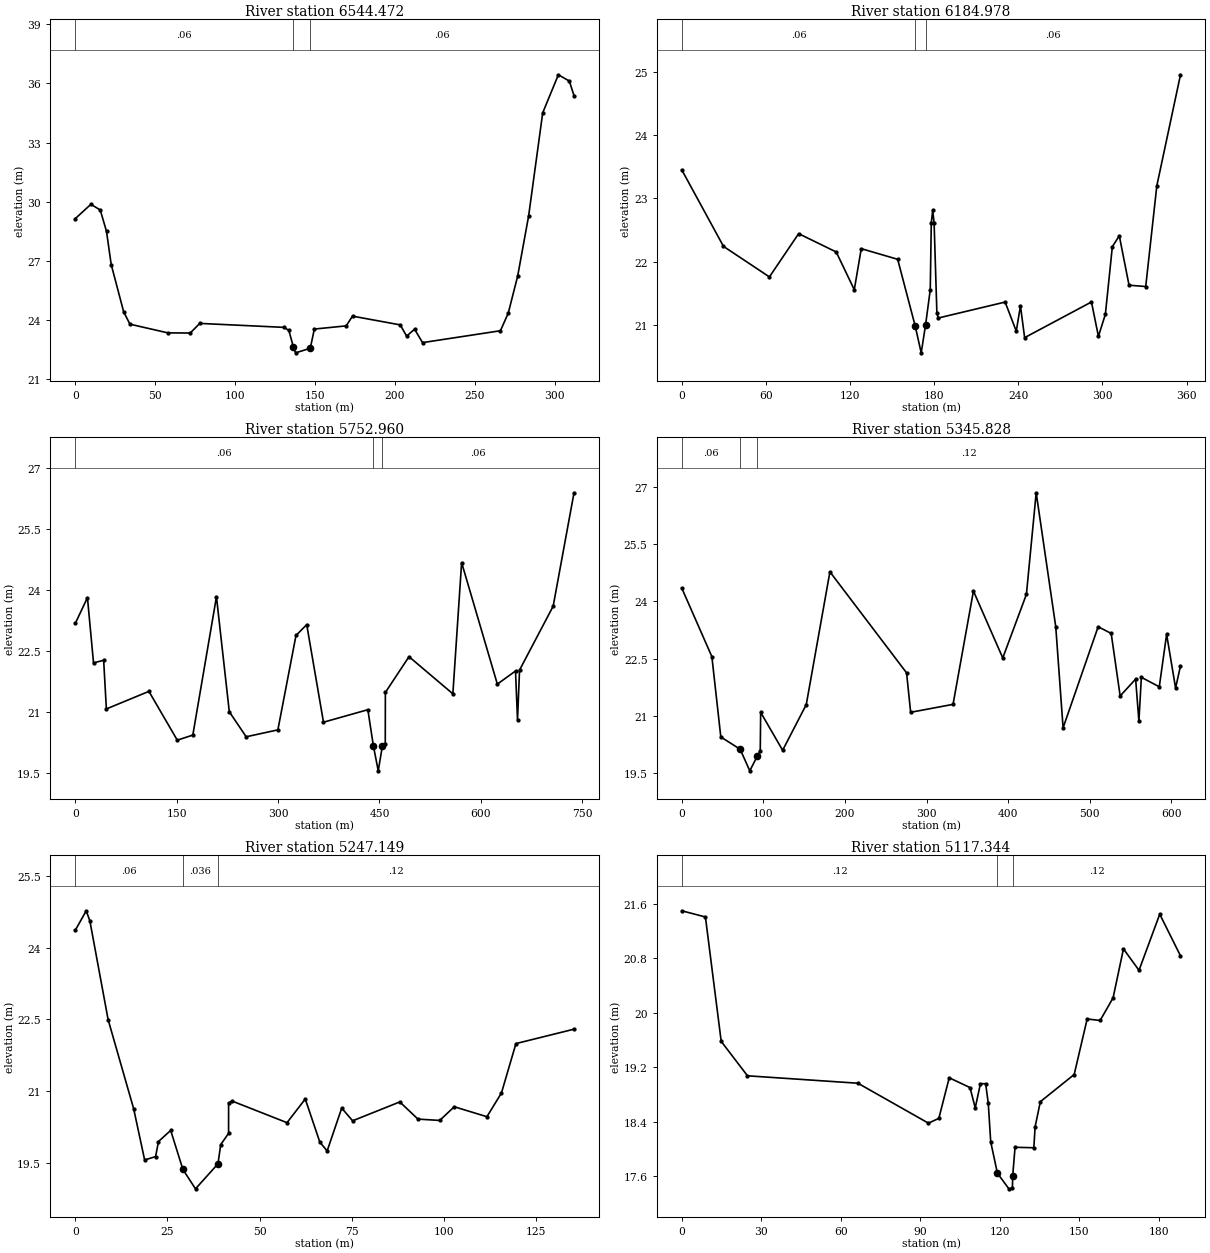
Type RM Length L Ch R = 1 ,6544.472,23.97,23.97,23.97
BEGIN DESCRIPTION:
Section 2
END DESCRIPTION:
Node Name=2
XS GIS Cut Line= 4
279642.8886158175269616.29250684279676.2254208965269594.05736596
279865.5728973935269474.22258917279906.754524344 5269449.5598458
#Sta/Elev= 30
       0  29.145   9.774  29.868  15.638  29.579  19.547  28.491  22.479  26.816
  30.298  24.414  34.208  23.792  57.998  23.351  71.941  23.345  77.917  23.832
   130.7  23.631 133.688  23.474   136.5  22.635  137.91   22.34  147.09  22.572
 149.623  23.545 169.542  23.707 173.525    24.2 203.403  23.757 207.387  23.186
 212.366   23.54 217.346  22.858 266.114   23.46 271.012  24.358  276.89   26.23
 283.747  29.278 292.564  34.506 302.361  36.434 309.218  36.116 312.157  35.377
#Mann= 3 , 0 , 0
       0     .06       0   136.5    .042       0  147.09     .06       0
Bank Sta=136.5,147.09
XS Rating Curve= 0 ,0
Exp/Cntr=0.3,0.1

Type RM Length L Ch R = 1 ,6184.978,24,24,24
BEGIN DESCRIPTION:
Section 3
END DESCRIPTION:
Node Name=3
XS GIS Cut Line= 5
 279820.72889364 5269887.8296174279934.1476008725269832.90339471
 279984.689044135269804.58392651280069.3762310125269709.81074358
280098.4158214875269675.93122135
#Sta/Elev= 30
       0  23.448  29.768  22.239  62.513  21.757  83.351   22.44 110.142  22.151
 123.042  21.555 128.016  22.203 153.987  22.035  166.4720.98214 170.769  20.558
  173.8720.99633 177.219  21.555  177.96  22.608 178.959  22.807 179.958  22.614
 181.955  21.184 182.954  21.108 230.622   21.36 238.565    20.9 241.544    21.3
 244.523  20.798 292.185  21.361 297.149  20.819 302.114  21.167 307.079  22.235
 312.042  22.406 318.984  21.626 330.883  21.605 338.816  23.198 355.673  24.949
#Mann= 3 , 0 , 0
       0     .06       0  166.47    .036       0  173.87     .06       0
Bank Sta=166.47,173.87
XS Rating Curve= 0 ,0
Exp/Cntr=0.3,0.1

Type RM Length L Ch R = 1 ,5752.960,23.95,23.95,23.95
BEGIN DESCRIPTION:
Section 4
END DESCRIPTION:
Node Name=4
XS GIS Cut Line= 6
279864.7088621385269962.89535559280148.460317394 5269914.7111462
280225.7080181515269946.06912374280258.8978504125270033.83840265
280291.7523945065270077.91709703280468.1728860055269961.66313154
#Sta/Elev= 30
       0  23.177  17.988  23.809  26.983  22.207  41.973  22.272   45.97  21.077
 108.929  21.508 150.902   20.31 173.888  20.435 208.865   23.83 227.853  21.008
 252.837  20.393 299.724  20.563 326.522   22.88 342.402  23.147 367.214  20.751
  432.86  21.058  440.9720.17692 448.221  19.557  454.24  20.157 458.619  20.216
 458.778  21.482 493.732   22.36  558.62  21.448 571.581   24.67 624.423  21.686
 651.306  22.008 654.291  20.805 657.276  22.031 707.025  23.599  737.87  26.384
#Mann= 3 , 0 , 0
       0     .06       0  440.97    .042       0  454.24     .06       0
Bank Sta=440.97,454.24
XS Rating Curve= 0 ,0
Exp/Cntr=0.3,0.1

Type RM Length L Ch R = 1 ,5345.828,24.67,24.67,24.67
BEGIN DESCRIPTION:
Section 5
END DESCRIPTION:
Node Name=5
XS GIS Cut Line= 5
279949.9376922285270261.38038633279992.9928032745270252.93819582
280078.9236277615270235.18545406 280243.823128035270203.54021435
 280514.572495045270049.04481284
#Sta/Elev= 30
       0  24.345  36.895  22.551  47.863  20.448   71.5720.12595  83.392  19.561
    92.719.95229  96.207  20.083  96.722  21.092 123.644  20.099 152.609  21.295
 181.593   24.77 275.541  22.126 280.539  21.093 332.499  21.301 357.477  24.267
 393.445  22.516 422.419   24.18 434.409  26.839 458.387  23.333  467.38  20.687
 510.341  23.332 526.328  23.158 537.318  21.521 556.302  21.962 560.299  20.856
 563.296  22.009 585.277  21.761  594.27  23.134  605.26  21.728 611.255  22.307
#Mann= 3 , 0 , 0
       0     .06       0   71.57    .042       0    92.7     .12       0
Bank Sta=71.57,92.7
XS Rating Curve= 0 ,0
Exp/Cntr=0.3,0.1

Type RM Length L Ch R = 1 ,5247.149,21.63,21.63,21.63
BEGIN DESCRIPTION:
Section 6
END DESCRIPTION:
Node Name=6
XS GIS Cut Line= 3
280032.4970469815270351.86658041280096.3958268435270322.49029571
280154.3381677475270293.02517464
#Sta/Elev= 30
       0  24.371   2.972  24.779   3.962  24.565   8.915  22.495  15.849  20.626
   18.82  19.555  21.792  19.626  22.573  19.942  25.887  20.175    29.2  19.356
  32.621   18.95   38.7219.47467  39.468  19.879  41.597  20.112  41.602  20.749
  42.593  20.789  57.451  20.337  62.404  20.833  66.366  19.928  68.347  19.745
  72.298  20.643  75.253  20.376  88.056  20.772  92.981  20.412   98.89  20.384
  102.83  20.671 111.694  20.462 115.634  20.958 119.573  21.995 135.332  22.297
#Mann= 3 , 0 , 0
       0     .06       0    29.2    .036       0   38.72     .12       0
Bank Sta=29.2,38.72
XS Rating Curve= 0 ,0
Exp/Cntr=0.3,0.1

Type RM Length L Ch R = 1 ,5117.344,22.05,22.05,22.05
BEGIN DESCRIPTION:
Section 7
END DESCRIPTION:
Node Name=7
XS GIS Cut Line= 5
280072.2465517615270501.69594384280128.3868047095270449.91716011
280150.1082838745270423.33692903280165.4760816075270388.23960006
280179.8961941525270351.88511824
#Sta/Elev= 30
       0  21.499   8.927  21.408  14.878  19.582  24.796  19.077  66.454  18.968
  93.046  18.382  96.969  18.452 100.892  19.048 108.738  18.904 110.699  18.606
 112.664  18.961 114.629  18.961 115.612  18.678 116.543  18.107  119.0717.64742
 123.405  17.418 124.732  17.423  124.8217.60086  125.72  18.028 132.809  18.021
 133.295   18.33  135.26  18.697 148.031  19.096 152.925  19.911 157.814  19.889
 162.702  20.221 166.613   20.94  172.48  20.625 180.302  21.449 188.124  20.838
#Mann= 3 , 0 , 0
       0     .12       0  119.07    .036       0  124.82     .12       0
Bank Sta=119.07,124.82
XS Rating Curve= 0 ,0
Exp/Cntr=0.3,0.1

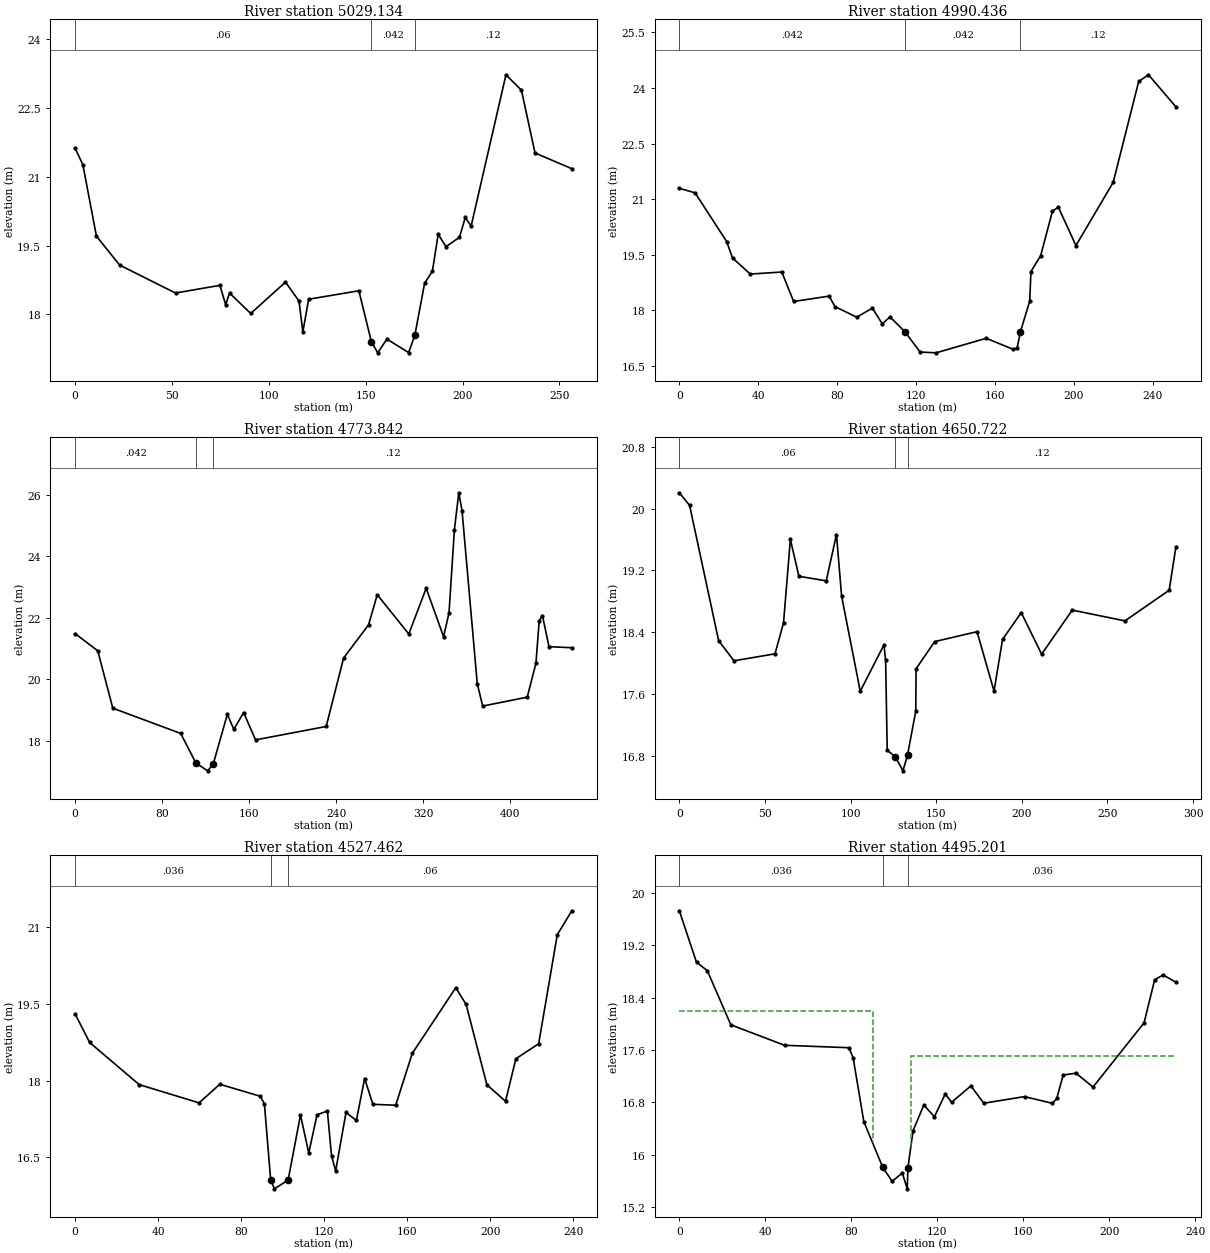
Type RM Length L Ch R = 1 ,5029.134,19.35,19.35,19.35
BEGIN DESCRIPTION:
Section 8
END DESCRIPTION:
Node Name=8
XS GIS Cut Line= 4
280103.1743131415270545.55409078280212.9905607145270469.68944225
280263.4532035485270422.73641931280296.3413668275270379.92087102
#Sta/Elev= 30
       0  21.614   3.984  21.255  10.957  19.705   22.91  19.076  51.795  18.467
  74.705  18.634  77.693  18.214  79.685  18.467  90.642  18.022 108.571  18.705
 115.544  18.294 117.536  17.622 120.524  18.332  146.46  18.516  152.9317.40534
 156.211  17.166 160.931  17.465 172.148  17.172  175.3417.54627 180.424  18.684
  184.42   18.94 187.417  19.746 191.413  19.476 198.406  19.678 201.403  20.112
 204.401  19.921 222.398  23.214 230.396  22.878 237.395  21.513 256.391  21.172
#Mann= 3 , 0 , 0
       0     .06       0  152.93    .042       0  175.34     .12       0
Bank Sta=152.93,175.34
XS Rating Curve= 0 ,0
Exp/Cntr=0.3,0.1

Type RM Length L Ch R = 1 ,4990.436,24.07,24.07,24.07
BEGIN DESCRIPTION:
Section 9
END DESCRIPTION:
Node Name=9
XS GIS Cut Line= 4
 280134.58009247  5270568.355547280212.2964044955270512.21838797
280299.5517162145270448.43891012280332.9097400215270414.33816344
#Sta/Elev= 30
       0  21.289   7.989  21.168  23.968  19.852  26.964  19.407  35.952  18.973
   51.93  19.028  57.922  18.233  75.898  18.377  78.894  18.094  89.879  17.808
  97.854  18.053 102.812   17.63 106.778  17.815  114.2217.42065 122.017  16.867
 130.084  16.845 155.522  17.238 169.129  16.941 171.187  16.976  172.8717.42072
 177.561  18.243  178.17   19.04 183.128  19.474 189.078  20.674 192.052   20.78
 200.976  19.744 219.852  21.451 232.772  24.176 237.741  24.357 251.654  23.489
#Mann= 3 , 0 , 0
       0    .042       0  114.22    .042       0  172.87     .12       0
Bank Sta=114.22,172.87
XS Rating Curve= 0 ,0
Exp/Cntr=0.3,0.1

Type RM Length L Ch R = 1 ,4773.842,24.62,24.62,24.62
BEGIN DESCRIPTION:
Section 10
END DESCRIPTION:
Node Name=10
XS GIS Cut Line= 4
280316.8324029625270732.46707628280370.6936636935270671.92322421
280426.127656044  5270600.035326 280593.190513925270369.42837701
#Sta/Elev= 30
       0  21.481  20.753  20.923  34.588  19.054  96.996  18.232  110.9717.26892
 121.828  17.014  126.9917.24531 139.891  18.852 145.876  18.365 154.855  18.913
 165.828  18.022 230.764  18.459  246.75  20.686 269.731  21.769 277.725  22.748
 306.701  21.469 322.688  22.958 338.674  21.384  343.67  22.151 348.666  24.871
 352.663  26.068  355.66  25.485 369.649  19.856 374.645  19.123 415.611  19.413
 423.604  20.518 426.602  21.897 429.599  22.069 435.595  21.058 456.577  21.022
#Mann= 3 , 0 , 0
       0    .042       0  110.97    .042       0  126.99     .12       0
Bank Sta=110.97,126.99
XS Rating Curve= 0 ,0
Exp/Cntr=0.3,0.1

Type RM Length L Ch R = 1 ,4650.722,24.65,24.65,24.65
BEGIN DESCRIPTION:
Section 11
END DESCRIPTION:
Node Name=11
XS GIS Cut Line= 4
280408.6755851325270777.49636719280481.7863438195270714.11417964
280536.1377770565270665.19788972280623.7836627355270583.03866504
#Sta/Elev= 30
       0  20.205   5.985  20.042  22.943  18.289  31.921  18.028  55.861  18.118
  60.849  18.519  64.839  19.601  69.827  19.123  85.787  19.064  91.772  19.664
  94.765  18.865 105.653  17.633 119.487  18.234 120.475  18.032   121.4  16.867
  126.1916.78418 130.588  16.602  133.2516.80567 138.071  17.375 138.262  17.925
 149.132  18.277 173.854  18.405 183.782  17.635 188.746  18.305 199.667  18.652
 211.581  18.114 229.452  18.685  260.23  18.545 286.044  18.942 290.015  19.506
#Mann= 3 , 0 , 0
       0     .06       0  126.19    .042       0  133.25     .12       0
Bank Sta=126.19,133.25
XS Rating Curve= 0 ,0
Exp/Cntr=0.3,0.1

Type RM Length L Ch R = 1 ,4527.462,16.13,16.13,16.13
BEGIN DESCRIPTION:
Section 12
END DESCRIPTION:
Node Name=12
XS GIS Cut Line= 4
280469.4936318965270843.45930345280521.2268582815270815.69005693
280595.2157189425270774.37960973280672.1732427935270717.26256459
#Sta/Elev= 30
       0  19.299   6.966  18.744   30.85  17.921  59.712  17.564  69.681  17.928
  89.036  17.695  91.167   17.55    94.2 16.0559  95.987  15.884   102.6  16.055
 108.562  17.326  112.55  16.584 116.538  17.333 121.522  17.403 123.516  16.531
  125.51  16.234 130.495  17.376  135.48   17.22 139.467   18.04 143.455  17.536
 154.437  17.518 162.423  18.531 183.387  19.815 188.379  19.487 198.362  17.919
 207.347  17.595 212.338  18.426  223.32  18.719 232.304  20.851 239.293  21.318
#Mann= 3 , 0 , 0
       0    .036       0    94.2    .036       0   102.6     .06       0
Bank Sta=94.2,102.6
XS Rating Curve= 0 ,0
Exp/Cntr=0.3,0.1

Type RM Length L Ch R = 1 ,4495.201,18.84,18.84,18.84
BEGIN DESCRIPTION:
Section 13
END DESCRIPTION:
Node Name=13
XS GIS Cut Line= 6
280485.8752244425270858.99914381280549.1776164115270829.36424114
 280591.957136425270816.00868368280628.5758623975270811.57395387
280658.3066750095270807.68587123 280701.222311025270783.11379422
#Sta/Elev= 30
       0  19.725   7.988  18.938  12.981  18.812  23.964  17.983  48.927   17.67
  78.859  17.633  80.851   17.48   85.83  16.504   94.6615.80346  98.996  15.592
 103.731  15.718 106.042  15.477  106.3515.80235 108.736  16.365 113.716  16.756
 118.699  16.579 123.684  16.926 126.675    16.8 135.647   17.05 141.629  16.785
 160.593  16.886 173.586  16.783 175.585  16.859 178.584  17.216 184.549  17.244
 192.462  17.032 216.199  18.013 221.144  18.673   225.1  18.744 231.034  18.633
#Mann= 3 , 0 , 0
       0    .036       0   94.66    .036       0  106.35    .036       0
#XS Ineff= 2 , 0
       0    89.9    18.2   107.7       0    17.5
Permanent Ineff=
       F       F
Bank Sta=94.66,106.35
XS Rating Curve= 0 ,0
Exp/Cntr=0.5,0.3

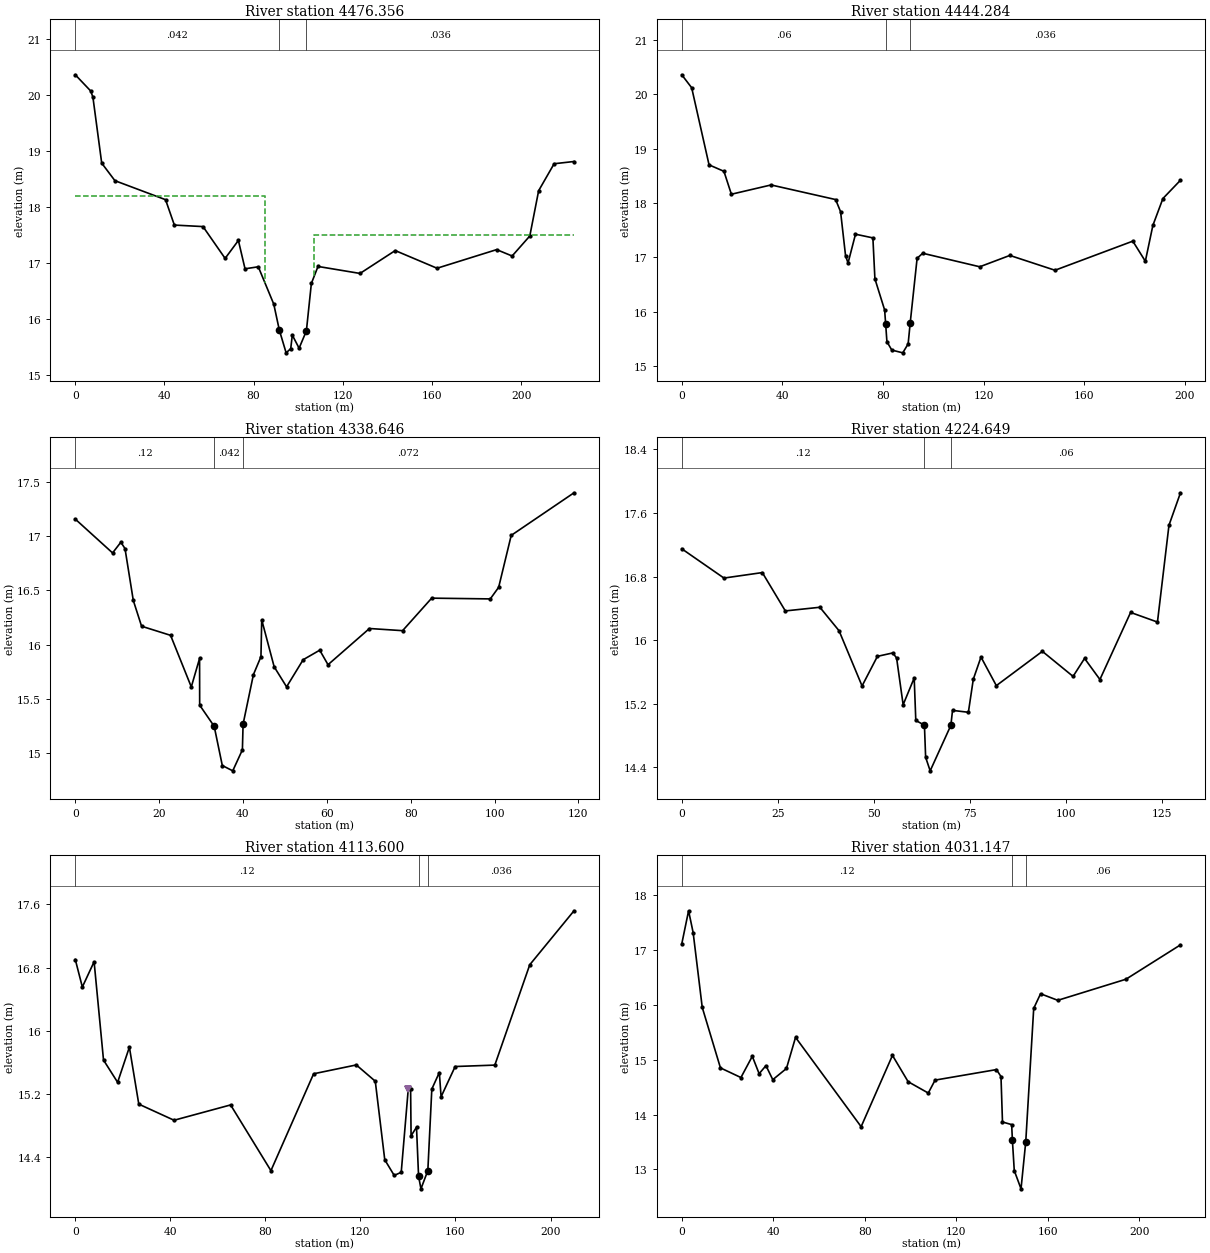
Type RM Length L Ch R = 1 ,4476.356,16.03,16.03,16.03
BEGIN DESCRIPTION:
Section 14
END DESCRIPTION:
Node Name=14
XS GIS Cut Line= 5
280496.7358473435270875.45409125280544.0596244165270848.78068963
280615.8615535035270829.26105511280656.7762570795270822.53750416
280705.820898775 5270801.0266964
#Sta/Elev= 30
       0  20.369   6.914  20.079   7.902   19.97  11.852  18.789  17.779  18.475
  40.495  18.135  44.446  17.681  57.299  17.654  67.221  17.085  73.173  17.406
  76.149  16.899  82.102  16.935  89.047  16.267   91.5415.80334   94.59  15.396
  96.654  15.471  97.364  15.713  100.41  15.479  103.6815.78834 105.913  16.637
 108.889  16.941 127.739  16.816 143.539  17.225 162.297  16.909 189.038  17.242
  195.98  17.128 203.914  17.486 207.881  18.296 214.823  18.778 223.749  18.818
#Mann= 3 , 0 , 0
       0    .042       0   91.54    .036       0  103.68    .036       0
#XS Ineff= 2 , 0
       0    85.1    18.2   107.2       0    17.5
Permanent Ineff=
       F       F
Bank Sta=91.54,103.68
XS Rating Curve= 0 ,0
Exp/Cntr=0.5,0.3

Type RM Length L Ch R = 1 ,4444.284,21.13,21.13,21.13
BEGIN DESCRIPTION:
Section 15
END DESCRIPTION:
Node Name=15
XS GIS Cut Line= 4
280537.3243790355270915.85512201280579.2393628745270881.39637454
280631.4159781775270842.26391306280702.9575987895270809.16151552
#Sta/Elev= 30
       0   20.36   3.946  20.121  10.852  18.701  16.772  18.582  19.731   18.16
  35.516  18.331  61.178  18.062  63.155  17.838  65.131  17.028  66.119  16.893
  69.084  17.424  76.001  17.356  76.806  16.602  80.673  16.028   81.0815.76939
   81.58  15.444  83.523   15.29  87.885  15.239  90.019  15.404   90.8515.79611
  93.588  16.981  95.823  17.073 118.493  16.824 130.458  17.033 148.419   16.76
 179.352  17.296 184.341  16.926 187.334  17.586 191.326  18.081  198.31  18.418
#Mann= 3 , 0 , 0
       0     .06       0   81.08    .036       0   90.85    .036       0
Bank Sta=81.08,90.85
XS Rating Curve= 0 ,0
Exp/Cntr=0.3,0.1

Type RM Length L Ch R = 1 ,4338.646,22.8,22.8,22.8
BEGIN DESCRIPTION:
Section 16
END DESCRIPTION:
Node Name=16
XS GIS Cut Line= 3
280662.9861696515270947.21254558280726.8982214045270894.25046074
280752.8626727945270869.39177725
#Sta/Elev= 30
       0  17.158   8.893  16.846   10.87  16.945  11.858  16.886  13.834  16.408
   15.81   16.17  22.727  16.086  27.668   15.61  29.644  15.873  29.666  15.442
   33.1315.24687  35.065  14.885  37.554  14.836  39.858   15.03   40.0215.26695
  42.487  15.724  44.282  15.889  44.467  16.229  47.431  15.796  50.396  15.611
  54.348  15.861  58.301  15.949  60.277  15.815  70.159  16.149  78.064  16.129
  85.001  16.429   98.98  16.422 100.977  16.529 103.973  17.008  118.95  17.401
#Mann= 3 , 0 , 0
       0     .12       0   33.13    .042       0   40.02    .072       0
Bank Sta=33.13,40.02
XS Rating Curve= 0 ,0
Exp/Cntr=0.3,0.1

Type RM Length L Ch R = 1 ,4224.649,22.21,22.21,22.21
BEGIN DESCRIPTION:
Section 17
END DESCRIPTION:
Node Name=17
XS GIS Cut Line= 2
280756.5132977445271056.72756873280795.9081223475270933.07159151
#Sta/Elev= 30
       0  17.149  10.981  16.781  20.964   16.85  26.954  16.368  35.939  16.414
  40.931  16.119   46.92  15.425  50.914  15.797  54.907   15.84  55.905  15.777
  57.609  15.189  60.486  15.525  60.905  14.991   63.1514.93203  63.463  14.528
  64.644  14.358   70.0314.93007  70.461  15.118  74.586  15.094  75.871   15.51
  77.868  15.788  81.861  15.429  93.841   15.86 101.827  15.545 104.822  15.771
 108.815  15.506 116.802  16.349  123.79  16.228 126.785  17.445  129.78  17.853
#Mann= 3 , 0 , 0
       0     .12       0   63.15    .036       0   70.03     .06       0
Bank Sta=63.15,70.03
XS Rating Curve= 0 ,0
Exp/Cntr=0.3,0.1

Type RM Length L Ch R = 1 ,4113.600,20.61,20.61,20.61
BEGIN DESCRIPTION:
Section 18
END DESCRIPTION:
Node Name=18
XS GIS Cut Line= 5
280830.5405897065271129.90359316280867.2523682835271081.97432669
 280885.60658149 5271012.4938833280881.6055446165270980.17781624
280892.2065824885270936.35449356
#Sta/Elev= 30
       0  16.901   2.969  16.553   7.918  16.873  11.877  15.629  17.815  15.347
  22.764  15.792  26.723  15.071  41.569  14.867  65.364  15.061  82.332  14.229
 100.298  15.455 118.264  15.567 126.249  15.361 130.241  14.367 134.211  14.169
 137.171  14.208 140.131  15.262 141.118  15.267 141.317   14.67 143.601  14.779
  144.4714.15843 145.473  13.999  148.3714.22992 150.047  15.262 153.207  15.471
 153.946  15.164 159.867  15.547 176.562  15.565 191.265  16.835 209.888  17.518
#Mann= 3 , 0 , 0
       0     .12       0  144.47    .042       0  148.37    .036       0
Levee=-1,140.13,15.26,0,,,,
Bank Sta=144.47,148.37
XS Rating Curve= 0 ,0
Exp/Cntr=0.3,0.1

Type RM Length L Ch R = 1 ,4031.147,21.44,21.44,21.44
BEGIN DESCRIPTION:
Section 19
END DESCRIPTION:
Node Name=19
XS GIS Cut Line= 4
280856.7997091065271150.93638297280902.6894323265271101.22251615
280928.2972830965271070.33546286280993.9765460445270981.76797192
#Sta/Elev= 30
       0  17.115   2.985   17.72   4.975  17.323   8.954  15.957  16.914  14.853
  25.868  14.677  30.843  15.065  33.828  14.747  36.813  14.894  39.798  14.638
  45.767  14.842  49.747   15.41   78.42   13.78  92.121  15.081  98.971  14.601
 107.778  14.394 110.758   14.63 137.579  14.822 139.566  14.695 140.222  13.866
 144.239  13.818  144.56 13.5295 145.374  12.979 148.327  12.646  150.3913.50294
 153.875  15.939  156.87  16.206   164.4  16.086 194.201  16.471 218.041  17.098
#Mann= 3 , 0 , 0
       0     .12       0  144.56    .042       0  150.39     .06       0
Bank Sta=144.56,150.39
XS Rating Curve= 0 ,0
Exp/Cntr=0.3,0.1