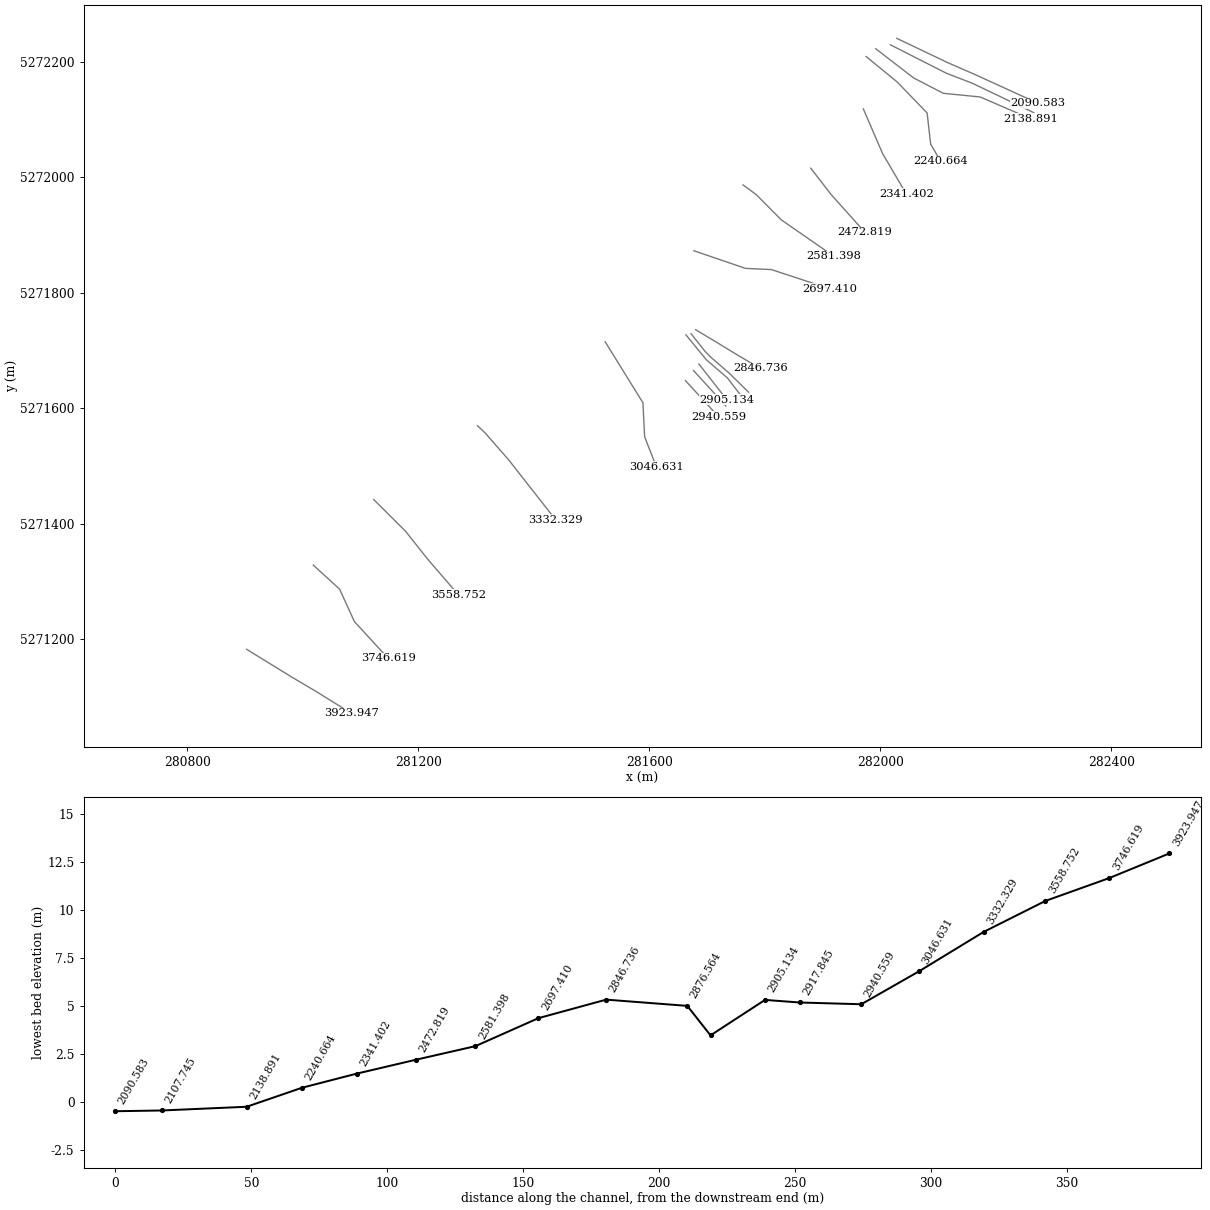
HEC-RAS study ShearstownModel.prj: Shearstown Model

--- ShearstownModel.g02 (geometry) --- (continued)

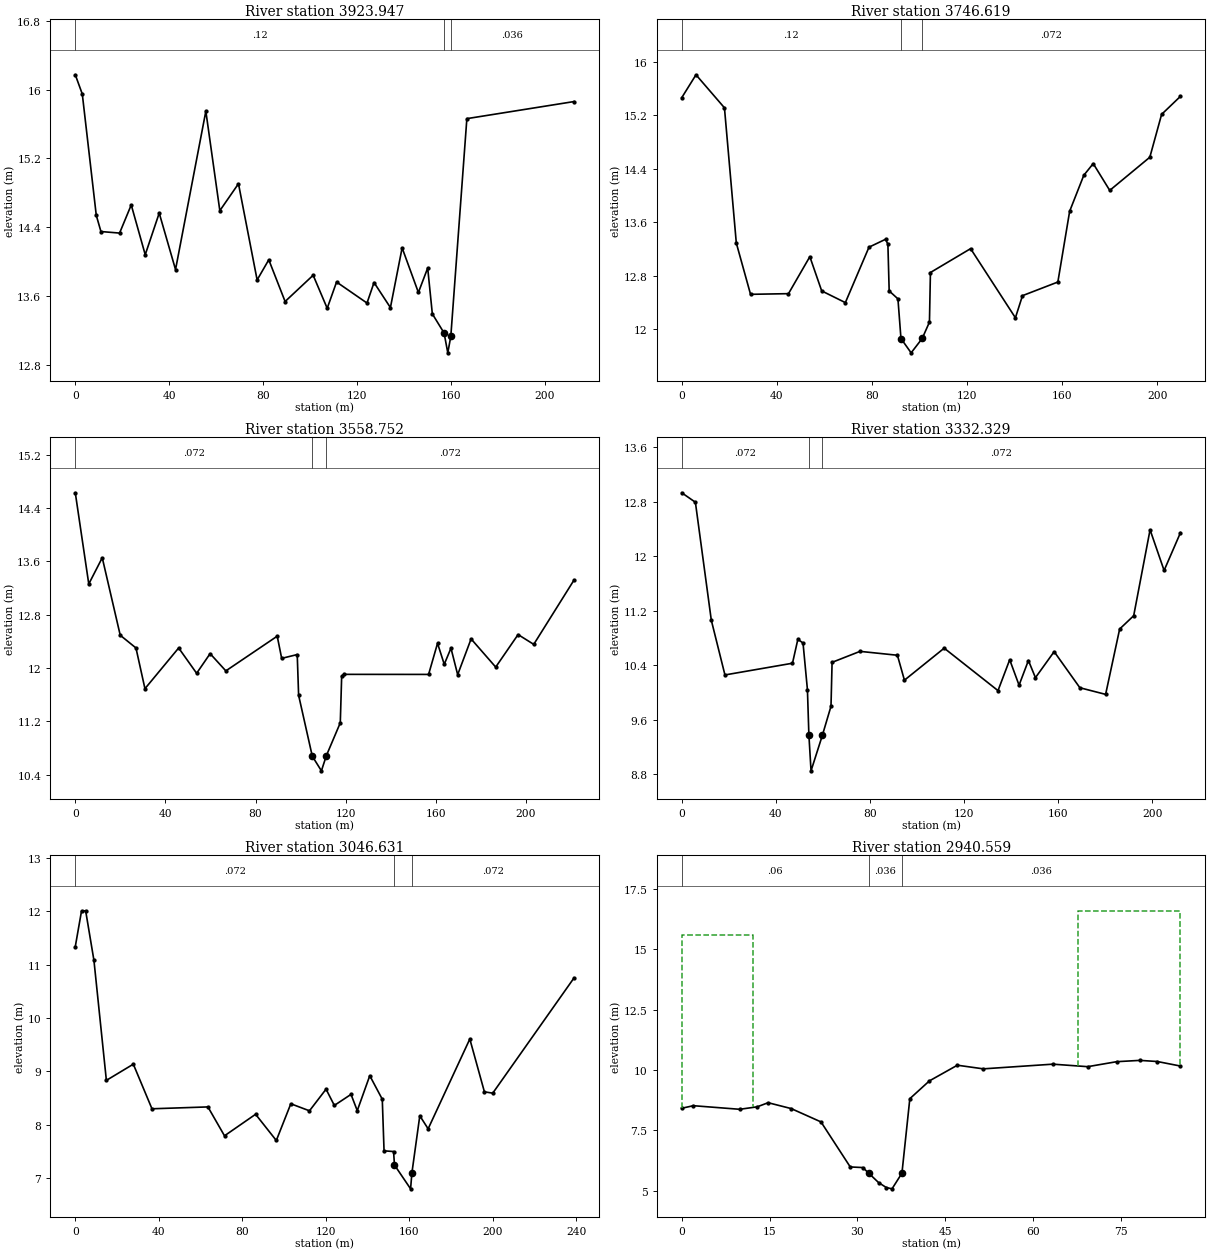
Type RM Length L Ch R = 1 ,3923.947,22.17,22.17,22.17
BEGIN DESCRIPTION:
Section 20
END DESCRIPTION:
Node Name=20
XS GIS Cut Line= 4
280902.9443752335271182.42183196280982.4865621535271133.47279385
281022.8773400025271109.63950305281084.2563524265271071.50062796
#Sta/Elev= 30
       0  16.175   2.981  15.951   8.942  14.538  10.929  14.349  18.878  14.331
  23.846  14.659  29.808  14.079  35.769  14.564  42.724  13.906  55.641  15.751
  61.602  14.592  69.551  14.906    77.5  13.785  82.467   14.02  89.423  13.534
  101.38   13.84 107.367  13.455 111.358  13.761  124.33  13.516 127.323  13.755
 134.308  13.463 139.297  14.159 146.234  13.639 150.194  13.924 152.174   13.39
  157.1813.16694 158.764  12.936  160.0513.12897 166.889  15.664 212.558  15.863
#Mann= 3 , 0 , 0
       0     .12       0  157.18    .042       0  160.05    .036       0
Bank Sta=157.18,160.05
XS Rating Curve= 0 ,0
Exp/Cntr=0.3,0.1

Type RM Length L Ch R = 1 ,3746.619,23.48,23.48,23.48
BEGIN DESCRIPTION:
Section 21
END DESCRIPTION:
Node Name=21
XS GIS Cut Line= 4
281018.3219744885271328.20933981281063.9514491195271286.49049696
281089.5287137515271230.45481033281147.8170372065271166.87828161
#Sta/Elev= 30
       0  15.466   5.983  15.808   17.95  15.314  22.936  13.292  28.919  12.525
  44.874  12.535  53.849  13.088  58.835  12.576  68.781  12.401  78.716   13.23
   85.67  13.348  86.664  13.275  87.204  12.576  90.889  12.457   92.16  11.864
  96.433   11.65  101.0911.86494 104.139   12.11 104.547  12.851 121.436  13.208
 140.277  12.174 143.252  12.505 158.123  12.709  163.08  13.767 169.028  14.305
 172.994   14.48 179.934  14.079 196.788  14.575 201.745  15.216 209.676  15.486
#Mann= 3 , 0 , 0
       0     .12       0   92.16    .042       0  101.09    .072       0
Bank Sta=92.16,101.09
XS Rating Curve= 0 ,0
Exp/Cntr=0.3,0.1

Type RM Length L Ch R = 1 ,3558.752,22.64,22.64,22.64
BEGIN DESCRIPTION:
Section 22
END DESCRIPTION:
Node Name=22
XS GIS Cut Line= 4
281122.9123019975271441.76250389281178.0015779925271386.86962703
281216.6226262515271338.22196047281269.7594163085271276.55950029
#Sta/Elev= 30
       0  14.631   5.982  13.262  11.964  13.656  19.941  12.493   26.92  12.302
  30.908  11.691  45.864  12.302   53.84  11.922  59.822  12.217  66.802  11.958
    89.6  12.479  91.572  12.146  98.474  12.203   99.09  11.592  105.1610.67731
 109.205  10.458  111.3710.68349  117.58  11.179 118.193   11.88 119.179  11.906
 156.759  11.905  160.73  12.372 163.708  12.057 166.686  12.299 169.664  11.901
  175.62  12.438 186.539  12.015 196.466  12.503 203.415  12.356 221.283  13.321
#Mann= 3 , 0 , 0
       0    .072       0  105.16    .036       0  111.37    .072       0
Bank Sta=105.16,111.37
XS Rating Curve= 0 ,0
Exp/Cntr=0.3,0.1

Type RM Length L Ch R = 1 ,3332.329,23.81,23.81,23.81
BEGIN DESCRIPTION:
Section 23
END DESCRIPTION:
Node Name=23
XS GIS Cut Line= 4
281302.6470512845271569.48890019281316.0131277455271556.90190333
281357.0248191265271509.89763604 281438.021734795271406.58038275
#Sta/Elev= 30
       0  12.929   5.798   12.79  12.562  11.059   18.36  10.256  47.075  10.428
  49.359  10.779  51.557  10.724  53.427   10.04   54.049.380342  54.961   8.849
   59.789.370162  63.447   9.797  63.908  10.441   75.79  10.602  91.681  10.545
  94.664  10.179 111.572  10.649 134.447  10.026  139.42  10.479 143.398  10.106
 147.376  10.468  150.36  10.216 158.317  10.598 169.257  10.068 180.197   9.971
 186.164   10.93 192.132  11.125 199.094  12.386 205.061  11.789 212.023  12.344
#Mann= 3 , 0 , 0
       0    .072       0   54.04    .036       0   59.78    .072       0
Bank Sta=54.04,59.78
XS Rating Curve= 0 ,0
Exp/Cntr=0.3,0.1

Type RM Length L Ch R = 1 ,3046.631,21.21,21.21,21.21
BEGIN DESCRIPTION:
Section 24
END DESCRIPTION:
Node Name=24
XS GIS Cut Line= 4
281523.6825514725271714.80635706281589.0722889515271609.27860942
281591.9612526165271550.41597476281612.402683033 5271498.3598292
#Sta/Elev= 30
       0  11.338   2.979  12.004   4.966   12.01   8.938  11.079  14.897   8.828
  27.808   9.132  36.747   8.295  63.562    8.33  71.507   7.788  86.405   8.192
  96.336     7.7 103.288   8.389 112.227   8.257 120.172   8.663 124.145   8.358
 132.136   8.565 135.132    8.26 141.125   8.916 147.119   8.474 147.967   7.506
 152.531   7.493  152.967.240294 160.687   6.793   161.37.087523 165.098   8.164
 169.094   7.919  189.07   9.604 196.061   8.613 200.055   8.588 239.004   10.75
#Mann= 3 , 0 , 0
       0    .072       0  152.96    .036       0   161.3    .072       0
Bank Sta=152.96,161.3
XS Rating Curve= 0 ,0
Exp/Cntr=0.3,0.1

Type RM Length L Ch R = 1 ,2940.559,22.71,22.71,22.71
BEGIN DESCRIPTION:
Section 25
END DESCRIPTION:
Node Name=25
XS GIS Cut Line= 2
281662.7684061165271647.52404718 281720.296479125271584.66070934
#Sta/Elev= 24
       0   8.417   1.982   8.523   9.909   8.374  12.881   8.476  14.759   8.647
  18.694   8.404  23.791   7.851  28.791   5.985  30.936    5.96   31.915.734464
  33.632   5.337  34.948   5.133  35.925   5.078   37.625.726233  38.969   8.814
  42.313   9.551  47.092  10.201  51.524   10.05  63.414  10.244  69.359   10.14
  74.314  10.347  78.277  10.401   81.25  10.354  85.213  10.166
#Mann= 3 , 0 , 0
       0     .06       0   31.91    .036       0   37.62    .036       0
#XS Ineff= 2 , 0
       0    12.2    15.6    67.7       0    16.6
Permanent Ineff=
       F       F
Bank Sta=31.91,37.62
XS Rating Curve= 0 ,0
Exp/Cntr=0.3,0.1

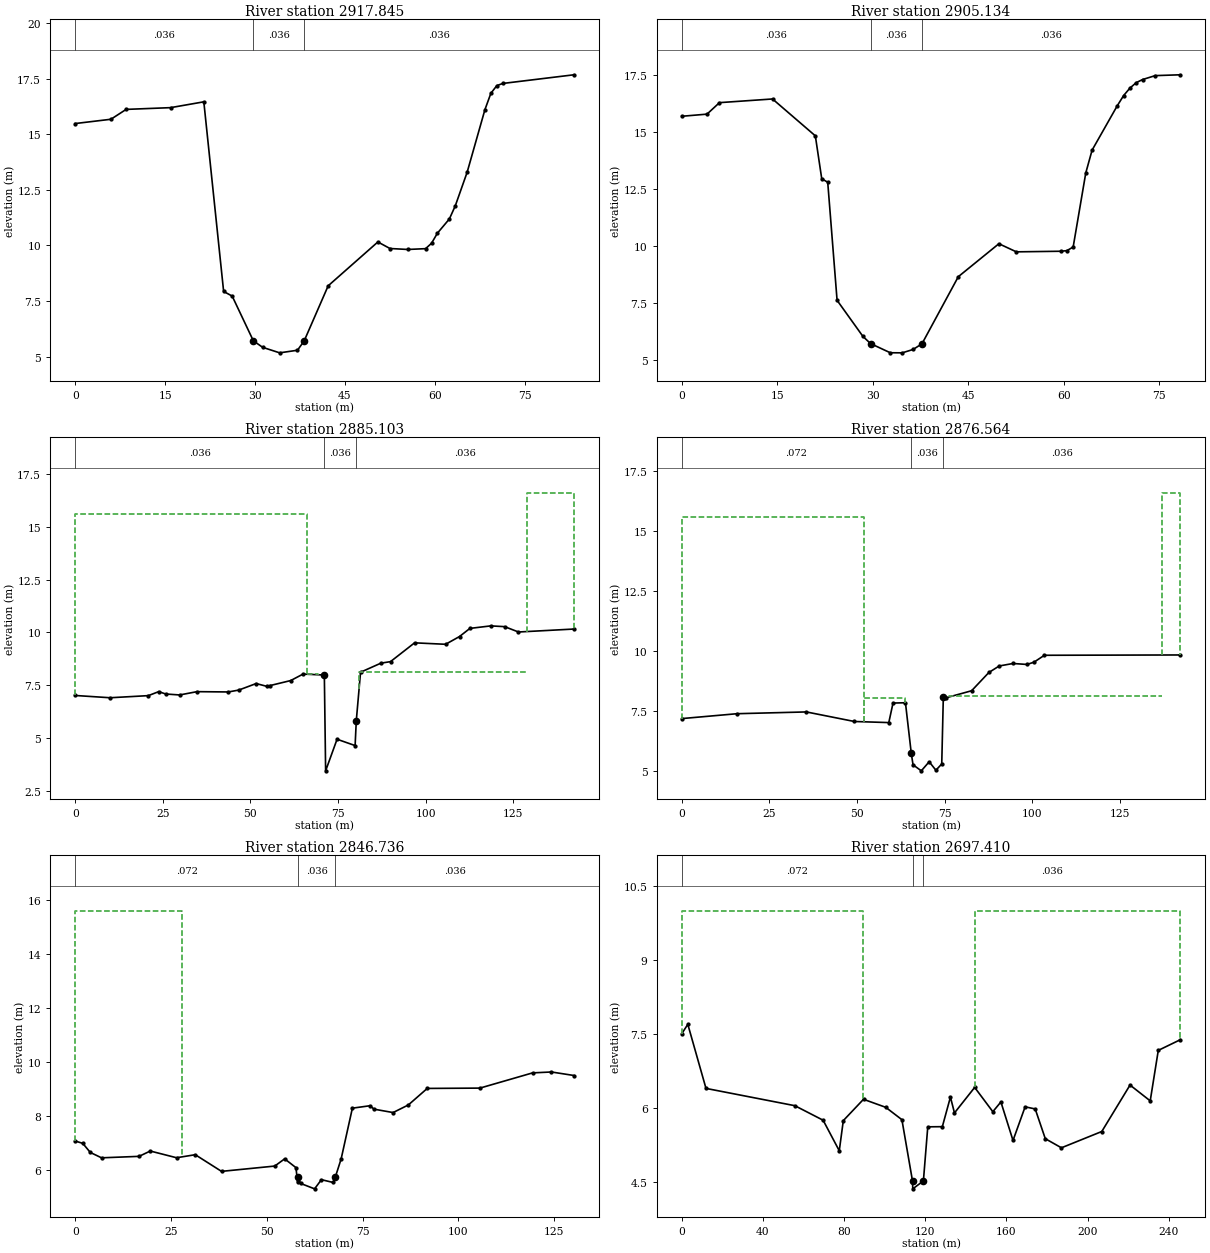
Type RM Length L Ch R = 1 ,2917.845,12.71,12.71,12.71
BEGIN DESCRIPTION:
Section 26
END DESCRIPTION:
Node Name=26
XS GIS Cut Line= 2
281676.5463425575271665.19952909281732.6826073435271603.72799947
#Sta/Elev= 27
       0  15.479   5.946  15.671   8.491  16.115  15.905  16.193  21.454  16.455
  24.761   7.929   26.19    7.72   29.725.711139  31.271   5.417  34.113   5.169
  37.088   5.286   38.215.708624  42.212   8.183  50.506  10.154  52.525    9.86
  55.498   9.817  58.471   9.853  59.462  10.095  60.453  10.552  62.435  11.186
  63.426  11.776  65.408  13.289  68.381  16.107  69.372  16.839  70.363  17.184
  71.354  17.281  83.247  17.671
#Mann= 3 , 0 , 0
       0    .036       0   29.72    .036       0   38.21    .036       0
Bank Sta=29.72,38.21
XS Rating Curve= 0 ,0
Exp/Cntr=0.5,0.3

Type RM Length L Ch R = 1 ,2905.134,20.03,20.03,20.03
BEGIN DESCRIPTION:
Section 27
END DESCRIPTION:
Node Name=27
XS GIS Cut Line= 2
281685.9660138415271676.38151417281734.2153653925271614.67801652
#Sta/Elev= 29
       0  15.678   3.966  15.772   5.922  16.276  14.256  16.437  20.981   14.82
  21.984  12.939  22.926  12.785  24.395   7.607  28.449   6.027   29.655.710056
  32.748   5.308  34.626   5.304  36.337   5.452   37.735.701284  43.433   8.643
   49.81  10.089  52.549   9.733   59.49   9.759  60.481   9.785  61.473   9.944
  63.456  13.196  64.447  14.194  68.413  16.146  69.405  16.589  70.396  16.917
  71.388  17.154  72.379   17.29  74.362  17.461  78.328  17.498
#Mann= 3 , 0 , 0
       0    .036       0   29.65    .036       0   37.73    .036       0
Bank Sta=29.65,37.73
XS Rating Curve= 0 ,0
Exp/Cntr=0.5,0.3

Type RM Length L Ch R = 1 ,2885.103,8.54,8.54,8.54
BEGIN DESCRIPTION:
Section 28
END DESCRIPTION:
Node Name=28
XS GIS Cut Line= 4
281663.4211472265271727.01063834281698.5871832425271683.95808113
  281735.05055685271652.55321026281758.6253066855271621.95777274
#Sta/Elev= 30
       0   7.018   9.927   6.911  20.846   7.011  23.824   7.201  25.809   7.088
   29.78   7.043  34.743   7.199  43.677   7.185  46.655   7.274  51.619   7.582
  54.597   7.453  55.589   7.487  61.482   7.724  65.005    8.03   71.087.984998
  71.447   3.456   74.71    4.95  79.861    4.65    80.25.831645  81.414   8.117
  87.219   8.546  89.963   8.618  96.838   9.507 105.693   9.438 109.655   9.805
 112.626  10.189 118.568  10.308  122.53  10.272 126.491  10.019 142.337  10.159
#Mann= 3 , 0 , 0
       0    .036       0   71.08    .036       0    80.2    .036       0
#XS Ineff= 4 ,-1
       0    66.2    15.6    66.2    69.3    8.02      81   128.9    8.12
   128.9 142.337    16.6
Permanent Ineff=
       F       F       F       F
Bank Sta=71.08,80.2
XS Rating Curve= 0 ,0
Exp/Cntr=0.5,0.3

Type RM Length L Ch R = 1 ,2876.564,29.83,29.83,29.83
BEGIN DESCRIPTION:
Section 29
END DESCRIPTION:
Node Name=29
XS GIS Cut Line= 5
281672.4356023655271728.71687912281697.0345774455271697.80007641
281705.9319163445271688.74825644281738.640594693 5271660.3228574
281772.0169645545271627.49406591
#Sta/Elev= 23
       0   7.174  15.804   7.378  35.558   7.452  49.272   7.053  59.096   7.007
    60.3   7.823  63.849   7.835   65.515.728192  66.012   5.246  68.371   4.993
  70.624   5.372  72.539   5.018  74.209    5.28   74.668.079876  75.505   8.045
  82.732   8.336  87.657   9.098  90.611    9.37  94.551   9.474  98.524   9.434
 100.516   9.527 103.504   9.817 142.351    9.83
#Mann= 3 , 0 , 0
       0    .072       0   65.51    .036       0   74.66    .036       0
#XS Ineff= 4 ,-1
       0    52.1    15.6    52.1    63.7    8.02    76.2   137.2    8.12
   137.2 142.351    16.6
Permanent Ineff=
       F       F       F       F
Bank Sta=65.51,74.66
XS Rating Curve= 0 ,0
Exp/Cntr=0.5,0.3

Type RM Length L Ch R = 1 ,2846.736,24.888,24.888,24.888
BEGIN DESCRIPTION:
Section 30
END DESCRIPTION:
Node Name=30
XS GIS Cut Line= 4
 281680.233430175271735.71964238281715.5231032895271714.65743861
281755.4997334125271690.28921387281791.9269256295271668.92040731
#Sta/Elev= 30
       0   7.086   1.957   6.999   3.914   6.664    6.85   6.465  16.635   6.519
   19.57   6.716   26.42   6.468  31.312    6.58  38.162   5.964  52.055    6.16
  54.636   6.427  57.582   6.102  58.022    5.56   58.145.737496  58.781   5.519
  62.447   5.318  64.228   5.657  67.309   5.553   67.845.744213  69.382   6.427
   72.31   8.301  76.909   8.391  77.954   8.264  82.935   8.139  86.919    8.42
  91.844   9.031 105.594   9.043 119.344   9.606 124.255   9.639 130.148   9.509
#Mann= 3 , 0 , 0
       0    .072       0   58.14    .036       0   67.84    .036       0
#XS Ineff= 2 , 0
       0    27.8    15.6               0
Permanent Ineff=
       F       F
Bank Sta=58.14,67.84
XS Rating Curve= 0 ,0
Exp/Cntr=0.3,0.1

Type RM Length L Ch R = 1 ,2697.410,23.204,23.204,23.204
BEGIN DESCRIPTION:
Section 31
END DESCRIPTION:
Node Name=31
XS GIS Cut Line= 4
281677.1962889735271872.48804698281766.6609145565271841.93035098
281811.4472147355271839.87253868281912.5245258745271806.66497523
#Sta/Elev= 30
       0   7.504   2.985   7.695  11.942   6.394  55.728   6.043  69.661   5.748
  77.622   5.128  79.612    5.74  89.564   6.173 100.517    6.01 108.487   5.759
  113.714.514509 113.847   4.355  119.084.516115 121.232   5.614 128.413   5.617
 132.399   6.218 134.391   5.896 144.344   6.414 153.293   5.921 157.271   6.119
 163.237   5.337 169.203    6.02 174.174   5.977 179.146   5.373   187.1   5.188
 206.987   5.519 220.907   6.462 230.851   6.141 234.828   7.166 245.765   7.384
#Mann= 3 , 0 , 0
       0    .072       0  113.71    .036       0  119.08    .036       0
#XS Ineff= 2 , 0
       0   89.56      10  144.34       0      10
Permanent Ineff=
       F       F
Bank Sta=113.71,119.08
XS Rating Curve= 0 ,0
Exp/Cntr=0.3,0.1

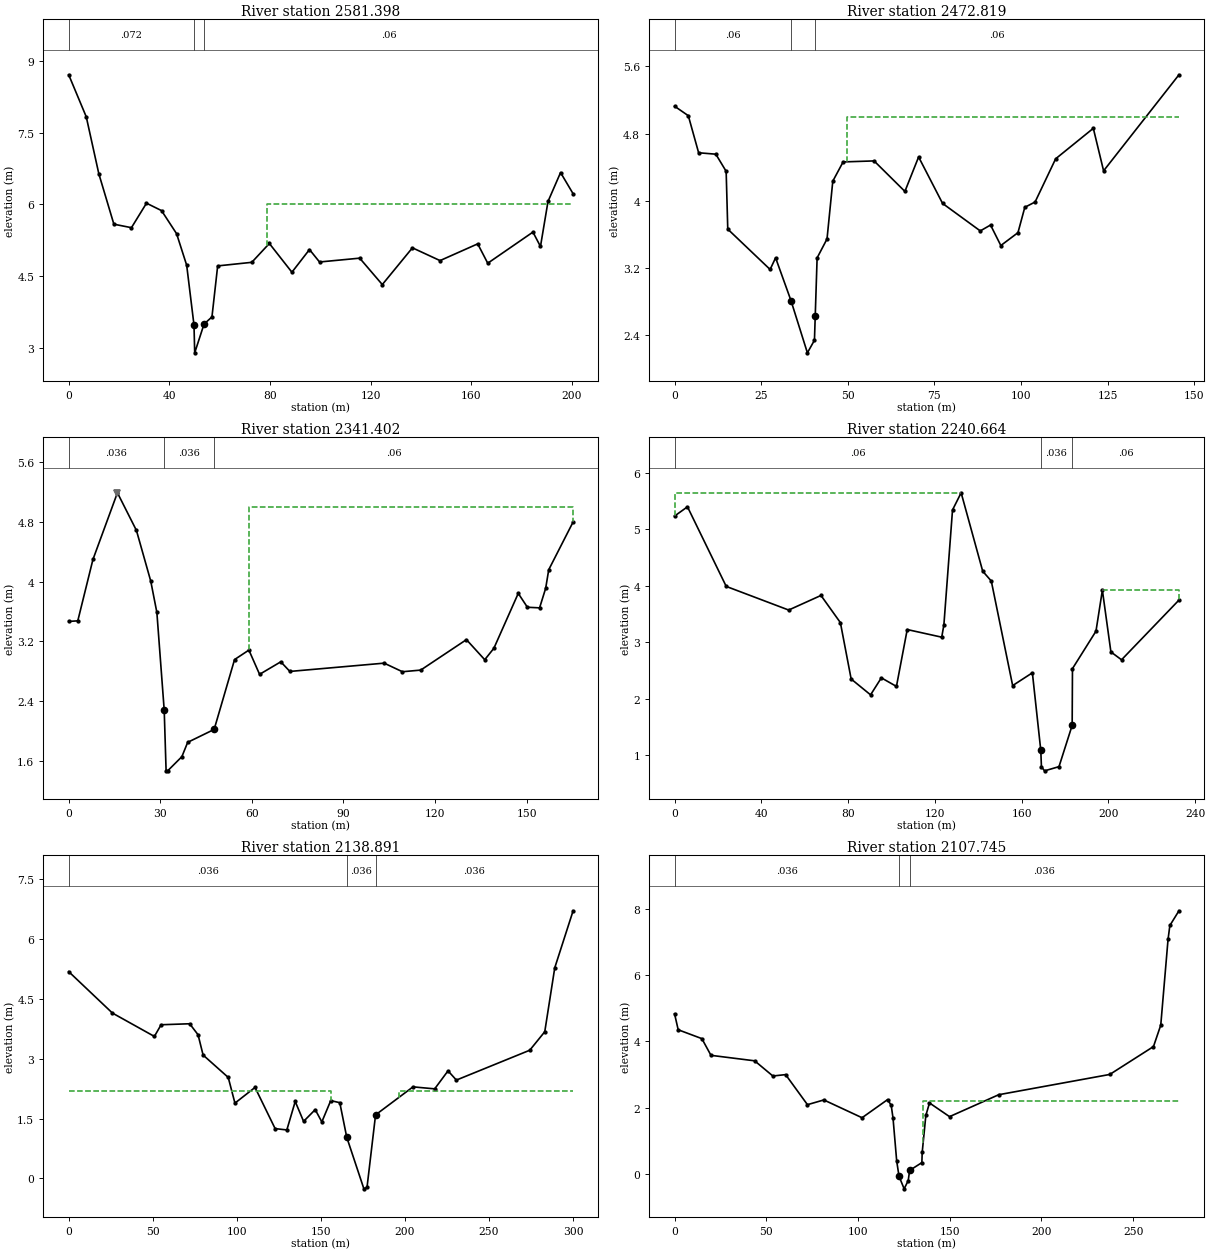
Type RM Length L Ch R = 1 ,2581.398,21.714,21.714,21.714
BEGIN DESCRIPTION:
Section 32
END DESCRIPTION:
Node Name=32
XS GIS Cut Line= 4
281762.3790877045271986.49532811281785.6393316475271969.31496042
281828.3935840355271926.11765878281919.4079843555271863.02329156
#Sta/Elev= 30
       0   8.707    6.98   7.828  11.966   6.639  17.949   5.584  24.929   5.511
   30.91   6.023  36.888   5.868  42.866   5.386  46.883   4.726   49.793.474867
  50.071   2.895   53.793.497486  56.924   3.645  59.195   4.712  72.757   4.787
  79.731   5.181  88.699    4.58  95.681   5.054  99.672   4.794 115.635   4.874
 124.614   4.322 136.587    5.09 147.562   4.823 162.527   5.173 166.518   4.768
 184.477   5.419  187.47   5.118 190.463   6.059 195.452   6.663 200.441    6.22
#Mann= 3 , 0 , 0
       0    .072       0   49.79    .036       0   53.79     .06       0
#XS Ineff= 2 , 0
       0   30.91       6   78.74       0       6
Permanent Ineff=
       F       F
Bank Sta=49.79,53.79
XS Rating Curve= 0 ,0
Exp/Cntr=0.3,0.1

Type RM Length L Ch R = 1 ,2472.819,21.903,21.903,21.903
BEGIN DESCRIPTION:
Section 33
END DESCRIPTION:
Node Name=33
XS GIS Cut Line= 3
281879.6585200585272015.30936874281914.9048153265271969.74708461
281973.615219914 5271904.1627114
#Sta/Elev= 30
       0   5.127   3.973   5.014   6.952   4.573  11.918   4.556  14.898   4.352
  15.364   3.664   27.59   3.184  29.171   3.323   33.612.814229  38.354   2.192
  40.391   2.342   40.622.634443  41.159   3.322  44.019   3.547  45.686   4.235
  48.665   4.464  57.604   4.476  66.505   4.113  70.461   4.523  77.385    3.97
  88.264   3.643  91.231   3.713  94.198   3.469  99.144   3.622 101.122   3.924
 104.089   3.987 110.023   4.501 120.902   4.864 123.869   4.358 145.628   5.501
#Mann= 3 , 0 , 0
       0     .06       0   33.61    .036       0   40.62     .06       0
#XS Ineff= 2 , 0
       0                   49.66       0       5
Permanent Ineff=
       F       F
Bank Sta=33.61,40.62
XS Rating Curve= 0 ,0
Exp/Cntr=0.3,0.1

Type RM Length L Ch R = 1 ,2341.402,20.15,20.15,20.15
BEGIN DESCRIPTION:
Section 34
END DESCRIPTION:
Node Name=34
XS GIS Cut Line= 3
281970.5899902895272118.18719284282003.9933875175272040.70986871
 282044.92354764 5271970.9537695
#Sta/Elev= 30
       0   3.466   2.978   3.474   7.941   4.296  15.963    5.19  22.194   4.685
  26.887   4.005  28.886   3.586   31.292.276762  31.906   1.468  32.422   1.464
  37.079   1.654  38.978   1.846   47.65 2.01894  54.337   2.955  59.033   3.082
  62.534   2.757  69.482   2.925   72.46   2.796 103.343   2.907 109.334   2.792
 115.325   2.814 130.302   3.222 136.293   2.953 139.288   3.106 147.276   3.842
 150.272   3.656 154.266   3.648 156.263   3.911 157.261   4.159 165.249   4.799
#Mann= 3 , 0 , 0
       0    .036       0   31.29    .036       0   47.65     .06       0
Levee=-1,15.96,5.19,0,,,,
#XS Ineff= 2 , 0
       0                   59.03       0       5
Permanent Ineff=
       F       F
Bank Sta=31.29,47.65
XS Rating Curve= 0 ,0
Exp/Cntr=0.3,0.1

Type RM Length L Ch R = 1 ,2240.664,20.35,20.35,20.35
BEGIN DESCRIPTION:
Section 35
END DESCRIPTION:
Node Name=35
XS GIS Cut Line= 5
281975.5868314815272208.67004968282029.3014879045272164.60013532
282081.0963429695272110.97575028 282087.181513565272057.15711371
282104.4009310975272027.47341689
#Sta/Elev= 30
       0   5.233   5.955   5.397  23.822   3.989  52.606   3.571  67.494   3.829
  76.438   3.349  81.408   2.351  90.355   2.071  95.325   2.372 102.283    2.22
 107.253   3.226 123.158   3.091 124.152   3.309 128.129   5.341 132.105   5.645
 142.045   4.258 146.003   4.084  155.85   2.235 164.941   2.461  168.821.088044
 169.116    .797 170.577    .727 177.211    .801  183.281.531658 183.424   2.535
 194.256   3.197  197.21   3.922 201.136    2.83 206.039   2.691 232.511   3.747
#Mann= 3 , 0 , 0
       0     .06       0  168.82    .036       0  183.28     .06       0
#XS Ineff= 2 , 0
       0   132.1    5.64  197.21       0    3.92
Permanent Ineff=
       F       F
Bank Sta=168.82,183.28
XS Rating Curve= 0 ,0
Exp/Cntr=0.3,0.1

Type RM Length L Ch R = 1 ,2138.891,31.14,31.14,31.14
BEGIN DESCRIPTION:
Section 36
END DESCRIPTION:
Node Name=36
XS GIS Cut Line= 5
281992.1013963195272222.21199284282057.8079421335272171.61362078
 282109.104620875272145.06449802282172.8661179475272138.71636405
282260.2979292715272100.99508694
#Sta/Elev= 30
       0   5.186  25.978   4.147  50.958    3.56  54.954   3.853   71.94   3.878
  76.936   3.602  79.933   3.093  94.881   2.532  98.865   1.887 110.815   2.281
 122.765   1.248 129.736   1.214 134.716   1.928 139.695   1.429 146.606   1.724
 150.549   1.416 155.844    1.95 161.227   1.898  165.361.031523 175.559   -.263
 177.417   -.227   182.51.592167 204.767   2.295 217.662   2.245 225.597   2.697
 230.557   2.465   274.2   3.214 283.127   3.678 289.078   5.283 299.989   6.712
#Mann= 3 , 0 , 0
       0    .036       0  165.36    .036       0   182.5    .036       0
#XS Ineff= 2 , 0
       0  155.84     2.2   196.3       0     2.2
Permanent Ineff=
       F       T
Bank Sta=165.36,182.5
XS Rating Curve= 0 ,0
Exp/Cntr=0.3,0.1

Type RM Length L Ch R = 1 ,2107.745,17.16,17.16,17.16
BEGIN DESCRIPTION:
Section 37
END DESCRIPTION:
Node Name=37
XS GIS Cut Line= 4
282017.5834106175272228.98007362282114.9336695655272179.56965854
282159.4577391465272162.45997242282265.9624657695272111.39637198
#Sta/Elev= 30
       0   4.837   1.985   4.354  14.887   4.086  19.849   3.581  43.669   3.415
  53.593   2.956  60.541   2.998   72.45   2.089  81.383   2.232 102.224   1.694
 116.128   2.242 118.115   2.069 119.109   1.679 121.096    .389  122.37   -.077
 125.173   -.456 127.385   -.206  128.16    .101 134.826    .337 135.008    .645
 136.996   1.763 138.983   2.141 149.914   1.727 176.721    2.39 237.267   3.003
 261.088   3.846 265.058   4.494 269.029   7.086 270.021   7.507 274.984   7.952
#Mann= 3 , 0 , 0
       0    .036       0  122.37    .036       0  128.16    .036       0
#XS Ineff= 2 , 0
       0   115.1     2.2   135.5       0     2.2
Permanent Ineff=
       T       T
Bank Sta=122.37,128.16
XS Rating Curve= 0 ,0
Exp/Cntr=0.5,0.3

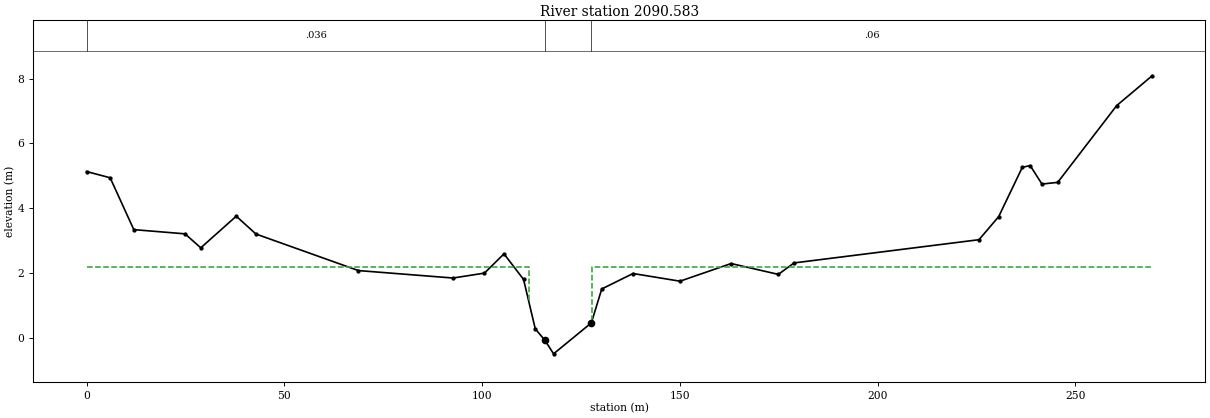
Type RM Length L Ch R = 1 ,2090.583,24.71,24.71,24.71
BEGIN DESCRIPTION:
Section 38
END DESCRIPTION:
Node Name=38
XS GIS Cut Line= 4
282028.5039556975272240.22521369282117.5327028165272197.75754502
282163.7804068235272177.67630512 282273.24980658 5272127.5958815
#Sta/Elev= 30
       0   5.133   5.978    4.94  11.956   3.339  24.909   3.209  28.894   2.777
  37.861   3.754  42.843   3.203  68.748   2.075  92.661   1.845 100.616   1.996
 105.559   2.591 110.502   1.803 113.468    .276  115.91   -.079 118.093   -.496
  127.65.4602455 130.275   1.507 138.184   1.984 150.053   1.747 162.987   2.292
 174.925   1.957 178.905   2.311 225.665   3.028 230.639    3.74 236.609   5.261
 238.598   5.318 241.583   4.746 245.563   4.798 260.486   7.169  269.44   8.089
#Mann= 3 , 0 , 0
       0    .036       0  115.91    .036       0  127.65     .06       0
#XS Ineff= 2 , 0
       0   111.9     2.2   127.8       0     2.2
Permanent Ineff=
       F       F
Bank Sta=115.91,127.65
XS Rating Curve= 0 ,0
Exp/Cntr=0.5,0.3