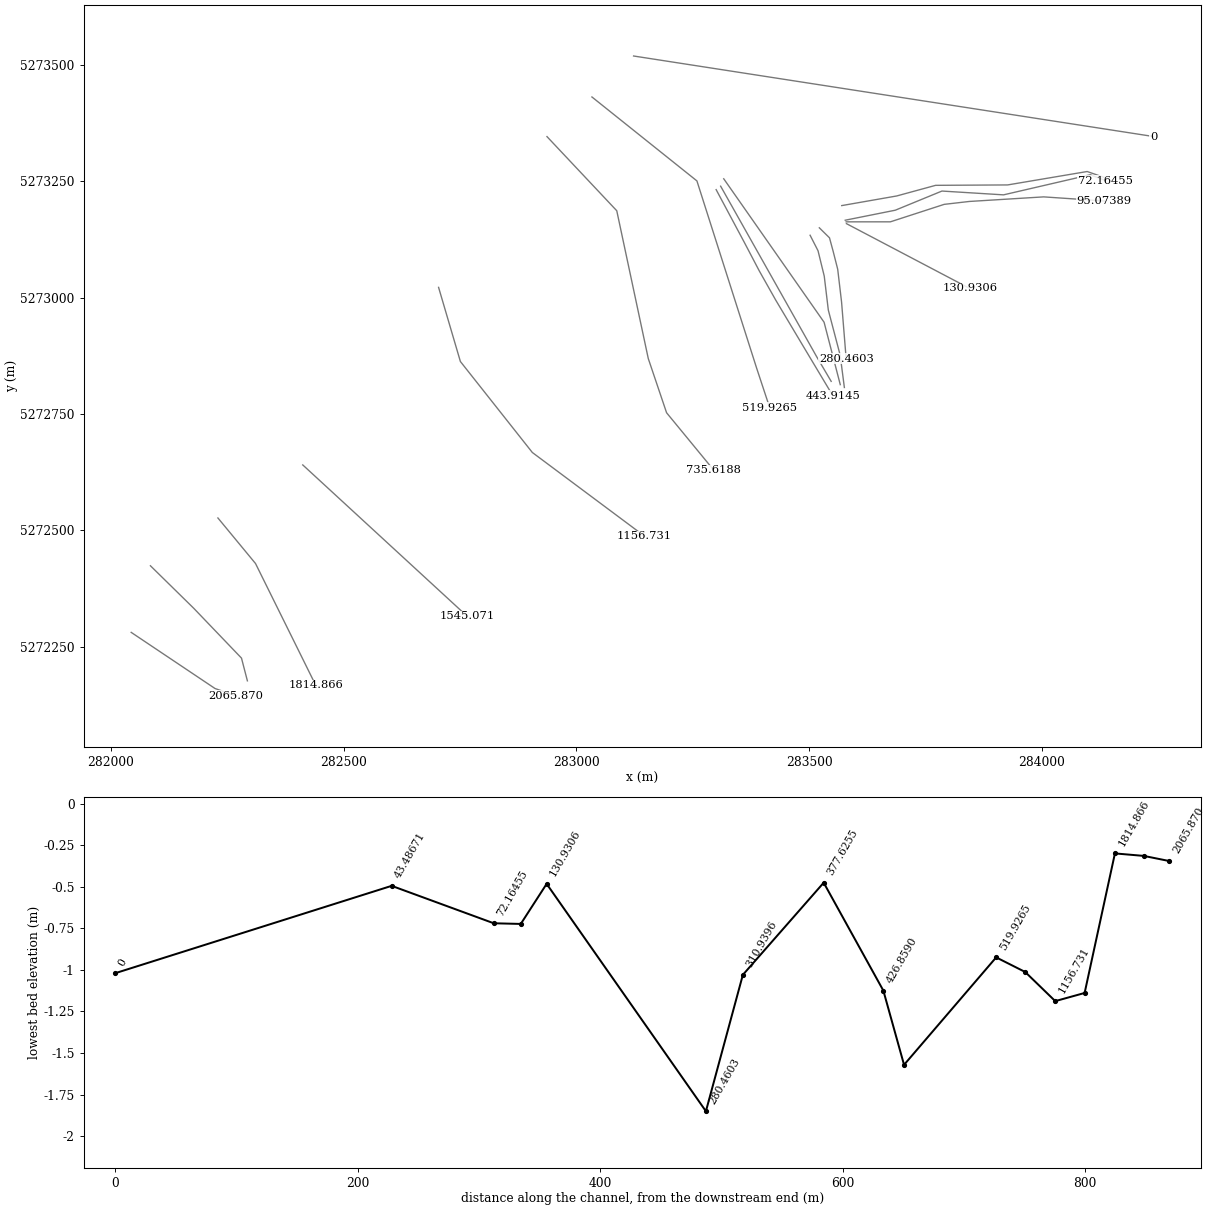
HEC-RAS study ShearstownModel.prj: Shearstown Model

--- ShearstownModel.g02 (geometry) --- (continued)

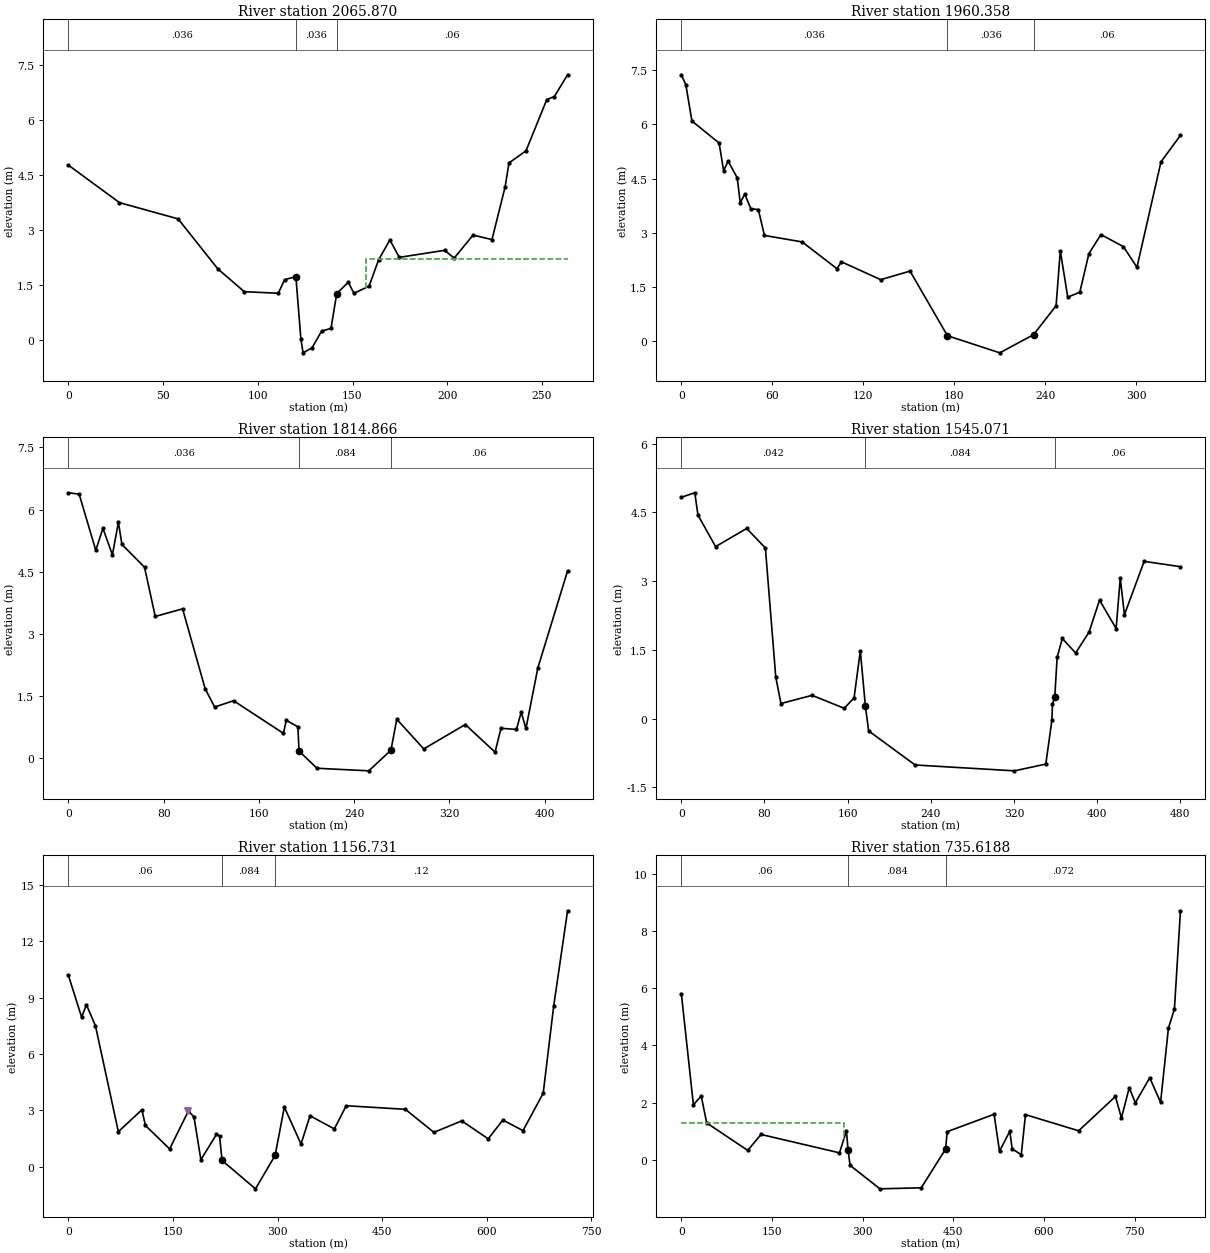
Type RM Length L Ch R = 1 ,2065.870,21.69,21.15,21.1
BEGIN DESCRIPTION:
Section 39
END DESCRIPTION:
Node Name=39
XS GIS Cut Line= 3
 282043.626838615272280.67355237282223.6355953335272160.11722906
282267.8946290965272144.59353811
#Sta/Elev= 30
       0   4.766  26.956   3.746  57.906   3.303  78.872   1.942   92.85    1.32
 110.821   1.277 114.144   1.648   120.11.729356 122.725    .037 123.894   -.346
 128.642   -.208 133.662    .244 138.642    .322  141.641.264055 147.761   1.578
 150.756   1.276 158.743   1.469 163.735   2.183 169.725   2.731 174.717   2.255
 198.678   2.447  203.67   2.234 213.654   2.862 223.635   2.739  230.62   4.185
 232.616   4.827 241.597   5.157 252.574   6.554 256.566   6.635 263.552   7.229
#Mann= 3 , 0 , 0
       0    .036       0   120.1    .036       0  141.64     .06       0
#XS Ineff= 2 , 0
       0                   156.9       0     2.2
Permanent Ineff=
       F       F
Bank Sta=120.1,141.64
XS Rating Curve= 0 ,0
Exp/Cntr=0.3,0.1

Type RM Length L Ch R = 1 ,1960.358,23.13,23.79,24.25
BEGIN DESCRIPTION:
Section 40
END DESCRIPTION:
Node Name=40
XS GIS Cut Line= 4
282084.9499497365272423.78143144282178.0543130115272332.36438142
282280.5859188695272225.37487966282293.2658232345272176.54331467
#Sta/Elev= 30
       0    7.37   2.988   7.095   6.972   6.093  24.901   5.484  27.889    4.72
  30.877   4.984  36.854   4.521  38.846   3.832  41.834   4.071  45.818   3.669
  50.798   3.643  54.782    2.93  79.684    2.75 102.593   2.011 105.581   2.201
 131.477   1.707 150.803   1.944  175.47.1579551 210.004   -.315  232.27.1880784
 247.111    .987 249.891   2.504 254.801   1.223 262.757   1.362 268.725   2.424
 276.681   2.955  291.53   2.619 300.433   2.049 316.261   4.962 329.121   5.696
#Mann= 3 , 0 , 0
       0    .036       0  175.47    .036       0  232.27     .06       0
Bank Sta=175.47,232.27
XS Rating Curve= 0 ,0
Exp/Cntr=0.3,0.1

Type RM Length L Ch R = 1 ,1814.866,27.44,25,23.72
BEGIN DESCRIPTION:
Section 41
END DESCRIPTION:
Node Name=41
XS GIS Cut Line= 4
282229.9290349735272526.47517485282310.6742653875272428.66876699
282313.7404462565272422.53857374282440.3496357175272166.60115474
#Sta/Elev= 30
       0   6.407   8.988   6.375  22.969   5.019  28.961   5.549  36.951   4.909
  41.944   5.696   44.94   5.161  63.914    4.61  72.902   3.424  95.872   3.607
 114.846   1.678 122.836   1.239 138.676   1.391 180.609    .604 182.949    .919
 192.692    .763   193.7.1757512 208.768   -.238 252.294     -.3  270.89.1984574
 275.771    .945 298.419    .229 333.363    .817 358.322     .15 363.314    .727
 376.293    .698 380.287   1.117  384.28    .722 394.264   2.183 419.224   4.521
#Mann= 3 , 0 , 0
       0    .036       0   193.7    .084       0  270.89     .06       0
Bank Sta=193.7,270.89
XS Rating Curve= 0 ,0
Exp/Cntr=0.3,0.1

Type RM Length L Ch R = 1 ,1545.071,24.92,24.23,24.02
BEGIN DESCRIPTION:
Section 42
END DESCRIPTION:
Node Name=42
XS GIS Cut Line= 2
282412.2411279695272640.43028539282765.6052254015272315.17469571
#Sta/Elev= 30
       0   4.832   12.98    4.93  15.976   4.444   32.95   3.755  62.904   4.151
  80.877   3.725  90.862    .909  95.854     .33 125.808    .509 156.761    .226
  166.22    .454 172.221   1.479  177.11.2724791 180.223   -.267 224.932  -1.011
 320.507  -1.139 350.701   -.992 356.566   -.034 357.129    .322  359.31.4665211
 361.603   1.339 366.589    1.75 379.421   1.433 392.401   1.892 402.386   2.587
 418.361   1.967 422.355   3.066 426.349   2.267  445.32   3.433 480.267   3.317
#Mann= 3 , 0 , 0
       0    .042       0  177.11    .084       0  359.31     .06       0
Bank Sta=177.11,359.31
XS Rating Curve= 0 ,0
Exp/Cntr=0.3,0.1

Type RM Length L Ch R = 1 ,1156.731,24.77,24.77,24.77
BEGIN DESCRIPTION:
Section 43
END DESCRIPTION:
Node Name=43
XS GIS Cut Line= 4
282704.0342084265273021.90289057 282750.881721345272862.62134666
282905.4855401995272667.13056745283146.3838473515272487.49095268
#Sta/Elev= 30
       0  10.177  18.889   7.957  25.849   8.618  38.773    7.49  71.581   1.857
 105.383   3.022 110.354   2.186  145.15    .938  172.01   2.957 179.985   2.644
 189.955    .362 212.297   1.711  216.69   1.629  220.32    .323 268.251  -1.188
  296.41.5946554 309.589   3.165 333.515   1.201 346.476   2.701 381.369   2.003
 398.317   3.238 483.153   3.047 524.086    1.82  564.02   2.431 601.957   1.475
 622.922   2.475 651.875   1.913 680.827   3.903 695.802    8.53 715.769  13.621
#Mann= 3 , 0 , 0
       0     .06       0  220.32    .084       0  296.41     .12       0
Levee=-1,172.01,2.96,0,,,,
Bank Sta=220.32,296.41
XS Rating Curve= 0 ,0
Exp/Cntr=0.3,0.1

Type RM Length L Ch R = 1 ,735.6188,23.97,23.97,23.97
BEGIN DESCRIPTION:
Section 44
END DESCRIPTION:
Node Name=44
XS GIS Cut Line= 5
282936.9332726415273345.81997989283086.8453139775273186.53843598
283154.5526840875272868.97747977283193.8805513565272752.50690277
283295.1372609955272629.32863744
#Sta/Elev= 30
       0   5.805  19.976   1.923   32.96   2.229  41.949    1.29 109.866    .329
 131.839    .887 261.693    .245 273.157   1.015  275.82.3542499  279.23   -.192
  328.57  -1.013 396.976   -.976  437.12.3708771 439.923    .984 517.459   1.592
  526.45      .3 543.435    .999 547.433    .381 562.424    .181  569.42   1.579
 657.372   1.015 718.189   2.213 728.155   1.465 741.111   2.521 751.077   1.992
 774.995   2.866 792.933   2.009 805.889   4.598 815.854   5.275  825.82   8.701
#Mann= 3 , 0 , 0
       0     .06       0  275.82    .084       0  437.12    .072       0
#XS Ineff= 2 , 0
       0   268.8     1.3     772       0     1.3
Permanent Ineff=
       F       F
Bank Sta=275.82,437.12
XS Rating Curve= 0 ,0
Exp/Cntr=0.3,0.1

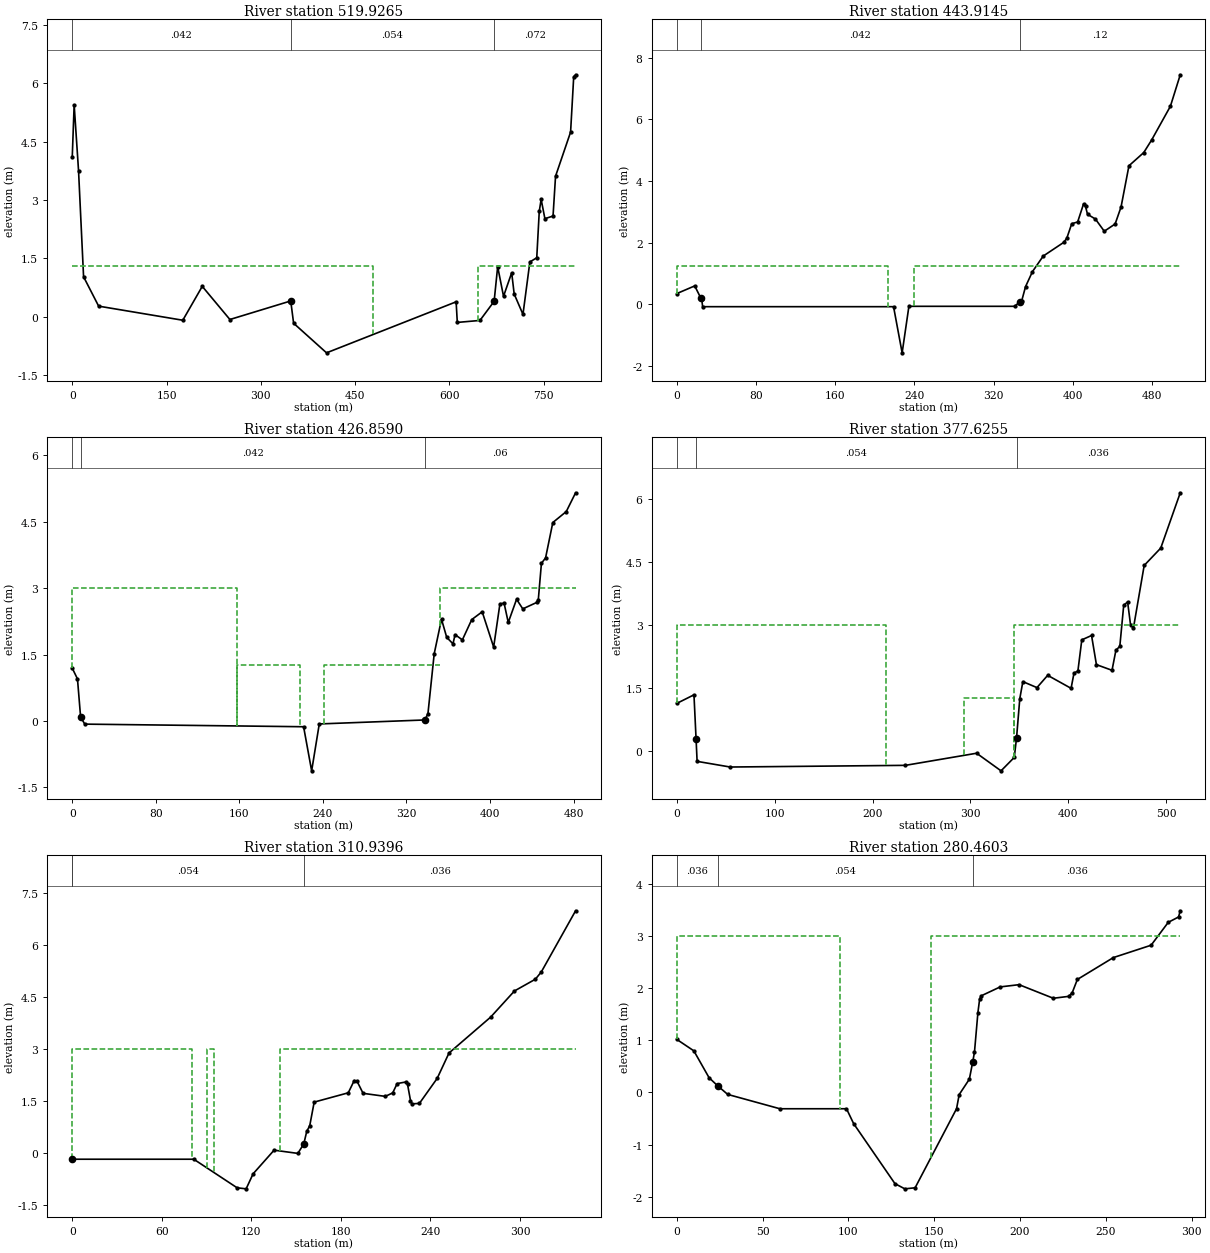
Type RM Length L Ch R = 1 ,519.9265,76.01,76.01,76.01
BEGIN DESCRIPTION:
Section 45
END DESCRIPTION:
Node Name=45
XS GIS Cut Line= 4
283033.4976219335273430.97415832283259.0553987255273250.64086736
283387.411682446   5272848.20008283415.5835134895272763.01970187
#Sta/Elev= 30
       0   4.115   2.998   5.444   9.993    3.75  17.987   1.028  41.969    .274
 175.868   -.088 206.845    .782 250.812   -.069  347.62.4073217 352.211   -.165
 404.603   -.925 610.825    .385 612.676   -.144  648.72   -.093  671.29.3980832
 676.912   1.288 686.233    .527 699.214   1.131 703.209    .585 717.179    .063
 728.145   1.409  739.11   1.516 743.098   2.707 746.089   3.016  752.07    2.52
 765.029   2.588 769.017   3.611 792.942   4.743 797.927   6.167 800.917   6.215
#Mann= 3 , 0 , 0
       0    .042       0  347.62    .054       0  671.29    .072       0
#XS Ineff= 2 , 0
       0     479     1.3   645.8       0     1.3
Permanent Ineff=
       F       F
Bank Sta=347.62,671.29
XS Rating Curve= 0 ,0
Exp/Cntr=0.3,0.1

Type RM Length L Ch R = 1 ,443.9145,17.06,17.06,17.06
BEGIN DESCRIPTION:
Section 46
END DESCRIPTION:
Node Name=46
XS GIS Cut Line= 6
283300.3700358045273231.86327597283361.1229911965273118.16049707
283393.0786741575273057.22175282 283428.564345355272994.23933117
283490.0604561625272891.12651697283550.9992004125272789.31422475
#Sta/Elev= 30
       0    .353  17.988      .6  23.984    .216  24.984    .191  25.983   -.074
 218.957   -.074 227.634  -1.571 234.472   -.062 341.456   -.062 346.417    .083
 348.402    .105 352.371    .577 359.316   1.061 370.231   1.568 391.072   2.014
 394.063   2.147 399.049   2.617 405.031   2.674 411.014   3.262 413.008   3.176
 415.002   2.923 422.979   2.769 431.953   2.373 442.921   2.609 448.904   3.161
 456.881   4.497 471.837   4.925 479.814   5.333 498.759   6.426  508.73   7.448
#Mann= 3 , 0 , 0
       0    .042       0  23.984    .042       0 346.417     .12       0
#XS Ineff= 2 , 0
       0   213.3    1.26   240.1       0    1.26
Permanent Ineff=
       F       F
Bank Sta=23.984,346.417
XS Rating Curve= 0 ,0
Exp/Cntr=0.5,0.3

Type RM Length L Ch R = 1 ,426.8590,49.23,49.23,49.23
BEGIN DESCRIPTION:
Section 47
END DESCRIPTION:
Node Name=47
XS GIS Cut Line= 3
283310.0310562335273239.29483015283516.831999219 5272872.0801609
283547.5180335385272819.96757368
#Sta/Elev= 30
       0   1.193   4.993     .95   7.989    .088  11.984    -.07  221.49   -.129
 229.201  -1.125 236.502   -.066 337.553    .024 340.549    .167 346.542    1.52
 353.532   2.299 358.526   1.889 364.518   1.744 366.515   1.951 373.506   1.833
 382.494   2.291 392.481   2.467 403.467    1.67 409.459   2.645 413.454   2.662
 417.448   2.226 425.409    2.75 431.357   2.533 445.237   2.684 446.229   2.743
 449.203   3.562 453.169   3.684 460.109   4.483 472.997   4.731  481.92   5.155
#Mann= 3 , 0 , 0
       0    .042       0   7.989    .042       0 337.553     .06       0
#XS Ineff= 4 ,-1
       0   158.2       3   158.2   218.5    1.26   240.6   352.2    1.26
   352.2     500       3
Permanent Ineff=
       F       F       F       F
Bank Sta=7.989,337.553
XS Rating Curve= 0 ,0
Exp/Cntr=0.5,0.3

Type RM Length L Ch R = 1 ,377.6255,66.69,66.69,66.69
BEGIN DESCRIPTION:
Section 48
END DESCRIPTION:
Node Name=48
XS GIS Cut Line= 3
283316.6865485525273255.19152789283532.2738355985272947.01733186
283567.0444739495272812.91860813
#Sta/Elev= 30
       0   1.134  17.429   1.337  19.561    .293  20.634    -.25  54.431   -.385
 233.617   -.345 306.411   -.056  331.39   -.476 344.924   -.156 347.286    .318
 350.561   1.245 353.709   1.652 368.118   1.509 379.089   1.802 403.008   1.492
 405.998   1.856 409.985   1.906 413.971   2.648 423.938   2.752 428.921   2.057
 444.867   1.922 448.854   2.401  452.84   2.493 456.827   3.473 460.813   3.553
 463.803   3.007 466.793   2.934 477.756   4.423 494.699   4.837 514.632   6.156
#Mann= 3 , 0 , 0
       0    .036       0  19.561    .054       0 347.286    .036       0
#XS Ineff= 3 ,-1
       0     214       3     294   344.2    1.26   344.2     515       3
Permanent Ineff=
       F       F       F
Bank Sta=19.561,347.286
XS Rating Curve= 0 ,0
Exp/Cntr=0.3,0.1

Type RM Length L Ch R = 1 ,310.9396,30.48,30.48,30.48
BEGIN DESCRIPTION:
Section 49
END DESCRIPTION:
Node Name=49
XS GIS Cut Line= 6
283502.2181972345273133.89678214283519.2490634915273100.62504274
283532.5992213525273046.17045146283541.3822199455272973.09590316
283566.8528555155272876.13751009283575.852241862  5272806.801189
#Sta/Elev= 30
       0   -.176  81.403   -.176  110.44      -1 116.476   -1.03 121.153   -.597
 135.218    .085 151.131   -.008  155.11    .266 157.099    .629 159.088    .789
 162.072   1.471 184.911   1.739 188.881   2.092 190.866   2.066 194.836   1.724
 209.725   1.636 214.687   1.737 217.665   2.006  223.62   2.052 224.613   1.985
 226.598   1.517  227.59   1.421 232.553   1.433 244.464   2.154 252.404   2.887
 280.278   3.921 296.259   4.676 310.243   5.014 314.238   5.224 337.211   6.988
#Mann= 3 , 0 , 0
       0    .036       0       0    .054       0  155.11    .036       0
#XS Ineff= 3 ,-1
       0      80       3      90      95       3   138.9     350       3
Permanent Ineff=
       F       F       F
Bank Sta=0,155.11
XS Rating Curve= 0 ,0
Exp/Cntr=0.5,0.3

Type RM Length L Ch R = 1 ,280.4603,172.11,131.4,203.46
BEGIN DESCRIPTION:
Section 50
END DESCRIPTION:
Node Name=50
XS GIS Cut Line= 6
 283522.062444495273149.85000052283543.8822346655273128.40303837
283551.8497124315273098.99925137283561.5245068615273060.86917921
283569.839135387 5272990.3105804283579.6760938115272868.75387987
#Sta/Elev= 30
       0   1.016   9.869    .798  18.752    .282  23.687    .129  29.608   -.038
      60   -.313  98.846   -.313     103   -.598 127.084   -1.75 132.828   -1.85
 138.837   -1.83     163   -.313 164.537   -.041 170.458    .254 172.444    .588
 173.444    .771 175.443    1.53 176.443   1.788 177.442   1.855 188.438   2.025
 199.434   2.068 219.426   1.807 228.423   1.844 230.422   1.913 233.421   2.168
 254.413   2.588 276.405   2.825 286.401   3.264 292.399   3.367 293.399   3.486
#Mann= 3 , 0 , 0
       0    .036       0  23.687    .054       0 172.444    .036       0
#XS Ineff= 2 , 0
       0      95       3     148       0       3
Permanent Ineff=
       F       F
Bank Sta=23.687,172.444
XS Rating Curve= 0 ,0
Exp/Cntr=0.5,0.3

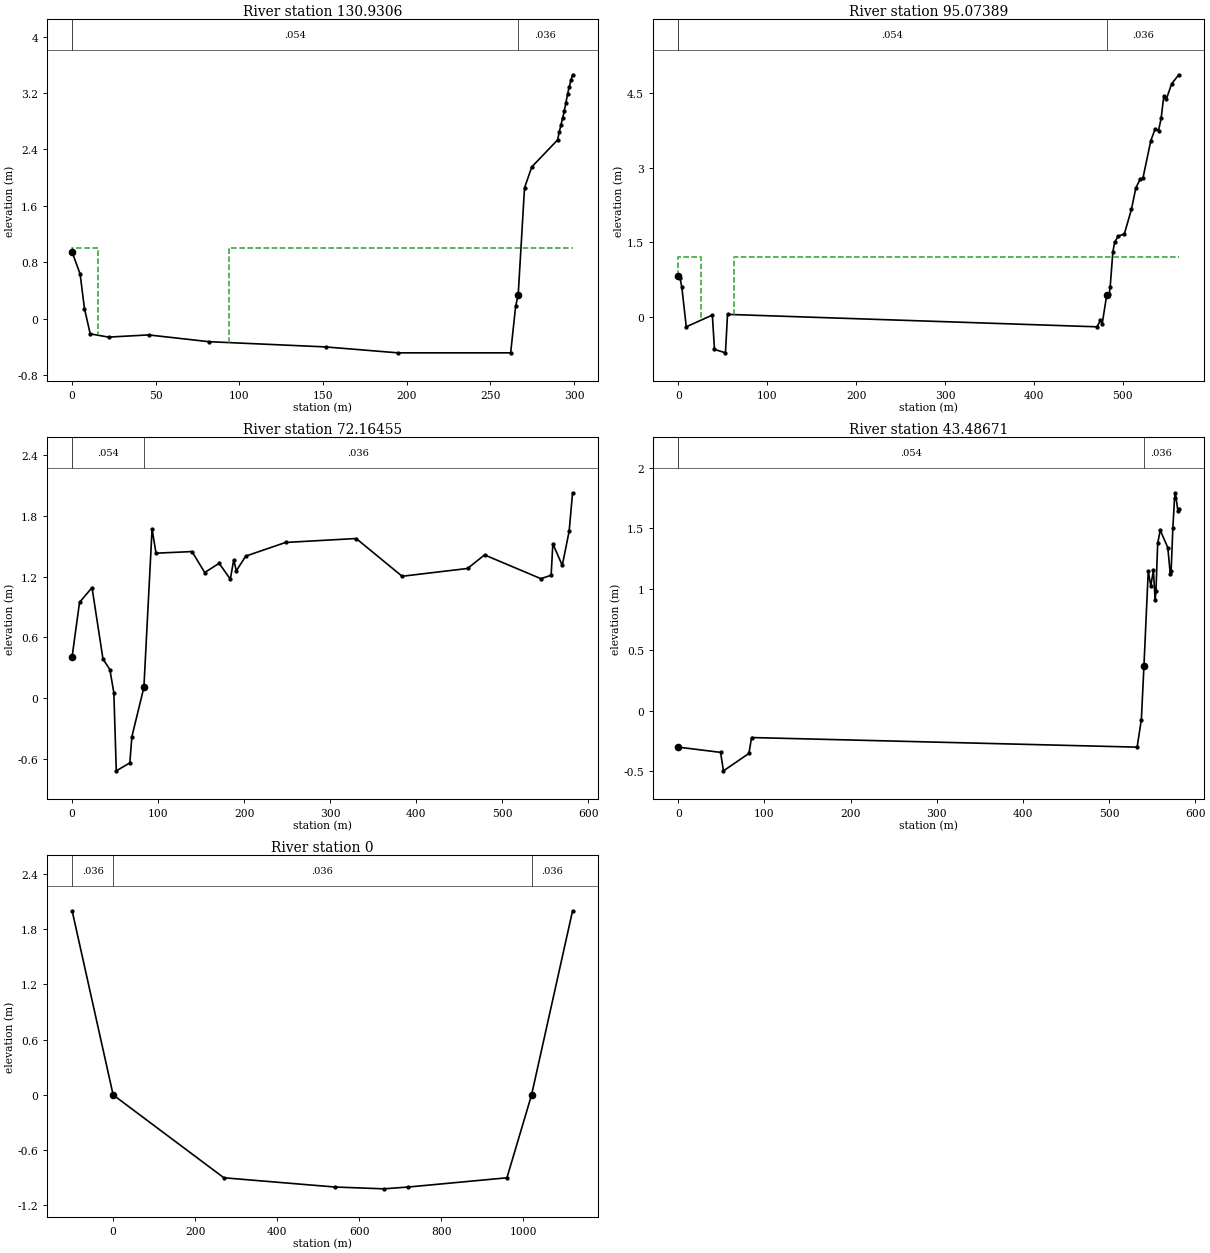
Type RM Length L Ch R = 1 ,130.9306,169.92,21.35,20
BEGIN DESCRIPTION:
Section 51
END DESCRIPTION:
Node Name=51
XS GIS Cut Line= 2
283580.291020371 5273158.8379694 283844.99891245 5273019.6966415
#Sta/Elev= 24
       0    .944   4.781    .634   7.363    .145  10.808   -.214  21.776    -.26
  45.704   -.229  81.778   -.325  151.43   -.399 194.655   -.483 262.048   -.483
 265.031    .179 266.551    .338 270.335   1.855 274.659   2.152 290.077   2.534
 291.074   2.643 292.071   2.746 293.068    2.84 294.065    2.94 295.061   3.061
 296.058   3.186 297.055   3.287 298.052   3.379 299.049   3.458
#Mann= 3 , 0 , 0
       0    .036       0       0    .054       0 266.551    .036       0
#XS Ineff= 2 , 0
       0    15.7       1    93.8       0       1
Permanent Ineff=
       F       F
Bank Sta=0,266.551
XS Rating Curve= 0 ,0
Exp/Cntr=0.3,0.1

Type RM Length L Ch R = 1 ,95.07389,20.65,22.28,17.68
BEGIN DESCRIPTION:
Section 52
END DESCRIPTION:
Node Name=52
XS GIS Cut Line= 6
283579.6496718225273162.69039581 283674.780875735273162.73952167
283790.3245664085273200.24693075 283844.280166795273206.47257695
284004.071752543 5273216.3298501284134.2915188525273207.51018465
#Sta/Elev= 30
       0    .813   1.997    .777   3.993    .597   8.985     -.2  38.316    .036
  40.702   -.655   53.03   -.724  55.376     .05 470.775     -.2 474.754   -.073
 476.743   -.136 481.716    .436   484.7     .47 485.694    .609 488.678   1.308
 490.667   1.498 494.646   1.625 501.608   1.669 509.566   2.165  514.54   2.595
 519.514   2.777 522.499   2.791 531.335   3.545 536.192   3.782 540.077   3.749
 542.991   4.001 545.905   4.438 548.861   4.385 554.813   4.692 562.749   4.873
#Mann= 3 , 0 , 0
       0    .036       0       0    .054       0 481.716    .036       0
#XS Ineff= 2 , 0
       0    25.8     1.2   63.18       0     1.2
Permanent Ineff=
       F       F
Bank Sta=0,481.716
XS Rating Curve= 0 ,0
Exp/Cntr=0.5,0.3

Type RM Length L Ch R = 1 ,72.16455,43.33,84.24,26.07
BEGIN DESCRIPTION:
Section 53
END DESCRIPTION:
Node Name=53
XS GIS Cut Line= 6
283577.704157385 5273166.1923218283685.2826575295273187.68436555
283785.4850992485273228.83788666283917.7800809575273220.66672603
284104.1603640125273263.85714652284136.8450065535273251.40585413
#Sta/Elev= 30
       0    .409   8.609    .945  23.119   1.091  35.872    .385  43.885    .281
  48.489    .052  51.335    -.72  67.063   -.642  69.443   -.383  83.424    .105
  92.922   1.669  97.526   1.431 139.356   1.447 154.117    1.24 170.926   1.331
 183.883   1.174  187.87   1.365  190.86   1.257 201.791   1.402 248.094   1.537
 330.178   1.576 383.581   1.203 459.717    1.28 479.383   1.414 544.924   1.179
 556.814   1.213 558.796   1.524 569.759    1.31 577.741   1.648 581.732   2.028
#Mann= 3 , 0 , 0
       0    .036       0       0    .054       0  83.424    .036       0
Bank Sta=0,83.424
XS Rating Curve= 0 ,0
Exp/Cntr=0.5,0.3

Type RM Length L Ch R = 1 ,43.48671,228,228,228
BEGIN DESCRIPTION:
Section 54
END DESCRIPTION:
Node Name=54
XS GIS Cut Line= 6
283570.219214844 5273197.5961977283688.2993020925273218.28176043
 283771.903451465273241.12206928283926.6142227135273241.98396772
284097.4564455145273270.80425433 284140.928278475273255.77052092
#Sta/Elev= 23
       0     -.3   49.09   -.343  52.453   -.495  82.026   -.352  85.079   -.221
 532.729     -.3 537.649   -.073 540.644    .369 545.635   1.147 548.629   1.027
 551.624   1.155  553.62    .909 554.618    .988 556.594   1.377 559.525   1.485
 568.321   1.342 571.253   1.123  572.23   1.152 574.185     1.5 576.139   1.746
 577.117   1.793 580.049   1.644 581.026   1.663
#Mann= 3 , 0 , 0
       0    .036       0       0    .054       0 540.644    .036       0
Bank Sta=0,540.644
XS Rating Curve= 0 ,0
Exp/Cntr=0.5,0.3

Type RM Length L Ch R = 1 ,0       ,,,
BEGIN DESCRIPTION:
Downstream BC
END DESCRIPTION:
XS GIS Cut Line= 2
         283123.        5273519.         284240.        5273346.
#Sta/Elev= 9
    -100       2       0       0     270     -.9     540      -1     660   -1.02
     720      -1     960     -.9    1020       0    1120       2
#Mann= 3 , 0 , 0
    -100    .036       0       0    .036       0    1020    .036       0
Bank Sta=0,1020
XS Rating Curve= 0 ,0
Exp/Cntr=0.3,0.1
Stream Node=Shearstown_Brook,Main            , 0 , 0 ,Upstream end
Stream Node=Shearstown_Brook,Main            , 0 , 1 ,Downstream end

--- ShearstownModel.g03 (geometry) ---

Geom Title=Shearstown Sens n-20%
Program Version=4.10

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
River Reach=Shearstown_Brook,Main

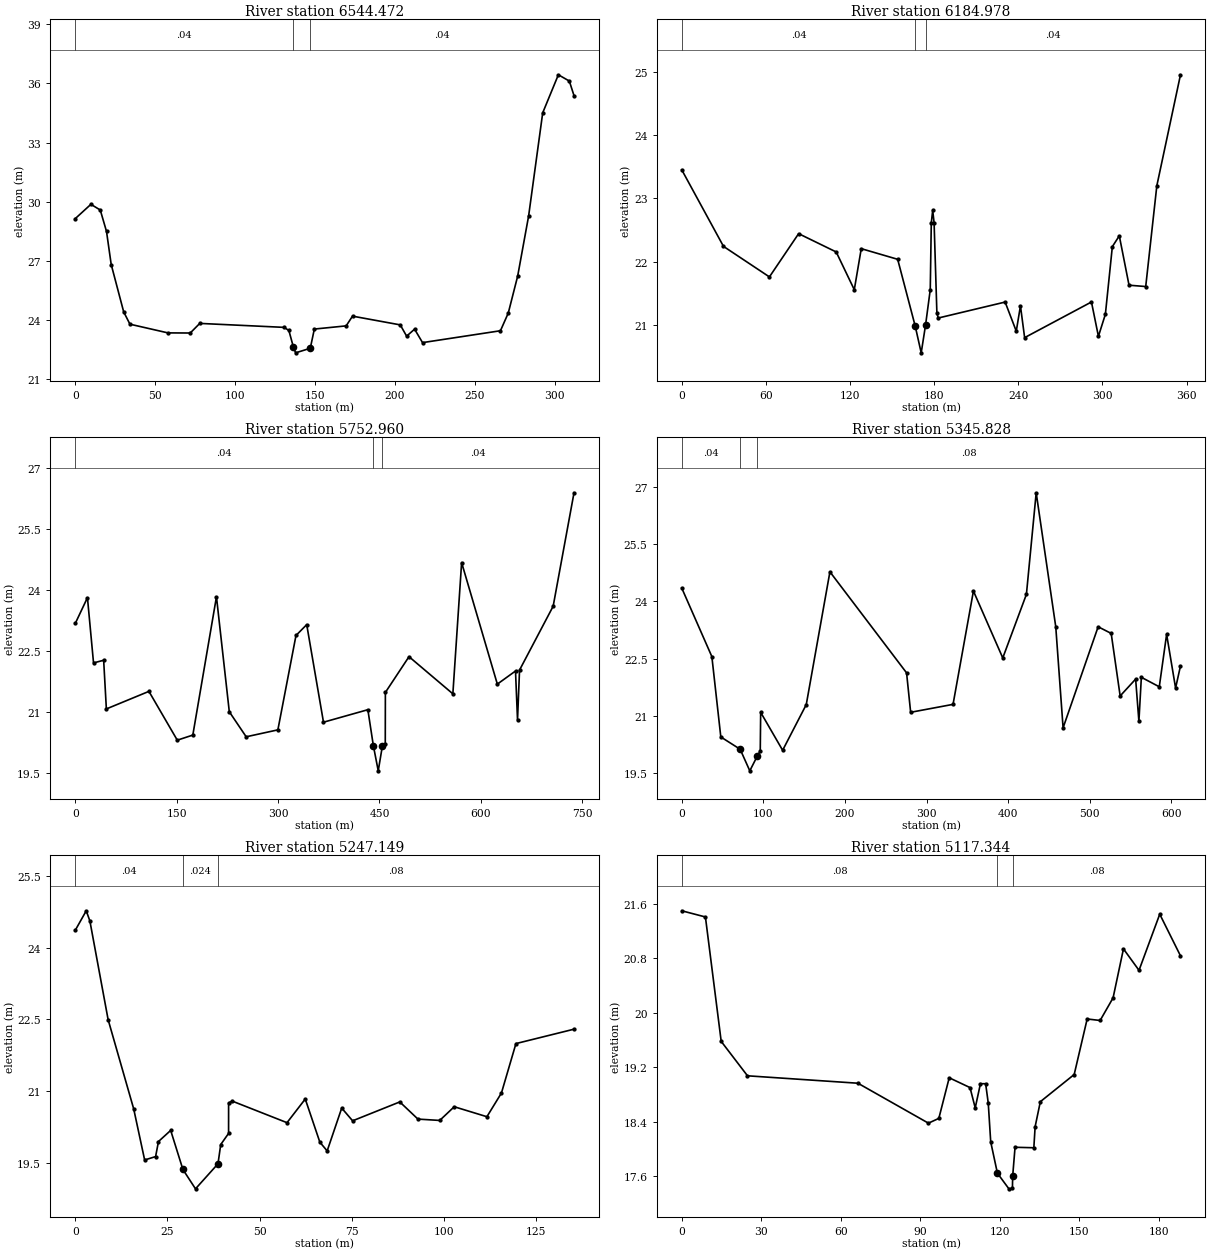
Type RM Length L Ch R = 1 ,6544.472,23.97,23.97,23.97
BEGIN DESCRIPTION:
Section 2
END DESCRIPTION:
Node Name=2
XS GIS Cut Line= 4
279642.8886158175269616.29250684279676.2254208965269594.05736596
279865.5728973935269474.22258917279906.754524344 5269449.5598458
#Sta/Elev= 30
       0  29.145   9.774  29.868  15.638  29.579  19.547  28.491  22.479  26.816
  30.298  24.414  34.208  23.792  57.998  23.351  71.941  23.345  77.917  23.832
   130.7  23.631 133.688  23.474   136.5  22.635  137.91   22.34  147.09  22.572
 149.623  23.545 169.542  23.707 173.525    24.2 203.403  23.757 207.387  23.186
 212.366   23.54 217.346  22.858 266.114   23.46 271.012  24.358  276.89   26.23
 283.747  29.278 292.564  34.506 302.361  36.434 309.218  36.116 312.157  35.377
#Mann= 3 , 0 , 0
       0     .04       0   136.5    .028       0  147.09     .04       0
Bank Sta=136.5,147.09
XS Rating Curve= 0 ,0
Exp/Cntr=0.3,0.1

Type RM Length L Ch R = 1 ,6184.978,24,24,24
BEGIN DESCRIPTION:
Section 3
END DESCRIPTION:
Node Name=3
XS GIS Cut Line= 5
 279820.72889364 5269887.8296174279934.1476008725269832.90339471
 279984.689044135269804.58392651280069.3762310125269709.81074358
280098.4158214875269675.93122135
#Sta/Elev= 30
       0  23.448  29.768  22.239  62.513  21.757  83.351   22.44 110.142  22.151
 123.042  21.555 128.016  22.203 153.987  22.035  166.4720.98214 170.769  20.558
  173.8720.99633 177.219  21.555  177.96  22.608 178.959  22.807 179.958  22.614
 181.955  21.184 182.954  21.108 230.622   21.36 238.565    20.9 241.544    21.3
 244.523  20.798 292.185  21.361 297.149  20.819 302.114  21.167 307.079  22.235
 312.042  22.406 318.984  21.626 330.883  21.605 338.816  23.198 355.673  24.949
#Mann= 3 , 0 , 0
       0     .04       0  166.47    .024       0  173.87     .04       0
Bank Sta=166.47,173.87
XS Rating Curve= 0 ,0
Exp/Cntr=0.3,0.1

Type RM Length L Ch R = 1 ,5752.960,23.95,23.95,23.95
BEGIN DESCRIPTION:
Section 4
END DESCRIPTION:
Node Name=4
XS GIS Cut Line= 6
279864.7088621385269962.89535559280148.460317394 5269914.7111462
280225.7080181515269946.06912374280258.8978504125270033.83840265
280291.7523945065270077.91709703280468.1728860055269961.66313154
#Sta/Elev= 30
       0  23.177  17.988  23.809  26.983  22.207  41.973  22.272   45.97  21.077
 108.929  21.508 150.902   20.31 173.888  20.435 208.865   23.83 227.853  21.008
 252.837  20.393 299.724  20.563 326.522   22.88 342.402  23.147 367.214  20.751
  432.86  21.058  440.9720.17692 448.221  19.557  454.24  20.157 458.619  20.216
 458.778  21.482 493.732   22.36  558.62  21.448 571.581   24.67 624.423  21.686
 651.306  22.008 654.291  20.805 657.276  22.031 707.025  23.599  737.87  26.384
#Mann= 3 , 0 , 0
       0     .04       0  440.97    .028       0  454.24     .04       0
Bank Sta=440.97,454.24
XS Rating Curve= 0 ,0
Exp/Cntr=0.3,0.1

Type RM Length L Ch R = 1 ,5345.828,24.67,24.67,24.67
BEGIN DESCRIPTION:
Section 5
END DESCRIPTION:
Node Name=5
XS GIS Cut Line= 5
279949.9376922285270261.38038633279992.9928032745270252.93819582
280078.9236277615270235.18545406 280243.823128035270203.54021435
 280514.572495045270049.04481284
#Sta/Elev= 30
       0  24.345  36.895  22.551  47.863  20.448   71.5720.12595  83.392  19.561
    92.719.95229  96.207  20.083  96.722  21.092 123.644  20.099 152.609  21.295
 181.593   24.77 275.541  22.126 280.539  21.093 332.499  21.301 357.477  24.267
 393.445  22.516 422.419   24.18 434.409  26.839 458.387  23.333  467.38  20.687
 510.341  23.332 526.328  23.158 537.318  21.521 556.302  21.962 560.299  20.856
 563.296  22.009 585.277  21.761  594.27  23.134  605.26  21.728 611.255  22.307
#Mann= 3 , 0 , 0
       0     .04       0   71.57    .028       0    92.7     .08       0
Bank Sta=71.57,92.7
XS Rating Curve= 0 ,0
Exp/Cntr=0.3,0.1

Type RM Length L Ch R = 1 ,5247.149,21.63,21.63,21.63
BEGIN DESCRIPTION:
Section 6
END DESCRIPTION:
Node Name=6
XS GIS Cut Line= 3
280032.4970469815270351.86658041280096.3958268435270322.49029571
280154.3381677475270293.02517464
#Sta/Elev= 30
       0  24.371   2.972  24.779   3.962  24.565   8.915  22.495  15.849  20.626
   18.82  19.555  21.792  19.626  22.573  19.942  25.887  20.175    29.2  19.356
  32.621   18.95   38.7219.47467  39.468  19.879  41.597  20.112  41.602  20.749
  42.593  20.789  57.451  20.337  62.404  20.833  66.366  19.928  68.347  19.745
  72.298  20.643  75.253  20.376  88.056  20.772  92.981  20.412   98.89  20.384
  102.83  20.671 111.694  20.462 115.634  20.958 119.573  21.995 135.332  22.297
#Mann= 3 , 0 , 0
       0     .04       0    29.2    .024       0   38.72     .08       0
Bank Sta=29.2,38.72
XS Rating Curve= 0 ,0
Exp/Cntr=0.3,0.1

Type RM Length L Ch R = 1 ,5117.344,22.05,22.05,22.05
BEGIN DESCRIPTION:
Section 7
END DESCRIPTION:
Node Name=7
XS GIS Cut Line= 5
280072.2465517615270501.69594384280128.3868047095270449.91716011
280150.1082838745270423.33692903280165.4760816075270388.23960006
280179.8961941525270351.88511824
#Sta/Elev= 30
       0  21.499   8.927  21.408  14.878  19.582  24.796  19.077  66.454  18.968
  93.046  18.382  96.969  18.452 100.892  19.048 108.738  18.904 110.699  18.606
 112.664  18.961 114.629  18.961 115.612  18.678 116.543  18.107  119.0717.64742
 123.405  17.418 124.732  17.423  124.8217.60086  125.72  18.028 132.809  18.021
 133.295   18.33  135.26  18.697 148.031  19.096 152.925  19.911 157.814  19.889
 162.702  20.221 166.613   20.94  172.48  20.625 180.302  21.449 188.124  20.838
#Mann= 3 , 0 , 0
       0     .08       0  119.07    .024       0  124.82     .08       0
Bank Sta=119.07,124.82
XS Rating Curve= 0 ,0
Exp/Cntr=0.3,0.1

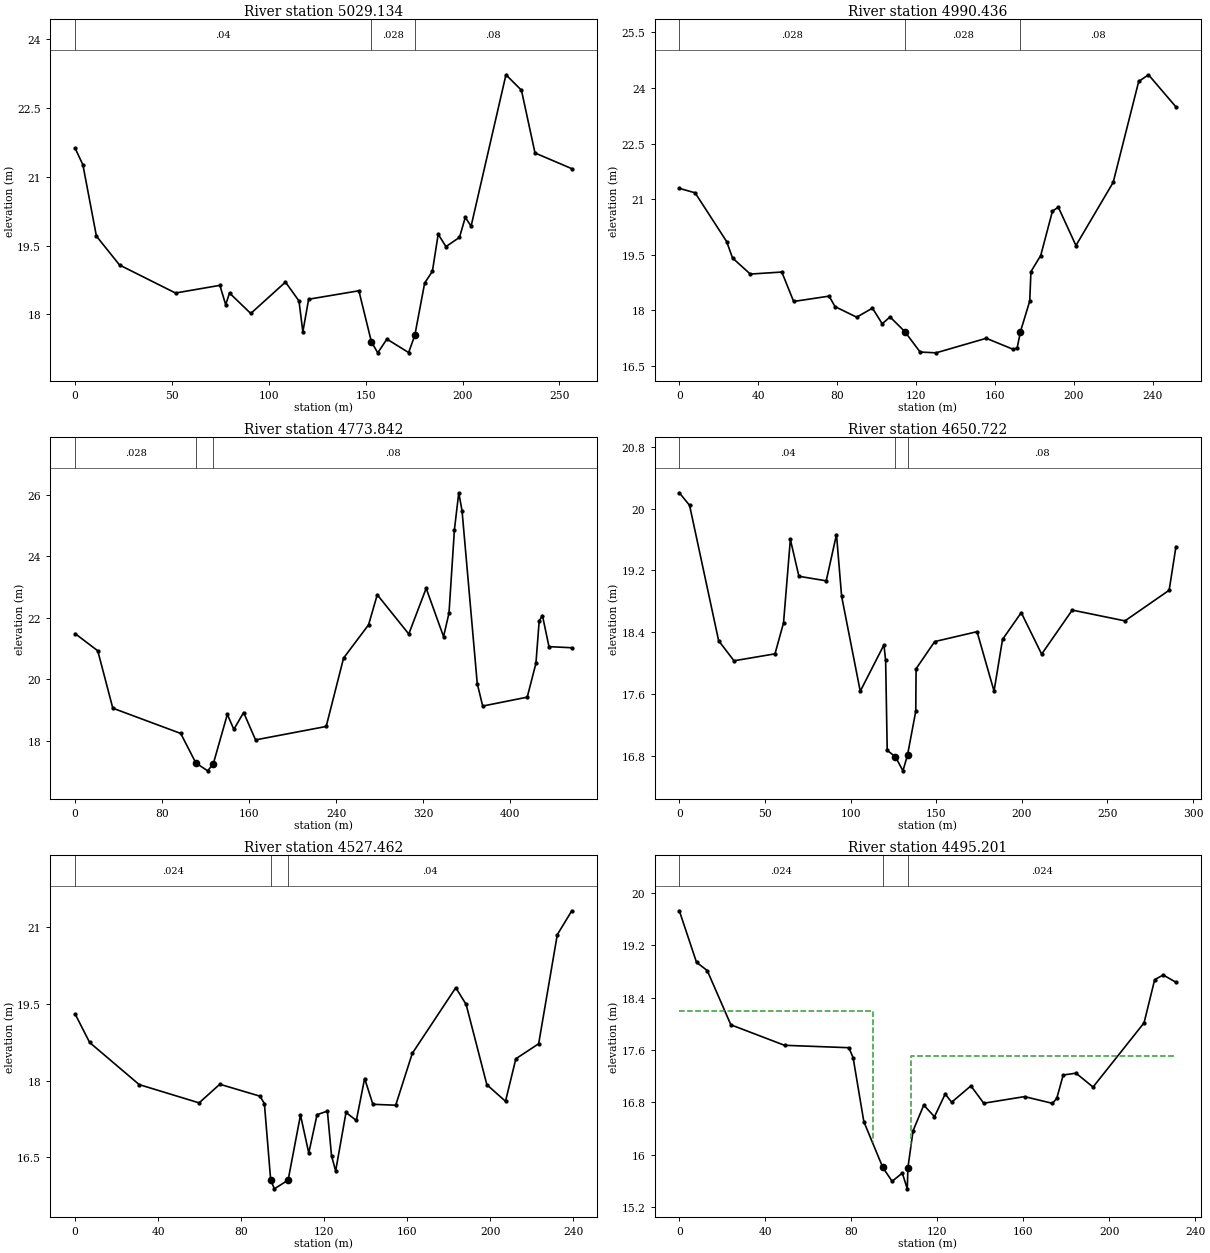
Type RM Length L Ch R = 1 ,5029.134,19.35,19.35,19.35
BEGIN DESCRIPTION:
Section 8
END DESCRIPTION:
Node Name=8
XS GIS Cut Line= 4
280103.1743131415270545.55409078280212.9905607145270469.68944225
280263.4532035485270422.73641931280296.3413668275270379.92087102
#Sta/Elev= 30
       0  21.614   3.984  21.255  10.957  19.705   22.91  19.076  51.795  18.467
  74.705  18.634  77.693  18.214  79.685  18.467  90.642  18.022 108.571  18.705
 115.544  18.294 117.536  17.622 120.524  18.332  146.46  18.516  152.9317.40534
 156.211  17.166 160.931  17.465 172.148  17.172  175.3417.54627 180.424  18.684
  184.42   18.94 187.417  19.746 191.413  19.476 198.406  19.678 201.403  20.112
 204.401  19.921 222.398  23.214 230.396  22.878 237.395  21.513 256.391  21.172
#Mann= 3 , 0 , 0
       0     .04       0  152.93    .028       0  175.34     .08       0
Bank Sta=152.93,175.34
XS Rating Curve= 0 ,0
Exp/Cntr=0.3,0.1

Type RM Length L Ch R = 1 ,4990.436,24.07,24.07,24.07
BEGIN DESCRIPTION:
Section 9
END DESCRIPTION:
Node Name=9
XS GIS Cut Line= 4
 280134.58009247  5270568.355547280212.2964044955270512.21838797
280299.5517162145270448.43891012280332.9097400215270414.33816344
#Sta/Elev= 30
       0  21.289   7.989  21.168  23.968  19.852  26.964  19.407  35.952  18.973
   51.93  19.028  57.922  18.233  75.898  18.377  78.894  18.094  89.879  17.808
  97.854  18.053 102.812   17.63 106.778  17.815  114.2217.42065 122.017  16.867
 130.084  16.845 155.522  17.238 169.129  16.941 171.187  16.976  172.8717.42072
 177.561  18.243  178.17   19.04 183.128  19.474 189.078  20.674 192.052   20.78
 200.976  19.744 219.852  21.451 232.772  24.176 237.741  24.357 251.654  23.489
#Mann= 3 , 0 , 0
       0    .028       0  114.22    .028       0  172.87     .08       0
Bank Sta=114.22,172.87
XS Rating Curve= 0 ,0
Exp/Cntr=0.3,0.1

Type RM Length L Ch R = 1 ,4773.842,24.62,24.62,24.62
BEGIN DESCRIPTION:
Section 10
END DESCRIPTION:
Node Name=10
XS GIS Cut Line= 4
280316.8324029625270732.46707628280370.6936636935270671.92322421
280426.127656044  5270600.035326 280593.190513925270369.42837701
#Sta/Elev= 30
       0  21.481  20.753  20.923  34.588  19.054  96.996  18.232  110.9717.26892
 121.828  17.014  126.9917.24531 139.891  18.852 145.876  18.365 154.855  18.913
 165.828  18.022 230.764  18.459  246.75  20.686 269.731  21.769 277.725  22.748
 306.701  21.469 322.688  22.958 338.674  21.384  343.67  22.151 348.666  24.871
 352.663  26.068  355.66  25.485 369.649  19.856 374.645  19.123 415.611  19.413
 423.604  20.518 426.602  21.897 429.599  22.069 435.595  21.058 456.577  21.022
#Mann= 3 , 0 , 0
       0    .028       0  110.97    .028       0  126.99     .08       0
Bank Sta=110.97,126.99
XS Rating Curve= 0 ,0
Exp/Cntr=0.3,0.1

Type RM Length L Ch R = 1 ,4650.722,24.65,24.65,24.65
BEGIN DESCRIPTION:
Section 11
END DESCRIPTION:
Node Name=11
XS GIS Cut Line= 4
280408.6755851325270777.49636719280481.7863438195270714.11417964
280536.1377770565270665.19788972280623.7836627355270583.03866504
#Sta/Elev= 30
       0  20.205   5.985  20.042  22.943  18.289  31.921  18.028  55.861  18.118
  60.849  18.519  64.839  19.601  69.827  19.123  85.787  19.064  91.772  19.664
  94.765  18.865 105.653  17.633 119.487  18.234 120.475  18.032   121.4  16.867
  126.1916.78418 130.588  16.602  133.2516.80567 138.071  17.375 138.262  17.925
 149.132  18.277 173.854  18.405 183.782  17.635 188.746  18.305 199.667  18.652
 211.581  18.114 229.452  18.685  260.23  18.545 286.044  18.942 290.015  19.506
#Mann= 3 , 0 , 0
       0     .04       0  126.19    .028       0  133.25     .08       0
Bank Sta=126.19,133.25
XS Rating Curve= 0 ,0
Exp/Cntr=0.3,0.1

Type RM Length L Ch R = 1 ,4527.462,16.13,16.13,16.13
BEGIN DESCRIPTION:
Section 12
END DESCRIPTION:
Node Name=12
XS GIS Cut Line= 4
280469.4936318965270843.45930345280521.2268582815270815.69005693
280595.2157189425270774.37960973280672.1732427935270717.26256459
#Sta/Elev= 30
       0  19.299   6.966  18.744   30.85  17.921  59.712  17.564  69.681  17.928
  89.036  17.695  91.167   17.55    94.2 16.0559  95.987  15.884   102.6  16.055
 108.562  17.326  112.55  16.584 116.538  17.333 121.522  17.403 123.516  16.531
  125.51  16.234 130.495  17.376  135.48   17.22 139.467   18.04 143.455  17.536
 154.437  17.518 162.423  18.531 183.387  19.815 188.379  19.487 198.362  17.919
 207.347  17.595 212.338  18.426  223.32  18.719 232.304  20.851 239.293  21.318
#Mann= 3 , 0 , 0
       0    .024       0    94.2    .024       0   102.6     .04       0
Bank Sta=94.2,102.6
XS Rating Curve= 0 ,0
Exp/Cntr=0.3,0.1

Type RM Length L Ch R = 1 ,4495.201,18.84,18.84,18.84
BEGIN DESCRIPTION:
Section 13
END DESCRIPTION:
Node Name=13
XS GIS Cut Line= 6
280485.8752244425270858.99914381280549.1776164115270829.36424114
 280591.957136425270816.00868368280628.5758623975270811.57395387
280658.3066750095270807.68587123 280701.222311025270783.11379422
#Sta/Elev= 30
       0  19.725   7.988  18.938  12.981  18.812  23.964  17.983  48.927   17.67
  78.859  17.633  80.851   17.48   85.83  16.504   94.6615.80346  98.996  15.592
 103.731  15.718 106.042  15.477  106.3515.80235 108.736  16.365 113.716  16.756
 118.699  16.579 123.684  16.926 126.675    16.8 135.647   17.05 141.629  16.785
 160.593  16.886 173.586  16.783 175.585  16.859 178.584  17.216 184.549  17.244
 192.462  17.032 216.199  18.013 221.144  18.673   225.1  18.744 231.034  18.633
#Mann= 3 , 0 , 0
       0    .024       0   94.66    .024       0  106.35    .024       0
#XS Ineff= 2 , 0
       0    89.9    18.2   107.7       0    17.5
Permanent Ineff=
       F       F
Bank Sta=94.66,106.35
XS Rating Curve= 0 ,0
Exp/Cntr=0.5,0.3