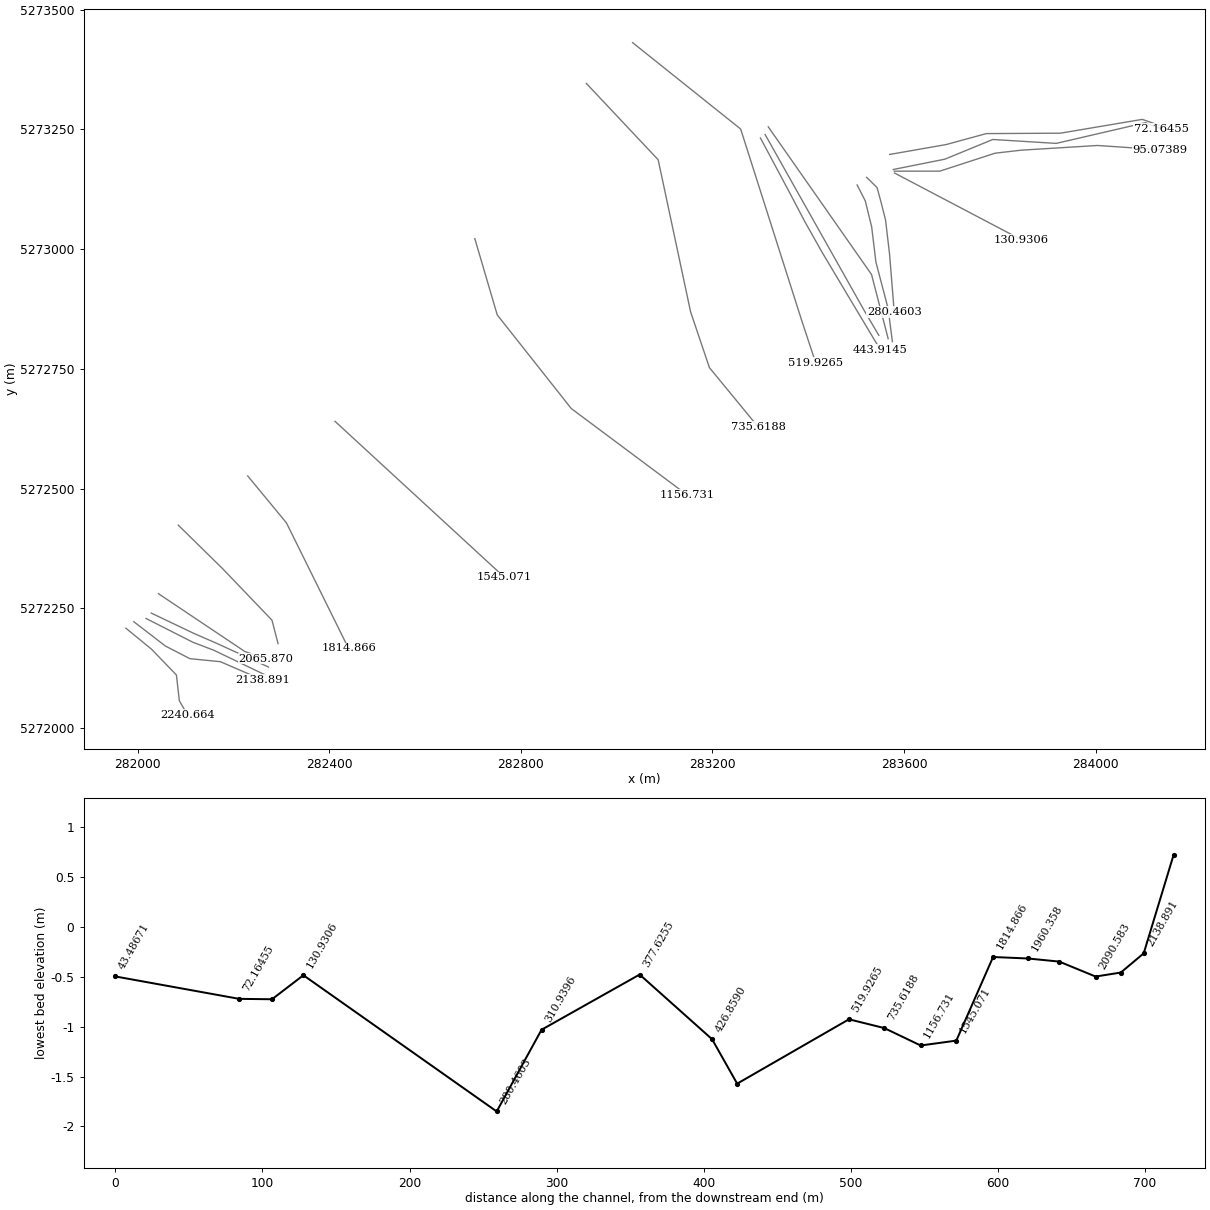
HEC-RAS study ShearstownModel.prj: Shearstown Model

--- ShearstownModel.g16 (geometry) --- (continued)

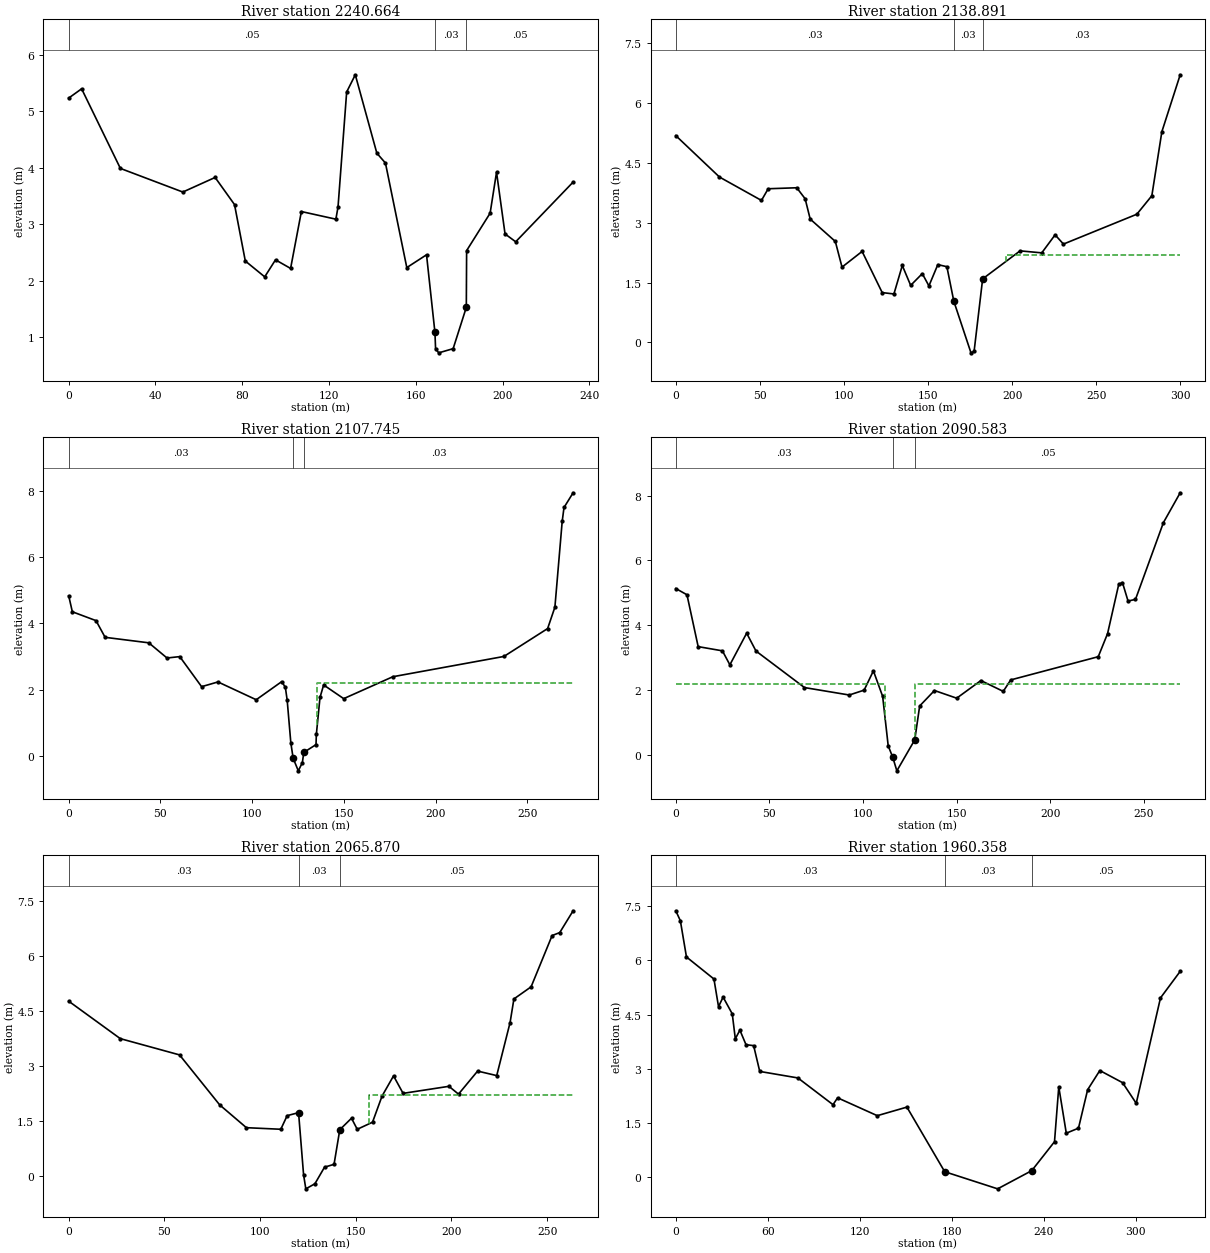
Type RM Length L Ch R = 1 ,2240.664,20.354,20.354,20.354
BEGIN DESCRIPTION:
Section 35
END DESCRIPTION:
Node Name=35
XS GIS Cut Line= 5
281975.5868314815272208.67004968282029.3014879045272164.60013532
282081.0963429695272110.97575028 282087.181513565272057.15711371
282104.4009310975272027.47341689
#Sta/Elev= 30
       0   5.233   5.955   5.397  23.822   3.989  52.606   3.571  67.494   3.829
  76.438   3.349  81.408   2.351  90.355   2.071  95.325   2.372 102.283    2.22
 107.253   3.226 123.158   3.091 124.152   3.309 128.129   5.341 132.105   5.645
 142.045   4.258 146.003   4.084  155.85   2.235 164.941   2.461  168.821.088044
 169.116    .797 170.577    .727 177.211    .801  183.281.531658 183.424   2.535
 194.256   3.197  197.21   3.922 201.136    2.83 206.039   2.691 232.511   3.747
#Mann= 3 , 0 , 0
       0     .05       0  168.82     .03       0  183.28     .05       0
Bank Sta=168.82,183.28
XS Rating Curve= 0 ,0
Exp/Cntr=0.3,0.1

Type RM Length L Ch R = 1 ,2138.891,15.575,15.575,15.575
BEGIN DESCRIPTION:
Section 36
END DESCRIPTION:
Node Name=36
XS GIS Cut Line= 5
281992.1013963195272222.21199284282057.8079421335272171.61362078
 282109.104620875272145.06449802282172.8661179475272138.71636405
282260.2979292715272100.99508694
#Sta/Elev= 30
       0   5.186  25.978   4.147  50.958    3.56  54.954   3.853   71.94   3.878
  76.936   3.602  79.933   3.093  94.881   2.532  98.865   1.887 110.815   2.281
 122.765   1.248 129.736   1.214 134.716   1.928 139.695   1.429 146.606   1.724
 150.549   1.416 155.844    1.95 161.227   1.898  165.361.031523 175.559   -.263
 177.417   -.227   182.51.592167 204.767   2.295 217.662   2.245 225.597   2.697
 230.557   2.465   274.2   3.214 283.127   3.678 289.078   5.283 299.989   6.712
#Mann= 3 , 0 , 0
       0     .03       0  165.36     .03       0   182.5     .03       0
#XS Ineff= 2 , 0
       0                   196.3       0     2.2
Permanent Ineff=
       F       T
Bank Sta=165.36,182.5
XS Rating Curve= 0 ,0
Exp/Cntr=0.3,0.1

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
Type RM Length L Ch R = 1 ,2107.745,17.16,17.16,17.16
BEGIN DESCRIPTION:
Section 37
END DESCRIPTION:
Node Name=37
XS GIS Cut Line= 4
282017.5834106175272228.98007362282114.9336695655272179.56965854
282159.4577391465272162.45997242282265.9624657695272111.39637198
#Sta/Elev= 30
       0   4.837   1.985   4.354  14.887   4.086  19.849   3.581  43.669   3.415
  53.593   2.956  60.541   2.998   72.45   2.089  81.383   2.232 102.224   1.694
 116.128   2.242 118.115   2.069 119.109   1.679 121.096    .389  122.37   -.077
 125.173   -.456 127.385   -.206  128.16    .101 134.826    .337 135.008    .645
 136.996   1.763 138.983   2.141 149.914   1.727 176.721    2.39 237.267   3.003
 261.088   3.846 265.058   4.494 269.029   7.086 270.021   7.507 274.984   7.952
#Mann= 3 , 0 , 0
       0     .03       0  122.37     .03       0  128.16     .03       0
#XS Ineff= 2 , 0
       0   115.1     2.2   135.5       0     2.2
Permanent Ineff=
       T       T
Bank Sta=122.37,128.16
XS Rating Curve= 0 ,0
Exp/Cntr=0.5,0.3

Type RM Length L Ch R = 1 ,2090.583,24.71,24.71,24.71
BEGIN DESCRIPTION:
Section 38
END DESCRIPTION:
Node Name=38
XS GIS Cut Line= 4
282028.5039556975272240.22521369282117.5327028165272197.75754502
282163.7804068235272177.67630512 282273.24980658 5272127.5958815
#Sta/Elev= 30
       0   5.133   5.978    4.94  11.956   3.339  24.909   3.209  28.894   2.777
  37.861   3.754  42.843   3.203  68.748   2.075  92.661   1.845 100.616   1.996
 105.559   2.591 110.502   1.803 113.468    .276  115.91   -.079 118.093   -.496
  127.65.4602455 130.275   1.507 138.184   1.984 150.053   1.747 162.987   2.292
 174.925   1.957 178.905   2.311 225.665   3.028 230.639    3.74 236.609   5.261
 238.598   5.318 241.583   4.746 245.563   4.798 260.486   7.169  269.44   8.089
#Mann= 3 , 0 , 0
       0     .03       0  115.91     .03       0  127.65     .05       0
#XS Ineff= 2 , 0
       0   111.9     2.2   127.8       0     2.2
Permanent Ineff=
       F       F
Bank Sta=115.91,127.65
XS Rating Curve= 0 ,0
Exp/Cntr=0.5,0.3

Type RM Length L Ch R = 1 ,2065.870,21.694,21.154,21.102
BEGIN DESCRIPTION:
Section 39
END DESCRIPTION:
Node Name=39
XS GIS Cut Line= 3
 282043.626838615272280.67355237282223.6355953335272160.11722906
282267.8946290965272144.59353811
#Sta/Elev= 30
       0   4.766  26.956   3.746  57.906   3.303  78.872   1.942   92.85    1.32
 110.821   1.277 114.144   1.648   120.11.729356 122.725    .037 123.894   -.346
 128.642   -.208 133.662    .244 138.642    .322  141.641.264055 147.761   1.578
 150.756   1.276 158.743   1.469 163.735   2.183 169.725   2.731 174.717   2.255
 198.678   2.447  203.67   2.234 213.654   2.862 223.635   2.739  230.62   4.185
 232.616   4.827 241.597   5.157 252.574   6.554 256.566   6.635 263.552   7.229
#Mann= 3 , 0 , 0
       0     .03       0   120.1     .03       0  141.64     .05       0
#XS Ineff= 2 , 0
       0                   156.9       0     2.2
Permanent Ineff=
       F       F
Bank Sta=120.1,141.64
XS Rating Curve= 0 ,0
Exp/Cntr=0.3,0.1

Type RM Length L Ch R = 1 ,1960.358,23.132,23.792,24.248
BEGIN DESCRIPTION:
Section 40
END DESCRIPTION:
Node Name=40
XS GIS Cut Line= 4
282084.9499497365272423.78143144282178.0543130115272332.36438142
282280.5859188695272225.37487966282293.2658232345272176.54331467
#Sta/Elev= 30
       0    7.37   2.988   7.095   6.972   6.093  24.901   5.484  27.889    4.72
  30.877   4.984  36.854   4.521  38.846   3.832  41.834   4.071  45.818   3.669
  50.798   3.643  54.782    2.93  79.684    2.75 102.593   2.011 105.581   2.201
 131.477   1.707 150.803   1.944  175.47.1579551 210.004   -.315  232.27.1880784
 247.111    .987 249.891   2.504 254.801   1.223 262.757   1.362 268.725   2.424
 276.681   2.955  291.53   2.619 300.433   2.049 316.261   4.962 329.121   5.696
#Mann= 3 , 0 , 0
       0     .03       0  175.47     .03       0  232.27     .05       0
Bank Sta=175.47,232.27
XS Rating Curve= 0 ,0
Exp/Cntr=0.3,0.1

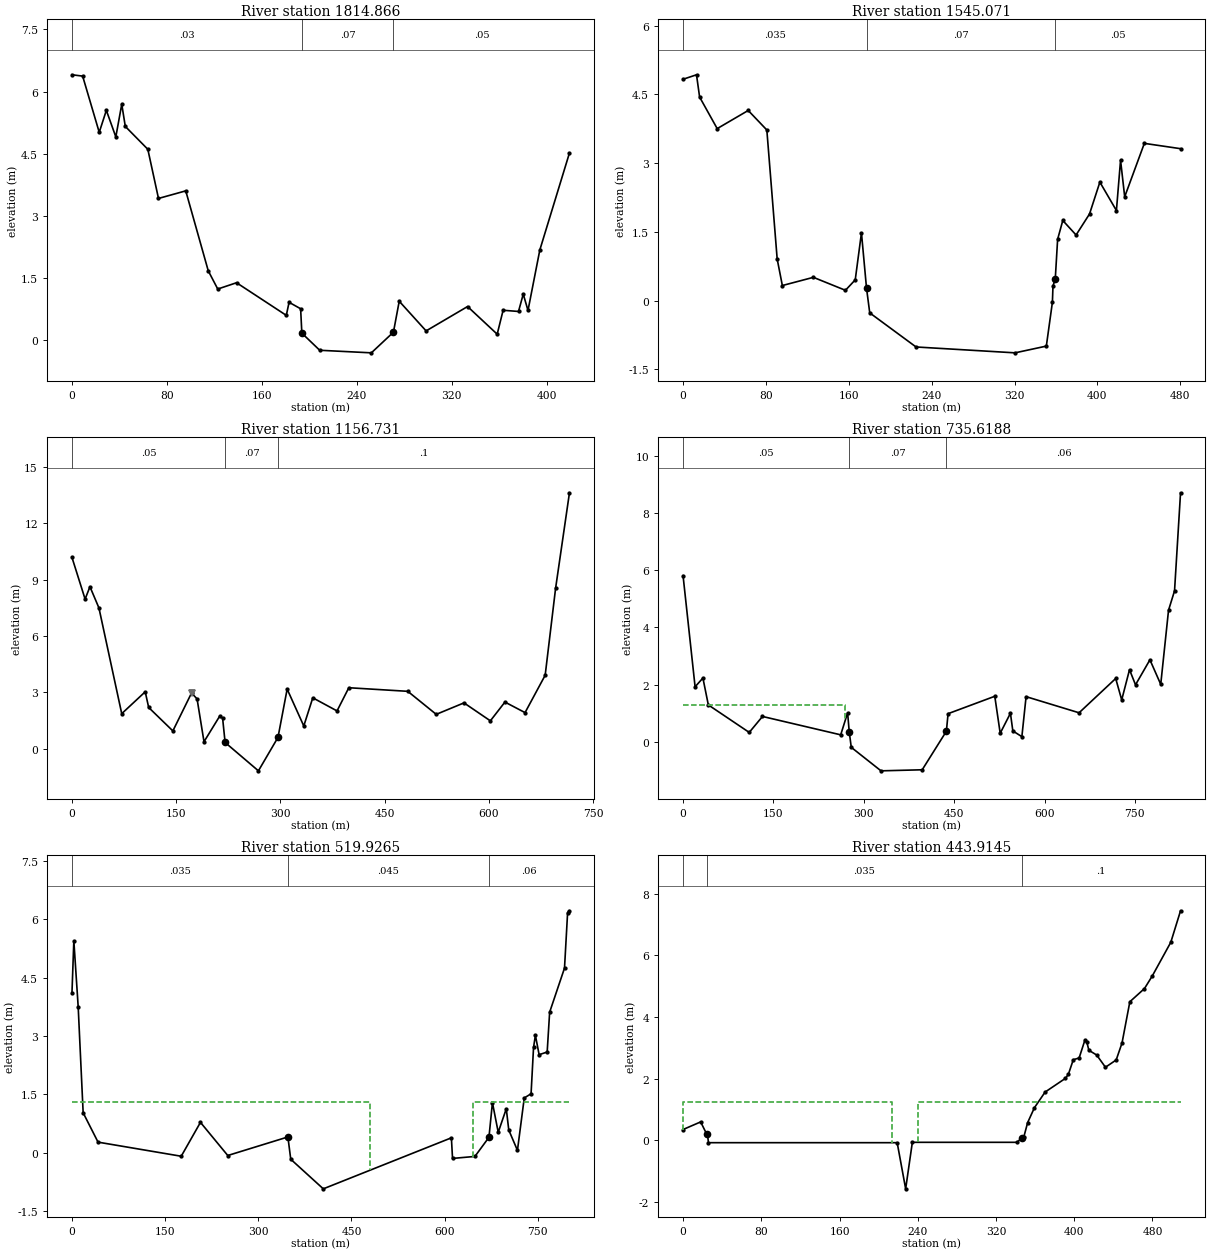
Type RM Length L Ch R = 1 ,1814.866,27.439,24.995,23.723
BEGIN DESCRIPTION:
Section 41
END DESCRIPTION:
Node Name=41
XS GIS Cut Line= 4
282229.9290349735272526.47517485282310.6742653875272428.66876699
282313.7404462565272422.53857374282440.3496357175272166.60115474
#Sta/Elev= 30
       0   6.407   8.988   6.375  22.969   5.019  28.961   5.549  36.951   4.909
  41.944   5.696   44.94   5.161  63.914    4.61  72.902   3.424  95.872   3.607
 114.846   1.678 122.836   1.239 138.676   1.391 180.609    .604 182.949    .919
 192.692    .763   193.7.1757512 208.768   -.238 252.294     -.3  270.89.1984574
 275.771    .945 298.419    .229 333.363    .817 358.322     .15 363.314    .727
 376.293    .698 380.287   1.117  384.28    .722 394.264   2.183 419.224   4.521
#Mann= 3 , 0 , 0
       0     .03       0   193.7     .07       0  270.89     .05       0
Bank Sta=193.7,270.89
XS Rating Curve= 0 ,0
Exp/Cntr=0.3,0.1

Type RM Length L Ch R = 1 ,1545.071,24.923,24.234,24.018
BEGIN DESCRIPTION:
Section 42
END DESCRIPTION:
Node Name=42
XS GIS Cut Line= 2
282412.2411279695272640.43028539282765.6052254015272315.17469571
#Sta/Elev= 30
       0   4.832   12.98    4.93  15.976   4.444   32.95   3.755  62.904   4.151
  80.877   3.725  90.862    .909  95.854     .33 125.808    .509 156.761    .226
  166.22    .454 172.221   1.479  177.11.2724791 180.223   -.267 224.932  -1.011
 320.507  -1.139 350.701   -.992 356.566   -.034 357.129    .322  359.31.4665211
 361.603   1.339 366.589    1.75 379.421   1.433 392.401   1.892 402.386   2.587
 418.361   1.967 422.355   3.066 426.349   2.267  445.32   3.433 480.267   3.317
#Mann= 3 , 0 , 0
       0    .035       0  177.11     .07       0  359.31     .05       0
Bank Sta=177.11,359.31
XS Rating Curve= 0 ,0
Exp/Cntr=0.3,0.1

Type RM Length L Ch R = 1 ,1156.731,24.771,24.771,24.771
BEGIN DESCRIPTION:
Section 43
END DESCRIPTION:
Node Name=43
XS GIS Cut Line= 4
282704.0342084265273021.90289057 282750.881721345272862.62134666
282905.4855401995272667.13056745283146.3838473515272487.49095268
#Sta/Elev= 30
       0  10.177  18.889   7.957  25.849   8.618  38.773    7.49  71.581   1.857
 105.383   3.022 110.354   2.186  145.15    .938  172.01   2.957 179.985   2.644
 189.955    .362 212.297   1.711  216.69   1.629  220.32    .323 268.251  -1.188
  296.41.5946554 309.589   3.165 333.515   1.201 346.476   2.701 381.369   2.003
 398.317   3.238 483.153   3.047 524.086    1.82  564.02   2.431 601.957   1.475
 622.922   2.475 651.875   1.913 680.827   3.903 695.802    8.53 715.769  13.621
#Mann= 3 , 0 , 0
       0     .05       0  220.32     .07       0  296.41      .1       0
Levee=-1,172.01,2.96,0,,,,
Bank Sta=220.32,296.41
XS Rating Curve= 0 ,0
Exp/Cntr=0.3,0.1

Type RM Length L Ch R = 1 ,735.6188,23.966,23.966,23.966
BEGIN DESCRIPTION:
Section 44
END DESCRIPTION:
Node Name=44
XS GIS Cut Line= 5
282936.9332726415273345.81997989283086.8453139775273186.53843598
283154.5526840875272868.97747977283193.8805513565272752.50690277
283295.1372609955272629.32863744
#Sta/Elev= 30
       0   5.805  19.976   1.923   32.96   2.229  41.949    1.29 109.866    .329
 131.839    .887 261.693    .245 273.157   1.015  275.82.3542499  279.23   -.192
  328.57  -1.013 396.976   -.976  437.12.3708771 439.923    .984 517.459   1.592
  526.45      .3 543.435    .999 547.433    .381 562.424    .181  569.42   1.579
 657.372   1.015 718.189   2.213 728.155   1.465 741.111   2.521 751.077   1.992
 774.995   2.866 792.933   2.009 805.889   4.598 815.854   5.275  825.82   8.701
#Mann= 3 , 0 , 0
       0     .05       0  275.82     .07       0  437.12     .06       0
#XS Ineff= 2 , 0
       0   268.8     1.3     772       0     1.3
Permanent Ineff=
       F       F
Bank Sta=275.82,437.12
XS Rating Curve= 0 ,0
Exp/Cntr=0.3,0.1

Type RM Length L Ch R = 1 ,519.9265,76.01,76.01,76.01
BEGIN DESCRIPTION:
Section 45
END DESCRIPTION:
Node Name=45
XS GIS Cut Line= 4
283033.4976219335273430.97415832283259.0553987255273250.64086736
283387.411682446   5272848.20008283415.5835134895272763.01970187
#Sta/Elev= 30
       0   4.115   2.998   5.444   9.993    3.75  17.987   1.028  41.969    .274
 175.868   -.088 206.845    .782 250.812   -.069  347.62.4073217 352.211   -.165
 404.603   -.925 610.825    .385 612.676   -.144  648.72   -.093  671.29.3980832
 676.912   1.288 686.233    .527 699.214   1.131 703.209    .585 717.179    .063
 728.145   1.409  739.11   1.516 743.098   2.707 746.089   3.016  752.07    2.52
 765.029   2.588 769.017   3.611 792.942   4.743 797.927   6.167 800.917   6.215
#Mann= 3 , 0 , 0
       0    .035       0  347.62    .045       0  671.29     .06       0
#XS Ineff= 2 , 0
       0     479     1.3   645.8       0     1.3
Permanent Ineff=
       F       F
Bank Sta=347.62,671.29
XS Rating Curve= 0 ,0
Exp/Cntr=0.3,0.1

Type RM Length L Ch R = 1 ,443.9145,17.06,17.06,17.06
BEGIN DESCRIPTION:
Section 46
END DESCRIPTION:
Node Name=46
XS GIS Cut Line= 6
283300.3700358045273231.86327597283361.1229911965273118.16049707
283393.0786741575273057.22175282 283428.564345355272994.23933117
283490.0604561625272891.12651697283550.9992004125272789.31422475
#Sta/Elev= 30
       0    .353  17.988      .6  23.984    .216  24.984    .191  25.983   -.074
 218.957   -.074 227.634  -1.571 234.472   -.062 341.456   -.062 346.417    .083
 348.402    .105 352.371    .577 359.316   1.061 370.231   1.568 391.072   2.014
 394.063   2.147 399.049   2.617 405.031   2.674 411.014   3.262 413.008   3.176
 415.002   2.923 422.979   2.769 431.953   2.373 442.921   2.609 448.904   3.161
 456.881   4.497 471.837   4.925 479.814   5.333 498.759   6.426  508.73   7.448
#Mann= 3 , 0 , 0
       0    .035       0  23.984    .035       0 346.417      .1       0
#XS Ineff= 2 , 0
       0   213.3    1.26   240.1       0    1.26
Permanent Ineff=
       F       F
Bank Sta=23.984,346.417
XS Rating Curve= 0 ,0
Exp/Cntr=0.5,0.3

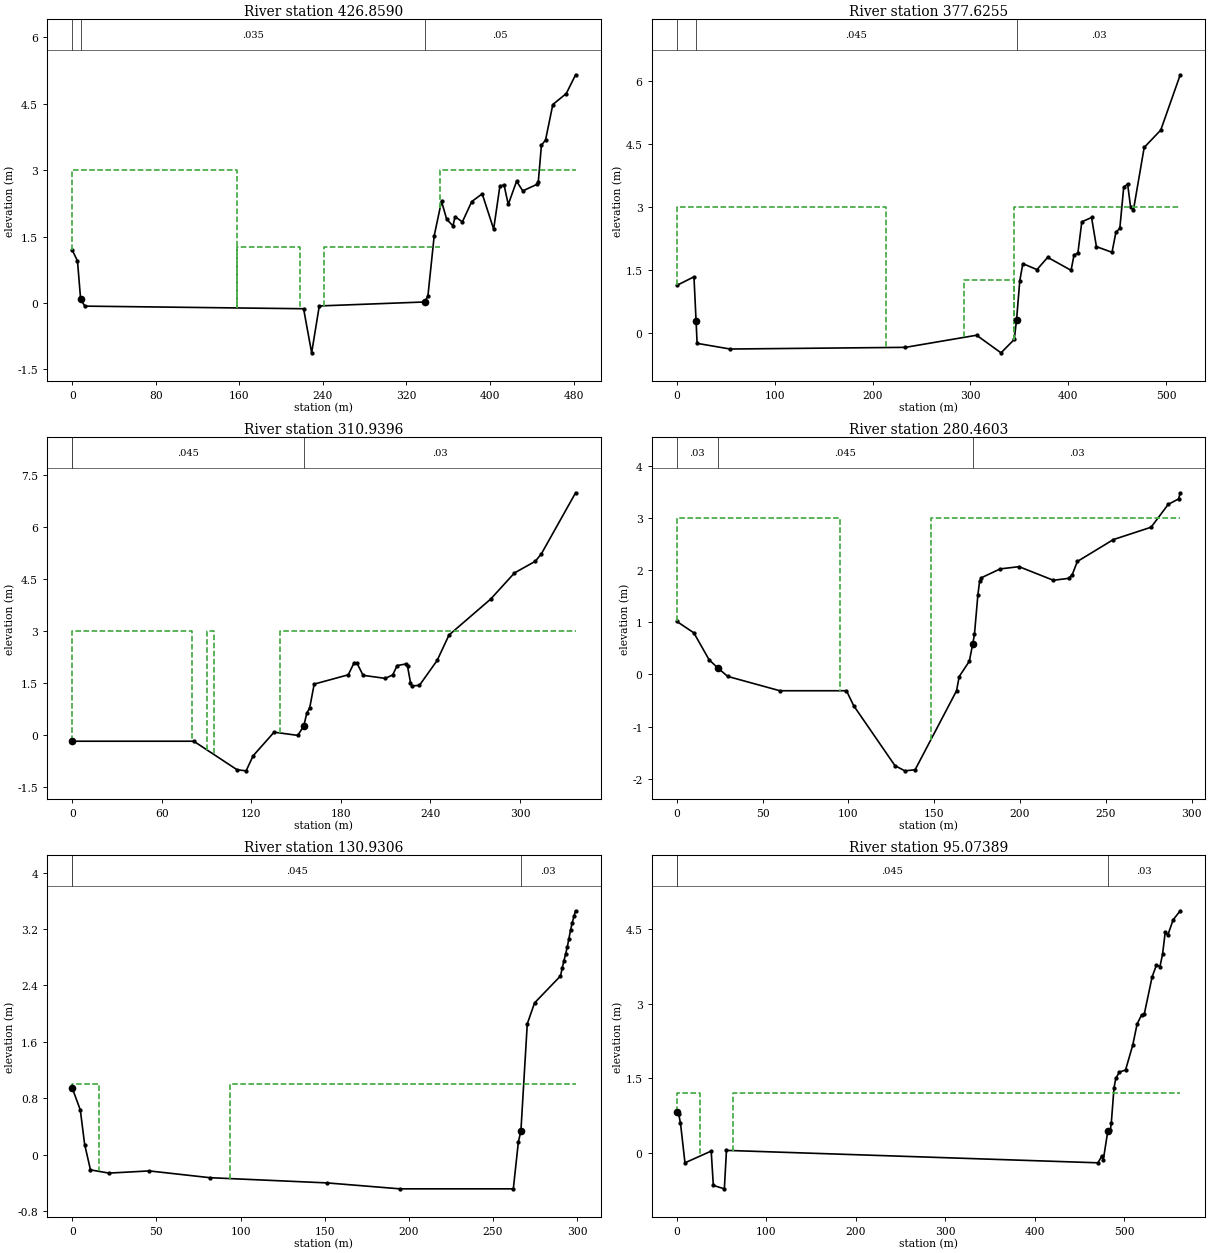
Type RM Length L Ch R = 1 ,426.8590,49.23,49.23,49.23
BEGIN DESCRIPTION:
Section 47
END DESCRIPTION:
Node Name=47
XS GIS Cut Line= 3
283310.0310562335273239.29483015283516.831999219 5272872.0801609
283547.5180335385272819.96757368
#Sta/Elev= 30
       0   1.193   4.993     .95   7.989    .088  11.984    -.07  221.49   -.129
 229.201  -1.125 236.502   -.066 337.553    .024 340.549    .167 346.542    1.52
 353.532   2.299 358.526   1.889 364.518   1.744 366.515   1.951 373.506   1.833
 382.494   2.291 392.481   2.467 403.467    1.67 409.459   2.645 413.454   2.662
 417.448   2.226 425.409    2.75 431.357   2.533 445.237   2.684 446.229   2.743
 449.203   3.562 453.169   3.684 460.109   4.483 472.997   4.731  481.92   5.155
#Mann= 3 , 0 , 0
       0    .035       0   7.989    .035       0 337.553     .05       0
#XS Ineff= 4 ,-1
       0   158.2       3   158.2   218.5    1.26   240.6   352.2    1.26
   352.2     500       3
Permanent Ineff=
       F       F       F       F
Bank Sta=7.989,337.553
XS Rating Curve= 0 ,0
Exp/Cntr=0.5,0.3

Type RM Length L Ch R = 1 ,377.6255,66.69,66.69,66.69
BEGIN DESCRIPTION:
Section 48
END DESCRIPTION:
Node Name=48
XS GIS Cut Line= 3
283316.6865485525273255.19152789283532.2738355985272947.01733186
283567.0444739495272812.91860813
#Sta/Elev= 30
       0   1.134  17.429   1.337  19.561    .293  20.634    -.25  54.431   -.385
 233.617   -.345 306.411   -.056  331.39   -.476 344.924   -.156 347.286    .318
 350.561   1.245 353.709   1.652 368.118   1.509 379.089   1.802 403.008   1.492
 405.998   1.856 409.985   1.906 413.971   2.648 423.938   2.752 428.921   2.057
 444.867   1.922 448.854   2.401  452.84   2.493 456.827   3.473 460.813   3.553
 463.803   3.007 466.793   2.934 477.756   4.423 494.699   4.837 514.632   6.156
#Mann= 3 , 0 , 0
       0     .03       0  19.561    .045       0 347.286     .03       0
#XS Ineff= 3 ,-1
       0     214       3     294   344.2    1.26   344.2     515       3
Permanent Ineff=
       F       F       F
Bank Sta=19.561,347.286
XS Rating Curve= 0 ,0
Exp/Cntr=0.3,0.1

Type RM Length L Ch R = 1 ,310.9396,30.48,30.48,30.48
BEGIN DESCRIPTION:
Section 49
END DESCRIPTION:
Node Name=49
XS GIS Cut Line= 6
283502.2181972345273133.89678214283519.2490634915273100.62504274
283532.5992213525273046.17045146283541.3822199455272973.09590316
283566.8528555155272876.13751009283575.852241862  5272806.801189
#Sta/Elev= 30
       0   -.176  81.403   -.176  110.44      -1 116.476   -1.03 121.153   -.597
 135.218    .085 151.131   -.008  155.11    .266 157.099    .629 159.088    .789
 162.072   1.471 184.911   1.739 188.881   2.092 190.866   2.066 194.836   1.724
 209.725   1.636 214.687   1.737 217.665   2.006  223.62   2.052 224.613   1.985
 226.598   1.517  227.59   1.421 232.553   1.433 244.464   2.154 252.404   2.887
 280.278   3.921 296.259   4.676 310.243   5.014 314.238   5.224 337.211   6.988
#Mann= 3 , 0 , 0
       0     .03       0       0    .045       0  155.11     .03       0
#XS Ineff= 3 ,-1
       0      80       3      90      95       3   138.9     350       3
Permanent Ineff=
       F       F       F
Bank Sta=0,155.11
XS Rating Curve= 0 ,0
Exp/Cntr=0.5,0.3

Type RM Length L Ch R = 1 ,280.4603,172.11,131.4,203.46
BEGIN DESCRIPTION:
Section 50
END DESCRIPTION:
Node Name=50
XS GIS Cut Line= 6
 283522.062444495273149.85000052283543.8822346655273128.40303837
283551.8497124315273098.99925137283561.5245068615273060.86917921
283569.839135387 5272990.3105804283579.6760938115272868.75387987
#Sta/Elev= 30
       0   1.016   9.869    .798  18.752    .282  23.687    .129  29.608   -.038
      60   -.313  98.846   -.313     103   -.598 127.084   -1.75 132.828   -1.85
 138.837   -1.83     163   -.313 164.537   -.041 170.458    .254 172.444    .588
 173.444    .771 175.443    1.53 176.443   1.788 177.442   1.855 188.438   2.025
 199.434   2.068 219.426   1.807 228.423   1.844 230.422   1.913 233.421   2.168
 254.413   2.588 276.405   2.825 286.401   3.264 292.399   3.367 293.399   3.486
#Mann= 3 , 0 , 0
       0     .03       0  23.687    .045       0 172.444     .03       0
#XS Ineff= 2 , 0
       0      95       3     148       0       3
Permanent Ineff=
       F       F
Bank Sta=23.687,172.444
XS Rating Curve= 0 ,0
Exp/Cntr=0.5,0.3

Type RM Length L Ch R = 1 ,130.9306,169.92,21.35,20
BEGIN DESCRIPTION:
Section 51
END DESCRIPTION:
Node Name=51
XS GIS Cut Line= 2
283580.291020371 5273158.8379694 283844.99891245 5273019.6966415
#Sta/Elev= 24
       0    .944   4.781    .634   7.363    .145  10.808   -.214  21.776    -.26
  45.704   -.229  81.778   -.325  151.43   -.399 194.655   -.483 262.048   -.483
 265.031    .179 266.551    .338 270.335   1.855 274.659   2.152 290.077   2.534
 291.074   2.643 292.071   2.746 293.068    2.84 294.065    2.94 295.061   3.061
 296.058   3.186 297.055   3.287 298.052   3.379 299.049   3.458
#Mann= 3 , 0 , 0
       0     .03       0       0    .045       0 266.551     .03       0
#XS Ineff= 2 , 0
       0    15.7       1    93.8       0       1
Permanent Ineff=
       F       F
Bank Sta=0,266.551
XS Rating Curve= 0 ,0
Exp/Cntr=0.3,0.1

Type RM Length L Ch R = 1 ,95.07389,20.65,22.28,17.68
BEGIN DESCRIPTION:
Section 52
END DESCRIPTION:
Node Name=52
XS GIS Cut Line= 6
283579.6496718225273162.69039581 283674.780875735273162.73952167
283790.3245664085273200.24693075 283844.280166795273206.47257695
284004.071752543 5273216.3298501284134.2915188525273207.51018465
#Sta/Elev= 30
       0    .813   1.997    .777   3.993    .597   8.985     -.2  38.316    .036
  40.702   -.655   53.03   -.724  55.376     .05 470.775     -.2 474.754   -.073
 476.743   -.136 481.716    .436   484.7     .47 485.694    .609 488.678   1.308
 490.667   1.498 494.646   1.625 501.608   1.669 509.566   2.165  514.54   2.595
 519.514   2.777 522.499   2.791 531.335   3.545 536.192   3.782 540.077   3.749
 542.991   4.001 545.905   4.438 548.861   4.385 554.813   4.692 562.749   4.873
#Mann= 3 , 0 , 0
       0     .03       0       0    .045       0 481.716     .03       0
#XS Ineff= 2 , 0
       0    25.8     1.2   63.18       0     1.2
Permanent Ineff=
       F       F
Bank Sta=0,481.716
XS Rating Curve= 0 ,0
Exp/Cntr=0.5,0.3

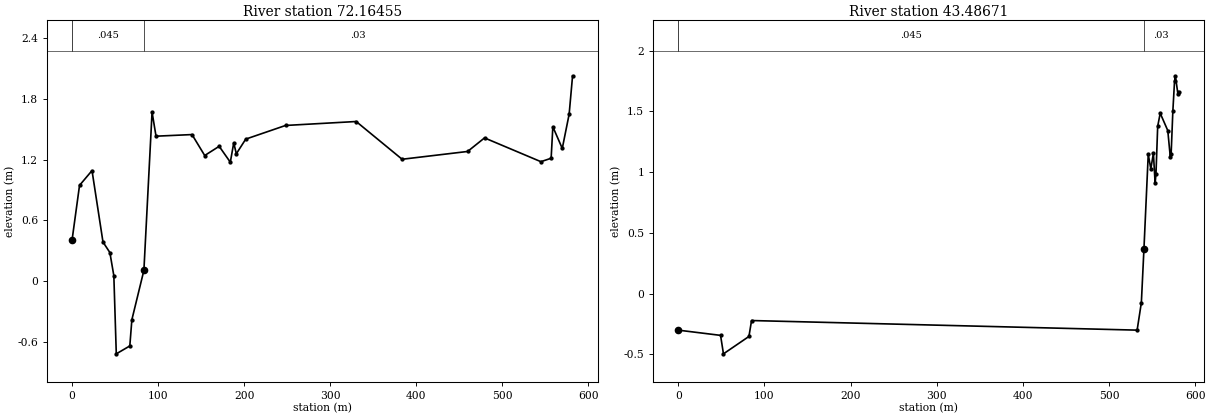
Type RM Length L Ch R = 1 ,72.16455,43.33,84.24,26.07
BEGIN DESCRIPTION:
Section 53
END DESCRIPTION:
Node Name=53
XS GIS Cut Line= 6
283577.704157385 5273166.1923218283685.2826575295273187.68436555
283785.4850992485273228.83788666283917.7800809575273220.66672603
284104.1603640125273263.85714652284136.8450065535273251.40585413
#Sta/Elev= 30
       0    .409   8.609    .945  23.119   1.091  35.872    .385  43.885    .281
  48.489    .052  51.335    -.72  67.063   -.642  69.443   -.383  83.424    .105
  92.922   1.669  97.526   1.431 139.356   1.447 154.117    1.24 170.926   1.331
 183.883   1.174  187.87   1.365  190.86   1.257 201.791   1.402 248.094   1.537
 330.178   1.576 383.581   1.203 459.717    1.28 479.383   1.414 544.924   1.179
 556.814   1.213 558.796   1.524 569.759    1.31 577.741   1.648 581.732   2.028
#Mann= 3 , 0 , 0
       0     .03       0       0    .045       0  83.424     .03       0
Bank Sta=0,83.424
XS Rating Curve= 0 ,0
Exp/Cntr=0.5,0.3

Type RM Length L Ch R = 1 ,43.48671,228,228,228
BEGIN DESCRIPTION:
Section 54
END DESCRIPTION:
Node Name=54
XS GIS Cut Line= 6
283570.219214844 5273197.5961977283688.2993020925273218.28176043
 283771.903451465273241.12206928283926.6142227135273241.98396772
284097.4564455145273270.80425433 284140.928278475273255.77052092
#Sta/Elev= 23
       0     -.3   49.09   -.343  52.453   -.495  82.026   -.352  85.079   -.221
 532.729     -.3 537.649   -.073 540.644    .369 545.635   1.147 548.629   1.027
 551.624   1.155  553.62    .909 554.618    .988 556.594   1.377 559.525   1.485
 568.321   1.342 571.253   1.123  572.23   1.152 574.185     1.5 576.139   1.746
 577.117   1.793 580.049   1.644 581.026   1.663
#Mann= 3 , 0 , 0
       0     .03       0       0    .045       0 540.644     .03       0
Bank Sta=0,540.644
XS Rating Curve= 0 ,0
Exp/Cntr=0.5,0.3